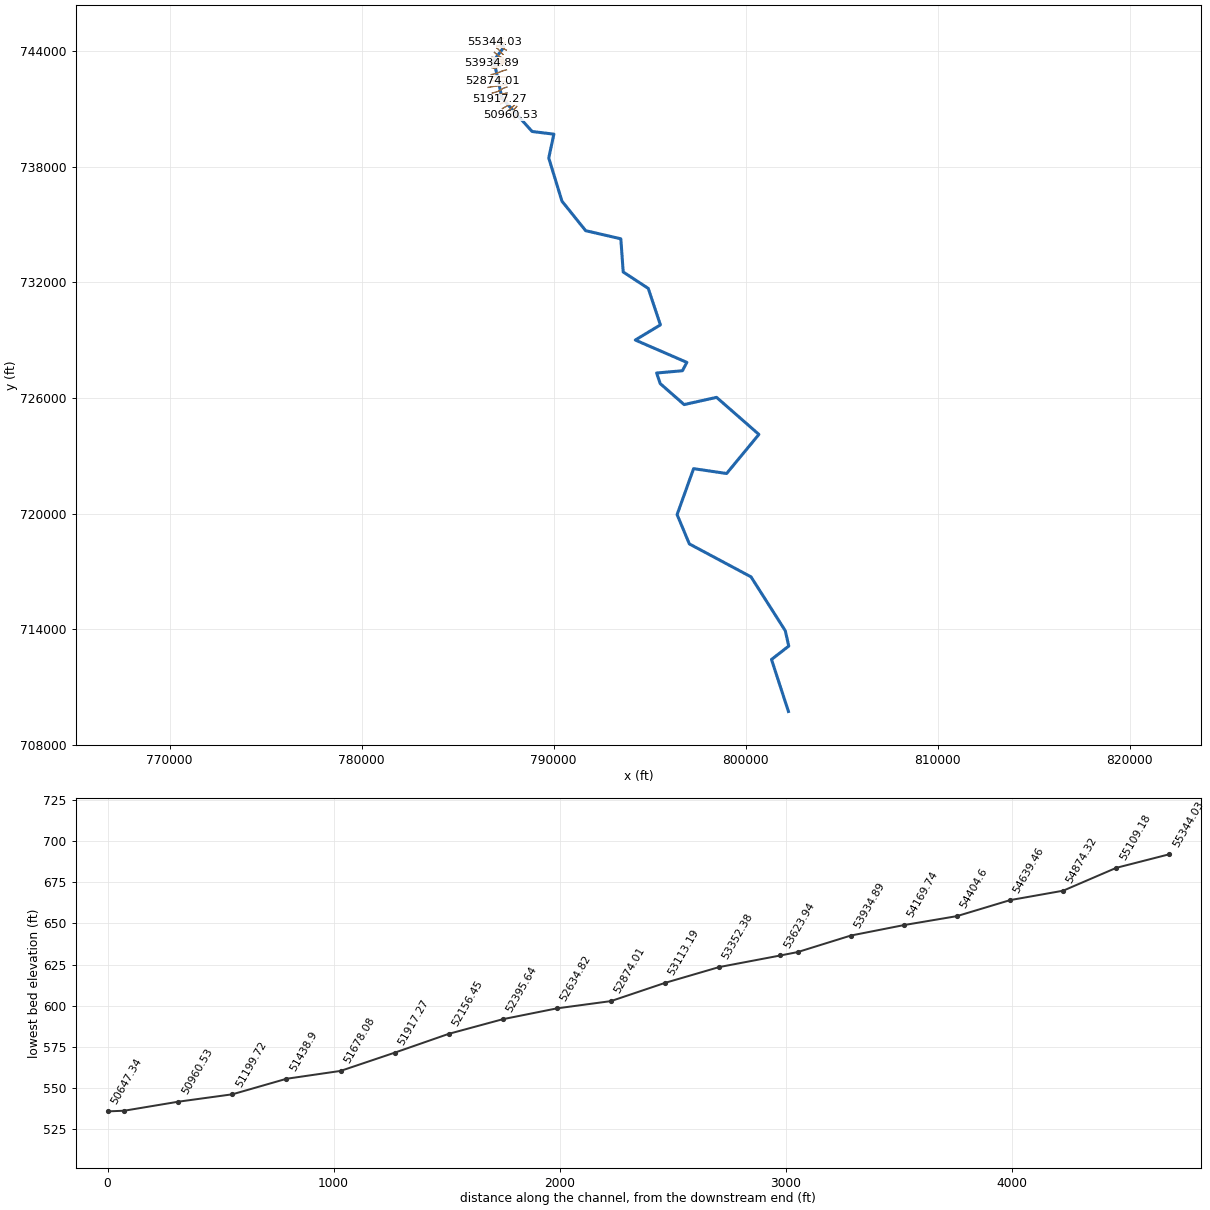
--- 6721_ras.prj (project) ---

Proj Title=6721
Current Plan=p01
Default Exp/Contr=0.3,0.1
English Units
Geom File=g01
Flow File=f01
Plan File=p01
Y Axis Title=Elevation
X Axis Title(PF)=Main Channel Distance
X Axis Title(XS)=Station
BEGIN DESCRIPTION:
RFD model 6721 exported to HEC-RAS
END DESCRIPTION:

--- 6721_ras.p01 (plan) ---

Plan Title=Plan 01
Program Version=4.10
Short Identifier=Plan 01
Geom File=g01
Flow File=f01
Subcritical Flow
Calc Critical at every XS
Secant Critical Depth

--- 6721_ras.f01 (steady flow) ---

Flow Title=Flow 01
Program Version=5.01
Number of Profiles= 6
Profile Names=10yr,25yr,50yr,100yr,100plus,500yr
River Rch & RM=6721,144,55344.03
 3798.82 6065.45 8199.2810103.9214751.7216337.73
River Rch & RM=6721,144,55109.18
 3802.81 6072.54 8209.5210117.2514771.1816358.81
River Rch & RM=6721,144,54874.32
 3892.89 6229.81 8434.1810407.3815194.7716808.32
River Rch & RM=6721,144,54639.46
 3896.18 6235.68 8442.6710418.4615210.9516825.83
River Rch & RM=6721,144, 54404.6
 3899.47 6241.55 8451.1610429.5315227.1116843.34
River Rch & RM=6721,144,54169.74
 3918.14 6274.46 8498.4310490.8615316.6616939.09
River Rch & RM=6721,144,53934.89
  3924.4 6285.62 8514.5710511.92 15347.416972.34
River Rch & RM=6721,144,53700.28
 3962.52 6352.12 8609.5410634.5315526.41 17161.4
River Rch & RM=6721,144,53623.94
 3965.18 6356.86 8616.3810643.4615539.4417175.46
River Rch & RM=6721,144,53352.38
 3977.05 6378.01 8646.9610683.3315597.6717238.28
River Rch & RM=6721,144,53113.19
 3978.15 6379.96 8649.7810687.0215603.0417244.07
River Rch & RM=6721,144,52874.01
 4068.08  6535.5 8870.8510971.3416018.1517677.17
River Rch & RM=6721,144,52634.82
 4092.83 6579.24 8933.8211053.1916137.6617804.57
River Rch & RM=6721,144,52395.64
 4102.82  6596.9 8959.2411086.2216185.8917855.92
River Rch & RM=6721,144,52156.45
 4145.53 6672.67 9068.5111228.5116393.6218077.77
River Rch & RM=6721,144,51917.27
 4197.64 6764.17 9199.7311398.5716641.9118339.69
River Rch & RM=6721,144,51678.08
  4204.7 6776.65 9217.7111421.9516676.0518375.95
River Rch & RM=6721,144, 51438.9
 4209.24 6784.69 9229.2911437.0116698.04 18399.3
River Rch & RM=6721,144,51199.72
 4210.49  6786.9 9232.4811441.16 16704.118405.75
River Rch & RM=6721,144,50960.53
 4215.47 6795.73 9245.2111457.74 16728.3 18431.5
River Rch & RM=6721,144,50721.35
    4238 6835.67 9302.8211532.7616837.8318548.01
River Rch & RM=6721,144,50647.34
 4239.24 6837.87    930611536.8916843.8718554.43
River Rch & RM=6721,144,50384.83
 4249.31 6855.74 9331.7711570.4616892.8818606.56
River Rch & RM=6721,144,50046.04
 4251.94 6860.41 9338.5111579.2416905.6918620.19
River Rch & RM=6721,144,49400.05
 4969.61 8091.8111082.0513814.7920169.5921924.92
River Rch & RM=6721,144,49069.73
 4973.51  8098.711091.9813827.7120188.4621944.45
River Rch & RM=6721,144,48820.42
 4974.55 8100.5411094.6413831.1820193.5321949.71
River Rch & RM=6721,144, 48571.1
 4976.78  8104.511100.3513838.6220204.3821960.98
River Rch & RM=6721,144,48287.13
 5648.34 9246.3912709.1715892.5523203.13 24897.5
River Rch & RM=6721,144,47823.15
 5654.14 9256.6512723.9615911.8223231.2624926.09
River Rch & RM=6721,144,47573.83
 5662.71 9271.7812745.7815940.2423272.7524968.24
River Rch & RM=6721,144,47324.51
 5670.42 9285.4112765.4115965.7923310.0525006.07
River Rch & RM=6721,144, 47075.2
 5677.07 9297.1712782.38 15987.923342.34 25038.9
River Rch & RM=6721,144,46825.88
 5682.54 9306.8512796.3616006.1423368.96   25066
River Rch & RM=6721,144,46576.56
 5733.65 9397.2712926.7916176.0823617.0725317.91
River Rch & RM=6721,144,46327.25
 5818.27 9547.4113143.7916459.2824030.5525738.42
River Rch & RM=6721,144,46077.93
 5818.97 9548.65 13145.616461.64   2403425741.95
River Rch & RM=6721,144,45828.61
 5823.85 9557.3713158.2516478.1924058.1625766.64
River Rch & RM=6721,144, 45579.3
 5825.53 9560.3613162.5816483.8624066.44 25775.1
River Rch & RM=6721,144,45329.98
  5827.9 9564.5813168.7116491.8924078.1625787.09
River Rch & RM=6721,144,45080.66
 5843.86 9593.1213210.1316546.1324157.3525868.13
River Rch & RM=6721,144,44831.35
 5848.65 9601.7113222.6316562.5424181.3225892.77
River Rch & RM=6721,144,44582.03
 5851.53 9606.8813230.15 16572.424195.7125907.55
River Rch & RM=6721,144,44332.71
 5853.85 9611.0513236.2216580.3724207.3525919.52
River Rch & RM=6721,144,44083.39
 5866.33 9633.5113268.9516623.3924270.1525984.23
River Rch & RM=6721,144,43834.08
  5868.5 9637.4113274.6316630.8624281.0525995.48
River Rch & RM=6721,144,43584.76
 5869.84 9639.8413278.1816635.5224287.86 26002.5
River Rch & RM=6721,144,43335.44
 5876.98 9652.7213296.9716660.2324323.9426039.74
River Rch & RM=6721,144,43086.13
 5881.67 9661.1813309.3316676.5124347.7126064.32
River Rch & RM=6721,144,42836.81
 5883.26 9664.0713313.5516682.0824355.8426072.75
River Rch & RM=6721,144,42587.49
 7607.9312604.5617465.8521993.2132110.0933414.68
River Rch & RM=6721,144,42338.18
  7675.612722.6117634.9522212.2132429.8333720.48
River Rch & RM=6721,144,42088.86
 7683.4712736.8617655.79 22239.732469.9633760.45
River Rch & RM=6721,144,41839.54
 7685.0712739.7717660.0622245.3432478.19 33768.7
River Rch & RM=6721,144,41590.23
 7739.4412834.95 17796.722422.6332737.0434016.97
River Rch & RM=6721,144,41340.91
 7741.2712838.29 17801.622429.11 32746.534026.45
River Rch & RM=6721,144,41091.59
 7743.4712842.2917807.4822436.8932757.8634037.84
River Rch & RM=6721,144,40842.28
 7744.9412844.96 17811.422442.0832765.4434045.42
River Rch & RM=6721,144,40592.96
 7874.6113076.8318148.4222884.0533410.7134678.52
River Rch & RM=6721,144,40470.51
  7877.413081.9118155.8822893.9333425.1434692.95
River Rch & RM=6721,144,39986.75
 7879.3513085.4618161.0922900.82 33435.234702.99
River Rch & RM=6721,144,39744.87
 7880.0813086.7918163.0522903.4133438.9734706.75
River Rch & RM=6721,144,39502.99
 9211.5115313.92 21271.526836.6639181.53 39804.5
River Rch & RM=6721,144,39261.11
 9224.5215337.7321306.5526883.1439249.3839871.07
River Rch & RM=6721,144,39019.23
 9225.33 15339.221308.7326886.0339253.6139875.23
River Rch & RM=6721,144,38777.35
 9284.1515443.6621459.9927083.7439542.2640149.37
River Rch & RM=6721,144,38535.46
 9286.4315447.8521466.1927091.9739554.2940161.22
River Rch & RM=6721,144,38293.58
 9294.9415463.3221488.8827121.9739598.0840203.87
River Rch & RM=6721,144, 38051.7
 9300.2615473.1221503.3927141.2839626.2740231.71
River Rch & RM=6721,144,37809.82
 9303.4315478.9621512.0327152.7739643.0540248.28
River Rch & RM=6721,144,37492.07
 9306.0315483.7621519.1327162.2139656.83 40261.9
River Rch & RM=6721,144,37413.49
 9482.0915799.31 21978.627765.6140537.7941105.49
River Rch & RM=6721,144, 37172.3
 9484.7915804.2921985.9727775.41 40552.141119.58
River Rch & RM=6721,144,36931.12
 9571.0315958.7222210.7428070.5140982.9441530.88
River Rch & RM=6721,144,36689.94
 9576.5515968.8822225.7628090.4841012.1141559.53
River Rch & RM=6721,144,36448.76
 9577.3415970.3322227.9128093.3441016.2741563.63
River Rch & RM=6721,144,36207.58
 9580.3315975.8822236.1328104.2941032.2641579.41
River Rch & RM=6721,144, 35966.4
 9581.2115977.5122238.5528107.5341036.9941584.08
River Rch & RM=6721,144, 35532.4
 9603.2916018.4122299.2428188.49 41155.241700.91
River Rch & RM=6721,144,35085.57
 9610.7216032.2222319.7728215.9141195.2341740.61
River Rch & RM=6721,144,34760.49
 9612.7816036.0622325.4728223.5541206.3941751.69
River Rch & RM=6721,144,34519.31
 9614.8816039.9522331.2528231.2541217.6341762.78
River Rch & RM=6721,144,34036.94
 9627.5716063.2522365.6528276.9541284.3541828.11
River Rch & RM=6721,144,33483.65
 9712.1516213.5822583.5128561.9441700.4442220.99
River Rch & RM=6721,144,33072.22
 9763.4116306.1822719.0228740.6341961.3242471.69
River Rch & RM=6721,144,32831.04
 9765.6616310.3222725.1328748.7641973.1842483.28
River Rch & RM=6721,144,32589.85
 9773.97 16325.622747.7128778.7842017.0242526.16
River Rch & RM=6721,144,32348.67
 9780.4116337.5522765.4628802.4942051.6342560.34
River Rch & RM=6721,144,32107.49
 9782.9916342.3622772.6228812.0742065.6342574.23
River Rch & RM=6721,144,31835.26
 9785.2516346.57 22778.928820.4742077.8942586.39
River Rch & RM=6721,144,31714.28
 9786.5216348.9522782.4628825.2442084.8642593.34
River Rch & RM=6721,144,31306.96
 9789.7216354.9422791.3828837.2142102.3342610.71
River Rch & RM=6721,144,30099.87
 9934.6816622.0523186.65 29363.442870.5743362.99
River Rch & RM=6721,144,28832.76
 9944.5416640.6923214.6329401.0942925.5943418.17
River Rch & RM=6721,144,28353.74
 9951.2516653.2323233.3229426.1242962.1343454.37
River Rch & RM=6721,144,27874.72
  9958.216666.1223252.4629451.6942999.4743491.13
River Rch & RM=6721,144, 27395.7
10030.6716799.0523448.7129712.4343380.1543861.48
River Rch & RM=6721,144,26916.68
10116.7916959.7123688.1330033.0543848.2644324.13
River Rch & RM=6721,144,26437.66
10119.2416964.3423695.0830042.4343861.94 44337.8
River Rch & RM=6721,144,25958.64
10121.0216967.8223700.3830049.6543872.4944348.63
River Rch & RM=6721,144,25479.62
10123.4716972.5723707.6330059.5443886.9344363.45
River Rch & RM=6721,144,24591.14
10130.7916986.8423729.3730089.1943930.2244407.88
River Rch & RM=6721,144,23702.66
10255.4217223.6624085.9130570.6444633.1445113.67
River Rch & RM=6721,144,22814.18
10269.8217251.8824129.09 30629.744719.3645202.51
River Rch & RM=6721,144,22074.79
10279.2417270.3524157.36 30668.444775.8645260.75
River Rch & RM=6721,144,21037.22
12493.6621061.7129530.6537560.0654837.6954080.49
River Rch & RM=6721,144,19999.68
12521.3321114.9629611.4237669.7954997.8954238.55
River Rch & RM=6721,144,19556.42
12525.7721123.6229624.6537687.8655024.2854264.87
River Rch & RM=6721,144,18816.02
12532.6121136.9529645.0137715.6855064.89 54305.4
River Rch & RM=6721,144,18183.76
12536.5321144.6629656.8237731.85 55088.554329.08
River Rch & RM=6721,144,17974.75
12537.1421145.8529658.6537734.3655092.1754332.77
River Rch & RM=6721,144,16736.02
12585.4821240.6829803.9537933.3455382.6754623.96
River Rch & RM=6721,144,16576.28
 12586.121241.8829805.7937935.8655386.3554627.65
River Rch & RM=6721,144,16090.23
12623.1921313.0429913.55 38082.155599.8754837.52
River Rch & RM=6721,144,15604.18
12759.7921569.9530298.5338600.0656356.0955566.48
River Rch & RM=6721,144,15118.13
12765.3121580.6830314.8938622.3856388.67 55598.8
River Rch & RM=6721,144,14632.08
   1276721583.96 30319.938629.2256398.6755608.71
River Rch & RM=6721,144,13939.42
12791.5521631.4730392.2138727.7556542.5155750.99
River Rch & RM=6721,144,13173.92
 13000.622025.0530982.4439522.4657702.79 56868.1
River Rch & RM=6721,144,12687.87
13007.7222038.6731003.0439550.3957743.5756907.89
River Rch & RM=6721,144,12245.89
13075.3822167.2231196.8339812.4358126.1557278.93
River Rch & RM=6721,144,11803.92
13077.7822171.8131203.7739821.8458139.8857292.33
River Rch & RM=6721,144,11361.94
13099.4422213.4831267.0239907.8358265.4357415.45
River Rch & RM=6721,144,10919.96
13102.8322219.9831276.8539921.1858284.93 57434.5
River Rch & RM=6721,144,10477.98
13106.46 22226.9 31287.339935.34 58305.657454.58
River Rch & RM=6721,144,10308.53
13120.7922254.0831328.2539990.6958386.41 57532.8
River Rch & RM=6721,144,9827.521
13123.9722260.1331337.3840003.0458404.4357550.29
River Rch & RM=6721,144,9346.515
13131.5522274.5531359.1440032.46 58447.457591.96
River Rch & RM=6721,144,8865.509
13136.41 22283.831373.0840051.3458474.96 57618.7
River Rch & RM=6721,144,8384.503
13139.4922289.6631381.9340063.3258492.4557635.67
River Rch & RM=6721,144,7903.496
13147.2822304.4631404.2340093.4858536.4857678.33
River Rch & RM=6721,144, 7422.49
13150.8422311.2331414.4440107.2958556.6457697.86
River Rch & RM=6721,144,6941.484
13153.8422316.9331423.0440118.9258573.62 57714.3
River Rch & RM=6721,144,6460.478
13158.83 22326.4 31437.3 40138.258601.7757741.54
River Rch & RM=6721,144,5979.472
13165.9722339.9531457.7340165.8258642.0957780.58
River Rch & RM=6721,144,5498.465
13170.1822347.9631469.8140182.1558665.9457803.69
River Rch & RM=6721,144,5017.459
13174.7722356.6831482.9540199.9358691.9157828.86
River Rch & RM=6721,144,4536.453
13179.8422366.3131497.4740219.5658720.5657856.58
River Rch & RM=6721,144,2939.007
13282.5322561.0331790.7440615.8859299.19 58415.6
River Rch & RM=6721,144,1773.627
13297.6422589.8831834.35   40675 59385.558499.45
River Rch & RM=6721,144,1604.672
 13298.122590.7631835.68 40676.859388.1358502.01
River Rch & RM=6721,144,897.9641
 13299.122592.6831838.5940680.7459393.8858507.63
River Rch & RM=6721,144,       0
13327.91 22647.831922.0240793.9559559.1758668.54
Boundary for River Rch & Prof#=6721,144,1
Up Type= 0
Dn Type= 2
Boundary for River Rch & Prof#=6721,144,2
Up Type= 0
Dn Type= 2
Boundary for River Rch & Prof#=6721,144,2
Up Type= 0
Dn Type= 2
Boundary for River Rch & Prof#=6721,144,2
Up Type= 0
Dn Type= 2
Boundary for River Rch & Prof#=6721,144,2
Up Type= 0
Dn Type= 2
Boundary for River Rch & Prof#=6721,144,2
Up Type= 0
Dn Type= 2

--- 6721_ras.g01 (geometry) ---

Geom Title=6721
Program Version=4.10

River Reach=6721,144
Reach XY= 30
787189.570239215744567.536111643787401.024936053 744194.99494121
786891.452248814743519.529705084787312.371457726741571.794995179
788884.006543786739835.581219826790017.798069271739695.983538691
789750.622211903738460.484718374790439.565381675736216.412347834
 791673.20814386734687.673003864793504.411849382734266.651167851
793628.545816423732544.238497741 794934.09934941731691.130334517
795566.530866533729798.175296899 794258.75212714729012.310890068
796944.005315541727852.654285232796713.613238277727418.560890062
795367.842176856727300.335490011795559.247784049726749.326112508
796802.328516066725662.310890063798492.432682725726037.310890055
800696.859766037724114.133806719799016.284507306722086.561846299
  797294.9500438722335.922001183796435.633070739719952.022860194
797074.463932724718430.540056757800286.269488276 716722.20672338
 802070.58324516713925.703903517802251.547266037713130.192834517
801352.957787785 712432.22972512802235.188034895709735.621455343

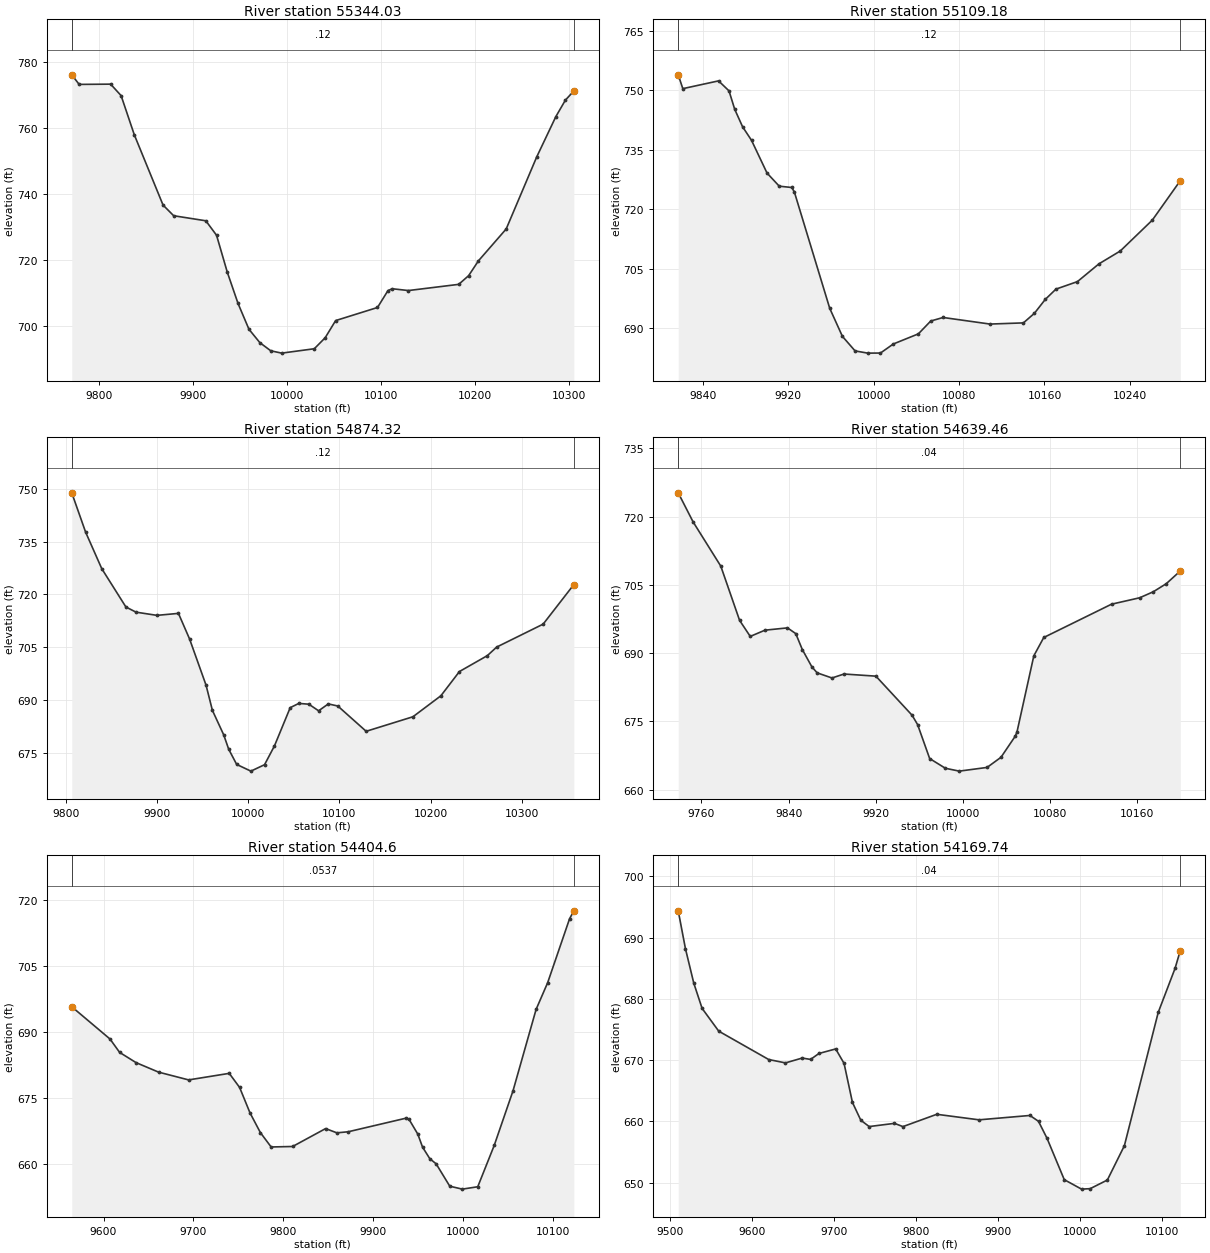
Type RM Length L Ch R = 1 ,55344.03,234.857600,234.857600,234.857600
XS GIS Cut Line= 6
787392.044330735744674.492589602787300.887950888744629.398268614
787154.138219212744545.913014481787086.691201204744512.938231583
786983.292549415744476.590745649786906.105065424 744460.81472218
#Sta/Elev= 30
 9770.97776.12419778.829773.22639812.299773.30599823.456 769.8329837.484757.9901
9868.082736.71329879.385733.48529913.597731.95719925.001727.57439936.405716.4206
9947.858706.93999959.467699.13539971.076695.07819982.684692.61489994.293691.9109
10028.98693.237610040.53696.552410051.69701.759610096.22705.721310107.35710.8256
 10111.9711.393510129.11710.848310182.62712.719110193.17715.350410203.61719.8369
10233.15 729.48710265.63751.295710285.99763.489910296.11768.464210305.11771.2437
#Mann= 3 , 0 , 0
 9770.97    0.12       0 9770.97    0.12       010305.11    0.12       0
#XS Ineff= 2 , 0
       0                               0
Bank Sta=9770.97,10305.11
Exp/Cntr=0.3,0.1

Type RM Length L Ch R = 1 ,55109.18,234.857600,234.857600,234.857600
XS GIS Cut Line= 6
787468.848037618744456.040911439787254.005896132744330.378712214
787217.765196089744313.879049459787170.801092597744300.901865191
787120.198334999744295.364187591787038.827107681744297.088950525
#Sta/Elev= 30
9817.124753.92729821.415 750.4379854.871752.39989864.663749.87259870.014745.2144
 9877.36740.81459885.722737.39719900.242729.13019911.683725.81359923.395725.4806
9925.814724.37349958.963694.97039970.819687.89849982.676684.22579994.532683.6636
10006.45683.685710018.54685.976810041.94688.529210053.52 691.76810065.11 692.663
10108.99691.001510140.27691.297910150.54693.708510160.69697.209710170.75699.8265
10190.87701.719710210.96706.200210230.96709.447610260.96717.241910287.17727.2115
#Mann= 3 , 0 , 0
9817.124    0.12       09817.124    0.12       010287.17    0.12       0
#XS Ineff= 2 , 0
       0                               0
Bank Sta=9817.124,10287.17
Exp/Cntr=0.3,0.1

Type RM Length L Ch R = 1 ,54874.32,234.857700,234.857700,234.857700
XS GIS Cut Line= 6
787539.117155575744062.112224951787441.663258167744110.135960334
787350.339461773 744190.88846358787330.853314418744202.048913328
787266.217335321744222.404326625787041.969618181744268.282604278
#Sta/Elev= 30
9806.644 748.8719821.794737.72349839.518727.32279865.993716.43499877.071714.9699
9900.053714.05679923.577714.62099935.794 707.3389953.866694.20779960.811687.0615
9973.192680.11469978.688676.01259987.417671.706310002.99669.801710017.97671.6272
10028.83676.969410046.09 687.832 10055.5689.039110066.53688.817510077.21686.9438
10087.89688.897410098.26688.302110129.36681.117210180.64685.248410211.25691.2053
10231.63698.103310262.21702.6191 10272.4 705.04310323.36711.565910357.02722.8085
#Mann= 3 , 0 , 0
9806.644    0.12       09806.644    0.12       010357.02    0.12       0
#XS Ineff= 2 , 0
       0                               0
Bank Sta=9806.644,10357.02
Exp/Cntr=0.3,0.1

Type RM Length L Ch R = 1 ,54639.46,234.857600,234.857600,234.857600
XS GIS Cut Line= 6
 787365.68861159743839.272801994787295.128211404743899.624513366
787240.494522341743958.810962717787135.304652821 744089.47845533
787101.272068414744123.604545722787044.090707184744165.847388754
#Sta/Elev= 30
9738.748725.22479752.339718.85549777.792709.11859795.031697.2094 9804.81693.6771
 9818.32695.04919838.971695.55359846.588694.2906 9852.58690.79429861.331687.0022
9866.189685.67089879.798 684.5469890.817685.41689920.094684.94699953.298676.3575
9958.345674.30899969.417666.84389983.845664.70689996.596664.0809 10022.1664.8945
10034.84 667.11910047.87671.733610049.52672.674610064.98689.4149 10074.1693.4413
10136.26700.757810162.07702.164610174.59703.489710186.44705.253410199.37708.0601
#Mann= 3 , 0 , 0
9738.748    0.04       09738.748    0.04       010199.37    0.04       0
#XS Ineff= 2 , 0
       09922.184                       0
Bank Sta=9738.748,10199.37
Exp/Cntr=0.3,0.1

Type RM Length L Ch R = 1 , 54404.6,234.857600,234.857600,234.857600
XS GIS Cut Line= 6
787384.761481352743638.322103572 787287.74460558 743677.04208929
787236.600776975743702.764249882787148.706505265743757.040678906
787083.087031448743806.870018274786921.055122248743941.622740237
#Sta/Elev= 30
9564.662695.73529607.184688.42149617.878685.39079636.165683.06729661.217 680.911
9694.613679.15029739.794680.63459751.338677.43899762.882671.6734 9774.45667.1955
9786.394663.94419810.283664.05059846.954668.10939859.511667.14899872.067  667.39
9936.213670.4635 9939.61670.25789949.523666.85259954.762663.91959962.833661.2911
9969.914660.11739985.067655.0456    9999654.383710016.18654.921310034.49 664.292
10055.41676.683710081.07695.138510093.91701.182110118.26715.667210123.05717.4878
#Mann= 3 , 0 , 0
9564.662  0.0537       09564.662  0.0537       010123.05  0.0537       0
#XS Ineff= 2 , 0
       09916.715                       0
Bank Sta=9564.662,10123.05
Exp/Cntr=0.3,0.1

Type RM Length L Ch R = 1 ,54169.74,234.857700,234.857700,234.857700
XS GIS Cut Line= 6
787393.706907063743549.056286454787305.064542125743563.445663882
787156.820432575743593.737444325787000.612069807743632.613332849
786889.300336674743667.083892957786798.761776905743689.859720129
#Sta/Elev= 30
9510.049694.3553 9518.87688.15629529.001682.55489539.131678.43879559.393674.7247
9620.331670.09039640.744669.54229661.157670.33179671.364670.1077 9681.57671.0796
9701.984671.8202 9712.19 669.4569722.397663.08779732.604660.1836 9742.81659.1525
9773.645659.6759 9783.95659.1451 9825.17 661.1549876.695660.25139938.788660.9644
9949.196660.00579959.603657.23429980.598650.487310001.67648.943610012.18 649.019
10033.13650.430310053.86 656.02410095.13677.781710115.65684.967810122.05687.8811
#Mann= 3 , 0 , 0
9510.049    0.04       09510.049    0.04       010122.05    0.04       0
#XS Ineff= 2 , 0
       09865.808                       0
Bank Sta=9510.049,10122.05
Exp/Cntr=0.3,0.1

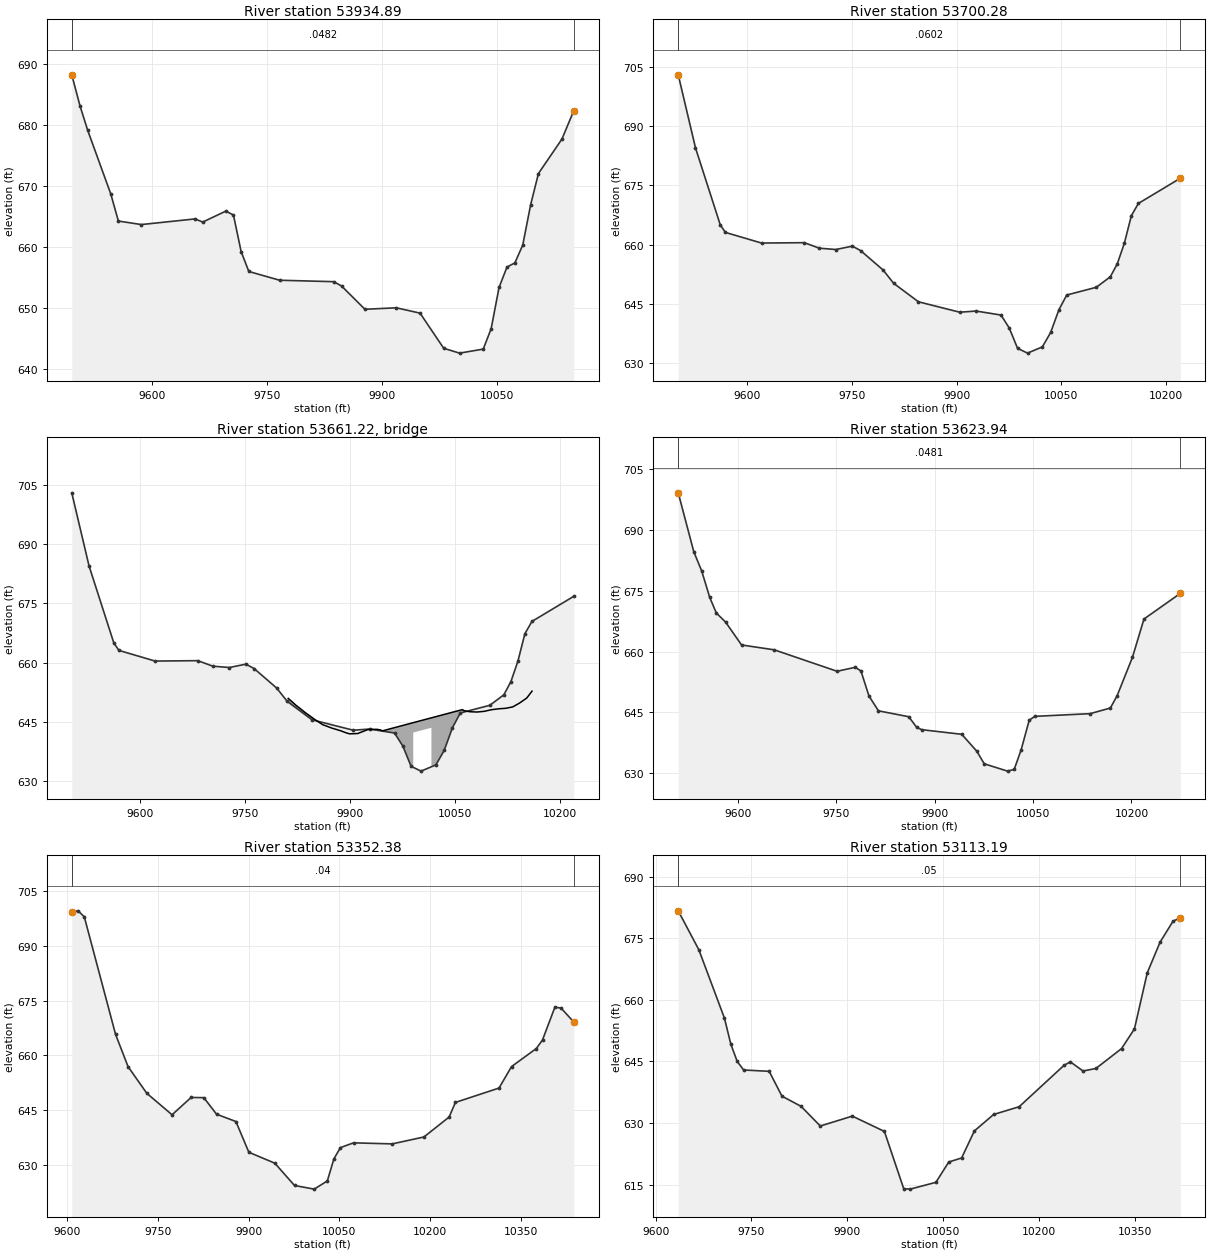
Type RM Length L Ch R = 1 ,53934.89,234.608600,234.608600,234.608600
XS GIS Cut Line= 6
787405.792383642  743480.2565288787232.199573764743480.649465873
787150.360449457743475.034735698787072.429484844743465.144679237
787009.325595772743453.511080933786759.820872257743393.707472858
#Sta/Elev= 30
 9495.51 688.2169506.307683.10269516.312679.10779546.327668.71829556.332664.2437
9586.336663.66939656.344664.59339666.345664.07969696.409665.86719706.433665.2367
9716.456659.2436 9726.48655.97679766.661 654.5419837.288654.30439847.456653.5961
9877.962649.78049918.952650.02159949.847649.14829980.743643.385910001.37642.5917
10032.33643.250810042.65646.609810052.97653.374210063.29656.700610073.61657.3901
10083.86660.307910094.09666.880210104.31 672.03310134.99677.687310150.51 682.366
#Mann= 3 , 0 , 0
 9495.51  0.0482       0 9495.51  0.0482       010150.51  0.0482       0
#XS Ineff= 2 , 0
       0 9797.87                       0
Bank Sta=9495.51,10150.51
Exp/Cntr=0.3,0.1

Type RM Length L Ch R = 1 ,53700.28,76.337000,76.337000,76.337000
XS GIS Cut Line= 4
787425.904314756743480.877693623787049.385217518743244.332554713
786946.556538582743179.342816934786795.192218958 743191.16515801
#Sta/Elev= 30
9501.881702.99979526.569684.51339561.998665.03749569.324663.12869621.046 660.436
9682.112660.53249703.714 659.1369727.334658.80289750.953 659.6549762.763658.5271
  9794.9653.61549810.001650.2511 9845.43 645.5759904.479642.93819928.098643.2291
9963.556642.21859975.386638.92979987.216633.806310001.44632.584810022.71634.1641
10034.54 637.80710046.37643.557210057.59647.290510099.84649.2435 10119.9651.8933
10129.93655.207210139.96660.375710149.99667.346910160.02670.456310220.01676.8279
#Mann= 3 , 0 , 0
9501.881  0.0602       09501.881  0.0602       010220.01  0.0602       0
#XS Ineff= 2 , 0
       09784.595                       0
Bank Sta=9501.881,10220.01
Exp/Cntr=0.3,0.1

Type RM Length L Ch R = 3 ,53661.22,,,
BEGIN DESCRIPTION:
END DESCRIPTION:
Bridge Culvert--1,0,-1,-1, 0
Deck Dist Width WeirC Skew NumUp NumDn MinLoCord MaxHiCord MaxSubmerge Is_Ogee
27.668500,21.000000,2.6,0, 41, 41, , , 0.95, 0, 0,0,,
 9811.43 9815.31 9822.55 9831.28 9835.38 9847.25 9848.20 9861.03 9863.22 9873.86
 9879.19 9886.68 9895.16 9899.51 9911.13 9912.33 9925.16 9927.10 9937.60 9937.97
 9943.52 9946.14 9990.31 9990.3110016.3110016.3110056.6710060.5410063.2410071.26
10081.5410091.8310102.1110102.9010112.3910116.8810122.5310132.5410142.5610152.58
10160.19
  651.00  650.40  649.25  648.04  647.45  645.94  645.80  644.31  644.18  643.47
  643.19  642.78  642.22  642.02  642.10  642.20  643.08  643.11  643.16  643.17
  643.01  642.77  644.85  644.85  646.07  646.07  647.97  648.14  647.88  647.61
  647.54  647.71  648.12  648.14  648.35  648.41  648.48  648.83  649.83  651.07
  652.82
 -349.00 -349.60 -350.75 -351.96 -352.55 -354.06 -354.20 -355.69 -355.82 -356.53
 -356.81 -357.22 -357.78 -357.98 -357.90 -357.80 -356.92 -356.89 -356.84 -356.83
 -356.99 -357.23 -355.15  642.35  643.57 -353.93 -352.03 -351.86 -352.12 -352.39
 -352.46 -352.29 -351.88 -351.86 -351.65 -351.59 -351.52 -351.17 -350.17 -348.93
 -347.18
 9811.43 9815.31 9822.55 9831.28 9835.38 9847.25 9848.20 9861.03 9863.22 9873.86
 9879.19 9886.68 9895.16 9899.51 9911.13 9912.33 9925.16 9927.10 9937.60 9937.97
 9943.52 9946.14 9986.43 9986.4310012.4310012.4310056.6710060.5410063.2410071.26
10081.5410091.8310102.1110102.9010112.3910116.8810122.5310132.5410142.5610152.58
10160.19
  651.00  650.40  649.25  648.04  647.45  645.94  645.80  644.31  644.18  643.47
  643.19  642.78  642.22  642.02  642.10  642.20  643.08  643.11  643.16  643.17
  643.01  642.77  644.66  644.66  645.89  645.89  647.97  648.14  647.88  647.61
  647.54  647.71  648.12  648.14  648.35  648.41  648.48  648.83  649.83  651.07
  652.82
 -349.00 -349.60 -350.75 -351.96 -352.55 -354.06 -354.20 -355.69 -355.82 -356.53
 -356.81 -357.22 -357.78 -357.98 -357.90 -357.80 -356.92 -356.89 -356.84 -356.83
 -356.99 -357.23 -355.34  642.16  643.39 -354.11 -352.03 -351.86 -352.12 -352.39
 -352.46 -352.29 -351.88 -351.86 -351.65 -351.59 -351.52 -351.17 -350.17 -348.93
 -347.18
BR Coef=-1 , 0 , 0 ,, 0 ,,,0.8,0,1,0,
WSPro=,,,, 1 ,,,, 0 ,,,, 0 ,,,,-1 ,-1 ,-1 , 0 , 0 , 0 , 0 , 0
BC Design=,, 0 ,, 0 ,,,,,,

Type RM Length L Ch R = 1 ,53623.94,271.565200,271.565200,271.565200
XS GIS Cut Line= 6
787454.506745302743417.900263047787148.596498127743207.586968114
787138.559549761743202.669271894786984.949163403743117.988074676
786916.372774514743120.592241343786780.956107847743150.974185788
#Sta/Elev= 30
9509.274699.13169532.946684.62989545.082679.83939557.217673.37729567.348669.4971
9581.488667.26539605.758661.62949655.604 660.4299751.382655.14189779.164656.1231
9787.788655.21229799.923649.05379814.467645.3892  9860.6643.93979872.735641.3035
9880.506640.73949941.402639.6054 9964.23635.45689975.644 632.33410011.23630.5271
10021.33 630.95510031.91635.776710044.18643.055910052.59 644.02810137.12644.6954
10167.87646.084110178.12 649.08810201.53658.568310219.11668.0247 10274.5 674.343
#Mann= 3 , 0 , 0
9509.274  0.0481       09509.274  0.0481       0 10274.5  0.0481       0
#XS Ineff= 2 , 0
       09775.225        10055.54       0
Bank Sta=9509.274,10274.5
Exp/Cntr=0.3,0.1

Type RM Length L Ch R = 1 ,53352.38,239.184500,239.184500,239.184500
XS GIS Cut Line= 6
787545.249016313743033.887220857787403.806235173742997.300320444
787315.336181632742968.652099738787028.731461277742855.540518398
786938.937981439742828.962451304786754.273196908742786.106778543
#Sta/Elev= 30
9607.558699.15589618.053699.51059628.293697.86929679.946665.78549700.661656.9429
9731.733649.64559773.452643.78599804.985648.51599826.008648.46179847.036643.9427
9879.115641.94299900.501633.54279943.425630.56219976.029624.463610008.63623.4699
10030.33625.705710041.18631.738410052.02634.814710073.72636.1188 10137.6635.8284
10190.06637.712310231.78643.162710242.21647.1597 10314.4651.0895   10335656.9475
10376.06 661.88910386.28 664.22910406.72673.159710416.94672.957510438.13 669.097
#Mann= 3 , 0 , 0
9607.558    0.04       09607.558    0.04       010438.13    0.04       0
#XS Ineff= 2 , 0
       0                10082.82       0
Bank Sta=9607.558,10438.13
Exp/Cntr=0.3,0.1

Type RM Length L Ch R = 1 ,53113.19,239.184500,239.184500,239.184500
XS GIS Cut Line= 6
787577.189619865742671.416226123787417.384246708742664.665854222
787340.206874219 742666.90728418787059.204460685742692.840699414
786942.996725731742689.255631573786793.521381768742674.348599439
#Sta/Elev= 30
9635.329 681.6699667.598672.18569707.682655.52359717.685649.18779727.687644.9748
 9737.69642.9058  9777.7 642.5819797.706636.53529827.718634.04499857.731629.2583
9907.856631.67019958.086627.94229988.332 613.9979998.415613.887910038.72615.5434
10058.87620.492610078.98621.4788   10099628.067310129.04632.065410169.07633.9561
10239.11644.009810249.13644.890310269.15642.653110289.24643.275210329.44648.1284
10349.54652.900810369.63666.563610389.73674.054210409.83679.098310421.37680.0138
#Mann= 3 , 0 , 0
9635.329    0.05       09635.329    0.05       010421.37    0.05       0
#XS Ineff= 2 , 0
       09948.199                       0
Bank Sta=9635.329,10421.37
Exp/Cntr=0.3,0.1

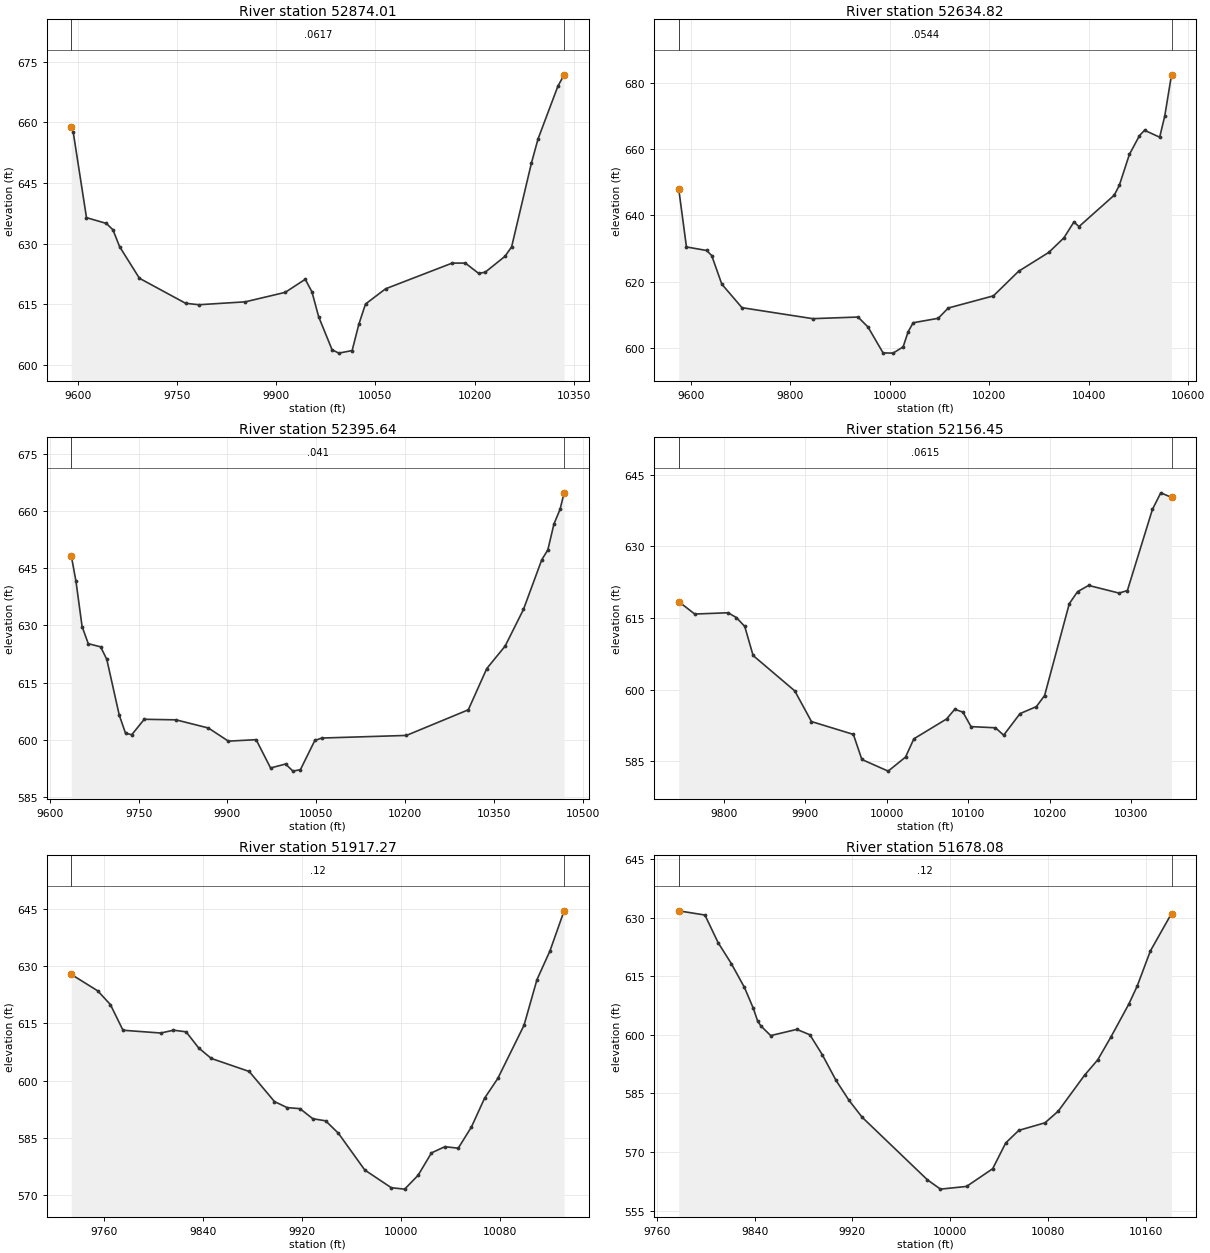
Type RM Length L Ch R = 1 ,52874.01,239.184600,239.184600,239.184600
XS GIS Cut Line= 6
787567.912134849742425.757074337 787384.05287367742420.277622449
787298.859891923742426.212378558787007.631604212  742467.8617818
786938.040465864742471.878057265 786825.58873158742470.627063316
#Sta/Elev= 30
9589.658658.97869592.587657.58329612.645636.41679642.682 634.9849652.695633.4077
9662.707629.24439692.744621.39299762.754 615.1869782.776614.83629852.946615.5514
9913.406617.89969943.749621.13919953.889618.0339 9964.03611.86449984.311603.6932
9994.451602.840110014.71603.472810024.83609.974610034.95615.007410065.31618.7811
10166.02625.144210186.05625.158610206.09622.6152 10216.1622.888210246.12626.8432
10256.12629.178710286.12649.957610296.12655.924710326.15668.992410335.57671.8088
#Mann= 3 , 0 , 0
9589.658  0.0617       09589.658  0.0617       010335.57  0.0617       0
#XS Ineff= 2 , 0
       09922.204                       0
Bank Sta=9589.658,10335.57
Exp/Cntr=0.3,0.1

Type RM Length L Ch R = 1 ,52634.82,239.184500,239.184500,239.184500
XS GIS Cut Line= 6
787570.291450294742278.199111445787546.307540987742273.655007694
787247.284506188 742221.08333166786992.064975951742188.556366327
786716.265870884742146.098345645786591.577778447742123.926847758
#Sta/Elev= 30
9575.429648.02389590.993630.45579631.627629.38699641.781627.86269662.088 619.242
9702.701612.13559844.848 608.8289935.999 609.3159956.164606.29519986.411598.4978
10006.57598.429210026.73 600.32410036.81604.878610046.89607.590810097.29608.9354
10117.45612.033410208.35615.705210258.94623.119710319.65 628.816   10350633.1948
10370.24637.998510380.36636.597410451.22  646.0710461.38648.999310481.69658.3591
10502.01664.036510512.17665.648410542.64663.563510552.79669.903410566.43682.3723
#Mann= 3 , 0 , 0
9575.429  0.0544       09575.429  0.0544       010566.43  0.0544       0
#XS Ineff= 2 , 0
       09840.667                       0
Bank Sta=9575.429,10566.43
Exp/Cntr=0.3,0.1

Type RM Length L Ch R = 1 ,52395.64,239.184500,239.184500,239.184500
XS GIS Cut Line= 6
 787572.48750783742142.006249774787375.219105556742073.580832841
787213.322270402741970.205553476787123.786943218741922.576105474
786988.945508567741876.413950201786808.368328529741829.132922821
#Sta/Elev= 30
9636.189648.20559643.997641.64279654.423629.7022 9664.85625.22239685.704624.3985
9696.131 621.1249717.195606.50769727.745601.79559738.295 601.3889759.395605.4311
 9813.02605.28599867.838603.14549901.497599.70559948.409600.09279972.809592.6816
 9998.07593.715710010.66591.8567 10023.2 592.24610047.53 599.88310059.19600.5192
10202.23601.2036 10306.8 607.91210337.91618.691610368.99624.599710399.93 634.179
10430.86647.184510441.17649.801110451.49656.5767 10461.8660.405910468.64664.7221
#Mann= 3 , 0 , 0
9636.189   0.041       09636.189   0.041       010468.64   0.041       0
#XS Ineff= 2 , 0
       09847.189                       0
Bank Sta=9636.189,10468.64
Exp/Cntr=0.3,0.1

Type RM Length L Ch R = 1 ,52156.45,239.184500,239.184500,239.184500
XS GIS Cut Line= 6
787584.062593523741836.748350402787387.007177756741792.659373859
787312.159725326741765.731599466787169.965653194741756.770594588
787125.451005728741750.943548155786992.147055093741723.557335432
#Sta/Elev= 30
9744.553618.45319764.223615.84569805.184616.11329815.425615.10249825.665613.2489
9835.905607.17699887.107  599.769907.587593.34679959.034590.65979969.479585.4108
10001.76582.973610023.09585.915710033.35589.739810073.52593.889710083.52595.9162
10093.53595.325510103.53592.286710133.57592.0447 10143.6590.492410163.66595.0061
 10183.8596.475910193.89598.797210224.22618.027310234.37620.532610247.96621.8353
10285.29620.229610295.54620.7621 10326.3 637.75110336.55641.210310349.73640.2609
#Mann= 3 , 0 , 0
9744.553  0.0615       09744.553  0.0615       010349.73  0.0615       0
#XS Ineff= 2 , 0
       0                               0
Bank Sta=9744.553,10349.73
Exp/Cntr=0.3,0.1

Type RM Length L Ch R = 1 ,51917.27,239.184500,239.184500,239.184500
XS GIS Cut Line= 6
787575.949942214741621.884421901  787409.3576596741589.267248639
787360.125794244741576.127533805787275.910792636741542.405521166
787231.427046239741526.269388863787194.096669881741514.593477275
#Sta/Elev= 30
9733.726627.86939755.074623.55279765.264619.96889775.454613.22319806.024612.4961
9816.213613.23689826.403612.81159836.593608.56719846.783 605.8219877.353602.4122
9897.732594.52319907.992592.92839918.342592.66029928.692590.01759939.042589.4662
9949.392586.19519970.657576.56319992.105 571.91310002.88571.549810013.69575.1768
10024.51581.059710035.33582.678310046.13582.290310056.77587.8611 10067.4595.4182
10078.04600.573710099.21614.516810109.69626.514910120.17634.040610131.59644.5468
#Mann= 3 , 0 , 0
9733.726    0.12       09733.726    0.12       010131.59    0.12       0
#XS Ineff= 2 , 0
       0                               0
Bank Sta=9733.726,10131.59
Exp/Cntr=0.3,0.1

Type RM Length L Ch R = 1 ,51678.08,239.184500,239.184500,239.184500
XS GIS Cut Line= 6
787614.906326275 741417.79122255787552.532623325741392.680197766
787408.509439541741338.446177739787406.632177969741337.756330661
787345.740782894741314.879075732787238.958725886741271.958396627
#Sta/Elev= 30
9777.865 631.7579799.324630.67819810.104623.61399820.884618.26289831.664612.1405
9838.892606.81559842.444603.55299845.104602.28239853.153599.81239874.524601.4016
9885.209600.01979895.274594.9641 9906.58588.35959917.266583.21639927.951578.9127
9981.379562.88539992.065560.498910013.43561.189710034.79565.726810045.47572.3304
10056.16575.542710077.62577.4854 10088.4580.450910109.96589.656910120.73593.5952
10131.51599.435110146.16607.859210153.07612.510110163.84621.493510181.13631.0637
#Mann= 3 , 0 , 0
9777.865    0.12       09777.865    0.12       010181.13    0.12       0
#XS Ineff= 2 , 0
       0                               0
Bank Sta=9777.865,10181.13
Exp/Cntr=0.3,0.1

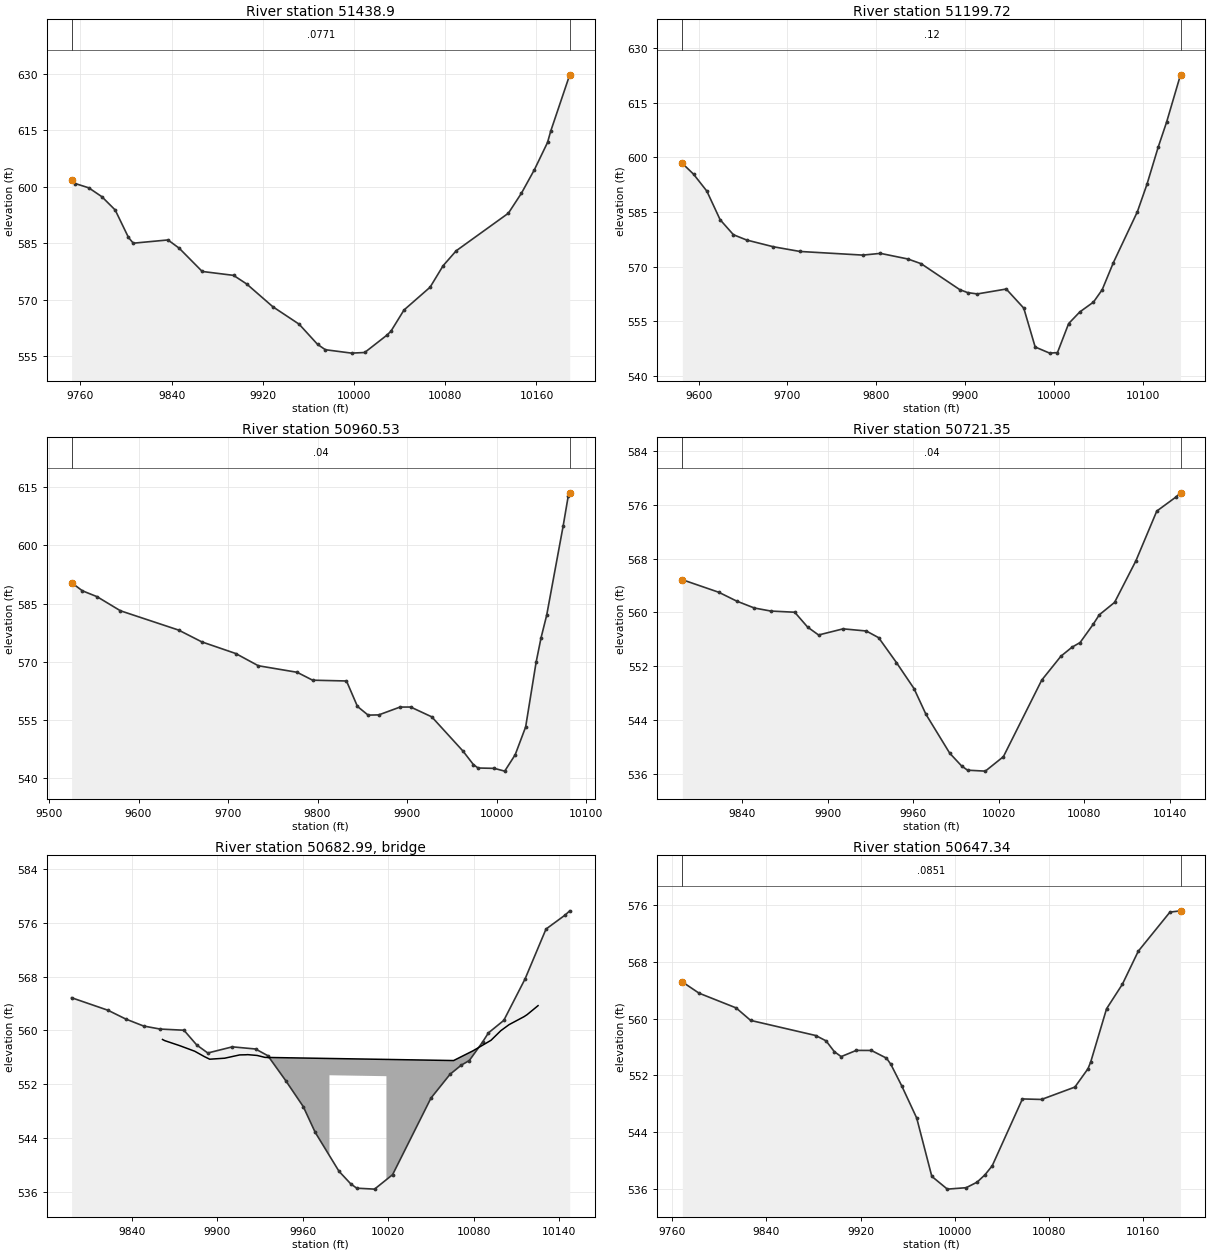
Type RM Length L Ch R = 1 , 51438.9,239.184600,239.184600,239.184600
XS GIS Cut Line= 6
787717.859168511741242.714965153787665.863846711741211.716317569
787503.986794715 741119.67156527787502.256406815741118.668690545
787473.131585581741102.130910516787337.988146965741026.918552537
#Sta/Elev= 30
9752.249601.79199755.578600.85839767.315599.72799778.863597.35419790.505593.8242
9802.147586.52689806.372  584.999836.785585.85449846.603583.66959866.834577.4664
9894.303576.42839905.806574.14139928.813568.0653 9951.82563.43659967.989558.0657
9974.827556.63549997.834555.728610009.34555.897310028.68560.477410032.34561.5528
 10043.8567.203710066.69573.275210078.13579.002610089.58582.966810135.35592.9679
 10146.8 598.29210158.24604.588810169.69611.794910172.54614.863410189.16629.8055
#Mann= 3 , 0 , 0
9752.249  0.0771       09752.249  0.0771       010189.16  0.0771       0
#XS Ineff= 2 , 0
       0                               0
Bank Sta=9752.249,10189.16
Exp/Cntr=0.3,0.1

Type RM Length L Ch R = 1 ,51199.72,239.184500,239.184500,239.184500
XS GIS Cut Line= 6
787956.337652221741193.402693093787813.422616173741065.108069676
787721.949514321740987.128640282787638.946361612740922.646070396
787637.345119953740921.447727729787524.986397155740835.472128941
#Sta/Elev= 30
 9581.64598.33529594.218595.38449609.188590.74759624.158 582.8979639.127578.7808
9654.097577.32299684.036575.48439713.976574.1928 9784.76573.19379804.688 573.667
9835.516572.12929850.463 570.8389893.893563.73389902.693562.91959913.663562.5448
9946.263563.89229966.008558.65339978.863547.99459995.163546.317410003.95546.4612
10016.54554.421110029.14557.620110044.52 560.31710054.32 563.71210066.91 571.138
10093.89585.064610104.69592.588910117.28602.7363 10126.8609.635910142.48622.6202
#Mann= 3 , 0 , 0
 9581.64    0.12       0 9581.64    0.12       010142.48    0.12       0
#XS Ineff= 2 , 0
       0                               0
Bank Sta=9581.64,10142.48
Exp/Cntr=0.3,0.1

Type RM Length L Ch R = 1 ,50960.53,239.184500,239.184500,239.184500
XS GIS Cut Line= 6
788083.051736992741136.120983545787990.089539892741026.245911537
 787940.02685878 740961.25524786787885.741075798740884.577833909
787845.274783972740821.527454977787760.991347111 740683.54711729
#Sta/Elev= 30
9525.176590.3648 9537.22588.28319553.578 586.774 9579.78583.13199644.753578.1628
9670.695575.12099708.564572.1267 9733.81568.97579777.165567.28959794.472565.2548
9832.338  565.059844.591558.48829856.489556.26019868.371556.31229892.136558.3299
9904.019558.34059927.618555.80989962.507546.99059974.137543.51489979.332542.6335
9997.396542.5415 10009.1541.8295 10020.8546.0418 10032.5553.2117 10044.2569.8988
10049.72576.178410056.04582.035310074.46605.0524   10080612.575710081.74613.5164
#Mann= 3 , 0 , 0
9525.176    0.04       09525.176    0.04       010081.74    0.04       0
#XS Ineff= 2 , 0
       0                               0
Bank Sta=9525.176,10081.74
Exp/Cntr=0.3,0.1

Type RM Length L Ch R = 1 ,50721.35,74.005300,74.005300,74.005300
XS GIS Cut Line= 4
 788142.08458007 740815.54015801788040.010217524740678.360332492
788008.760217524740636.693665825787924.029024514740542.623491343
#Sta/Elev= 30
9797.786564.88159823.388563.01069835.853561.70459848.317560.66729859.908560.2128
9876.659560.03929885.711557.82479893.411556.64719910.641557.56299926.914557.2412
 9935.57556.24269948.035552.54669960.417 548.6579968.775544.82819985.476539.0294
9993.792537.13449997.976536.499910010.46  536.3610023.14538.516310050.05549.9249
10063.51553.4845 10071.3554.827210076.97555.520210086.24558.263710090.43559.6514
10101.19561.506510116.13567.693310130.81575.113710144.26577.205710147.46577.8315
#Mann= 3 , 0 , 0
9797.786    0.04       09797.786    0.04       010147.46    0.04       0
#XS Ineff= 2 , 0
       09933.582        10061.73       0
Bank Sta=9797.786,10147.46
Exp/Cntr=0.3,0.1

Type RM Length L Ch R = 3 ,50682.99,,,
BEGIN DESCRIPTION:
END DESCRIPTION:
Bridge Culvert--1,0,-1,-1, 0
Deck Dist Width WeirC Skew NumUp NumDn MinLoCord MaxHiCord MaxSubmerge Is_Ogee
26.002650,22.000000,2.6,0, 27, 27, , , 0.95, 0, 0,0,,
 9861.62 9863.14 9873.68 9884.21 9890.98 9894.74 9905.27 9915.80 9920.14 9921.43
 9928.02 9933.58 9978.80 9978.8010018.8010018.8010066.0710066.4910066.8810079.54
10082.7910092.2110099.0910104.8710115.3910117.5410125.23
  558.66  558.49  557.74  556.91  556.11  555.72  555.87  556.36  556.38  556.40
  556.28  555.99  555.83  555.83  555.69  555.69  555.52  555.58  555.62  556.97
  557.37  558.54  559.97  560.87  562.06  562.36  563.70
 -441.34 -441.51 -442.26 -443.09 -443.89 -444.28 -444.13 -443.64 -443.62 -443.60
 -443.72 -444.01 -444.17  553.33  553.19 -444.31 -444.48 -444.42 -444.38 -443.03
 -442.63 -441.46 -440.03 -439.13 -437.94 -437.64 -436.30
 9861.62 9863.14 9873.68 9884.21 9890.98 9894.74 9905.27 9915.80 9920.14 9921.43
 9928.02 9933.58 9979.39 9979.3910019.3910019.3910066.0710066.4910066.8810079.54
10082.7910092.2110099.0910104.8710115.3910117.5410125.23
  558.66  558.49  557.74  556.91  556.11  555.72  555.87  556.36  556.38  556.40
  556.28  555.99  555.82  555.82  555.68  555.68  555.52  555.58  555.62  556.97
  557.37  558.54  559.97  560.87  562.06  562.36  563.70
 -441.34 -441.51 -442.26 -443.09 -443.89 -444.28 -444.13 -443.64 -443.62 -443.60
 -443.72 -444.01 -444.18  553.32  553.18 -444.32 -444.48 -444.42 -444.38 -443.03
 -442.63 -441.46 -440.03 -439.13 -437.94 -437.64 -436.30
BR Coef=-1 , 0 , 0 ,, 0 ,,,0.8,0,1,0,
WSPro=,,,, 1 ,,,, 0 ,,,, 0 ,,,,-1 ,-1 ,-1 , 0 , 0 , 0 , 0 , 0
BC Design=,, 0 ,, 0 ,,,,,,

Type RM Length L Ch R = 1 ,50647.34,262.513000,262.513000,262.513000
XS GIS Cut Line= 5
 788223.33458007740791.929046899788176.739165633740727.564008365
788151.806802292740698.005435788788029.410968959740545.401269121
 787948.33458007740472.484602454
#Sta/Elev= 30
9768.741565.16029782.954563.57479814.331561.50379826.676559.74019881.918557.6096
9890.723556.8536 9897.75555.32719903.542554.63619916.362  555.519929.181555.5028
    9942554.41669945.699553.54629954.819550.55099967.638545.97239980.457537.7502
9993.647535.951110009.63536.151510018.91536.936310025.61537.976110031.73539.2424
10057.37548.667910073.56548.593910101.88550.3382   10113 552.92110115.33553.8796
10128.78561.381510142.22564.841910155.67569.488910182.57575.006510191.54575.1876
#Mann= 3 , 0 , 0
9768.741  0.0851       09768.741  0.0851       010191.54  0.0851       0
#XS Ineff= 2 , 0
       09931.587        10066.76       0
Bank Sta=9768.741,10191.54
Exp/Cntr=0.3,0.1