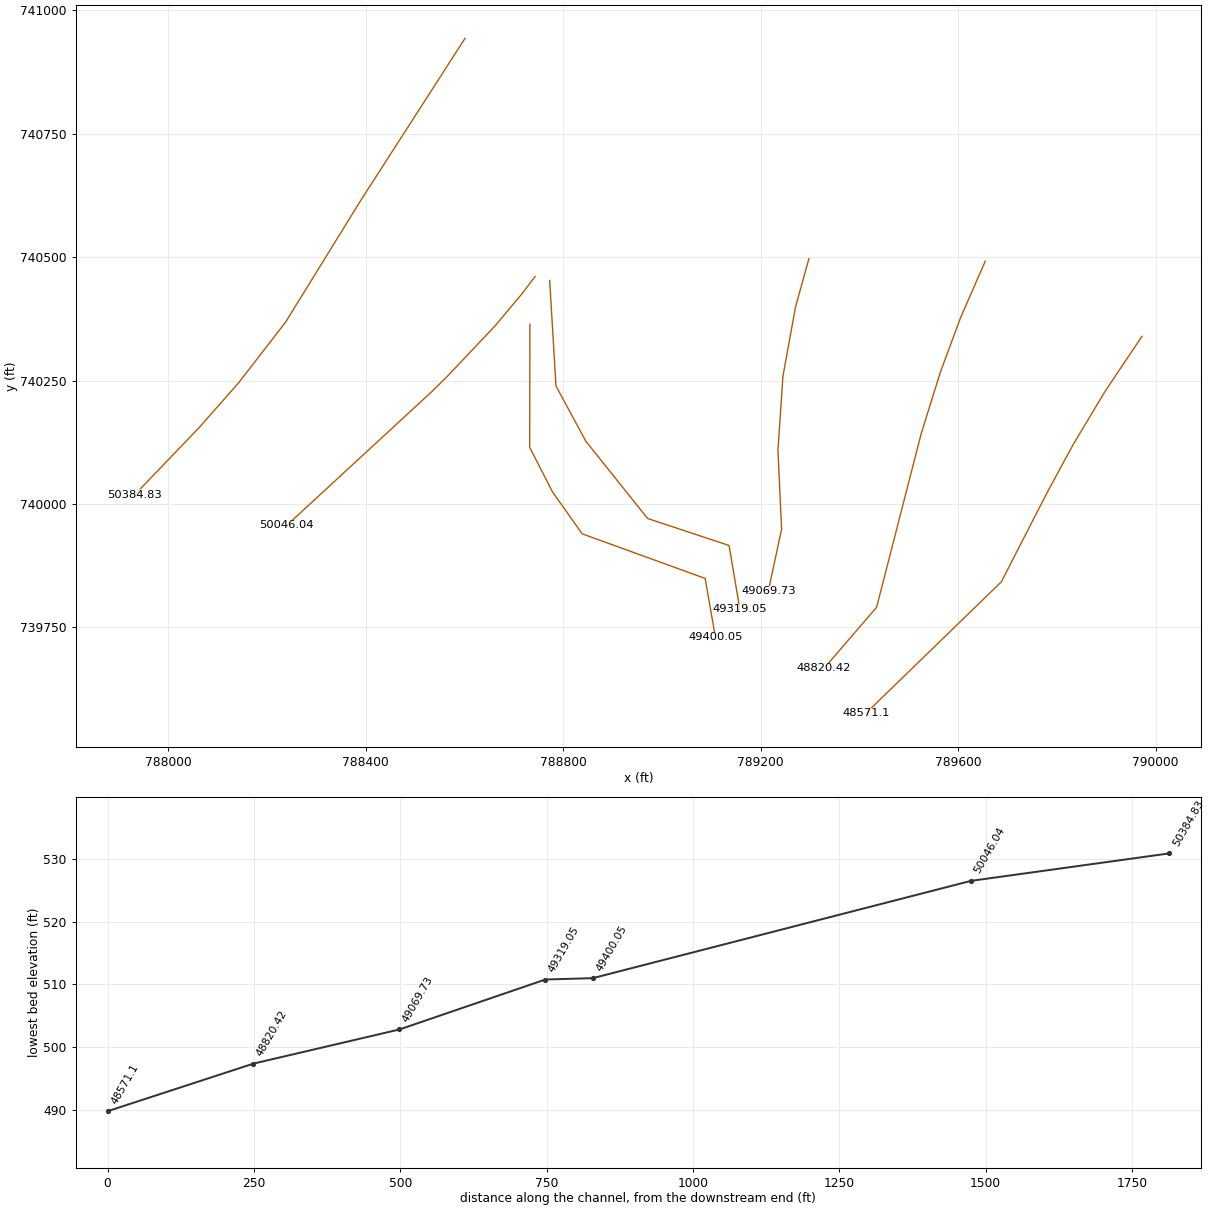
HEC-RAS study 6721_ras.prj: 6721

--- 6721_ras.g01 (geometry) --- (continued)

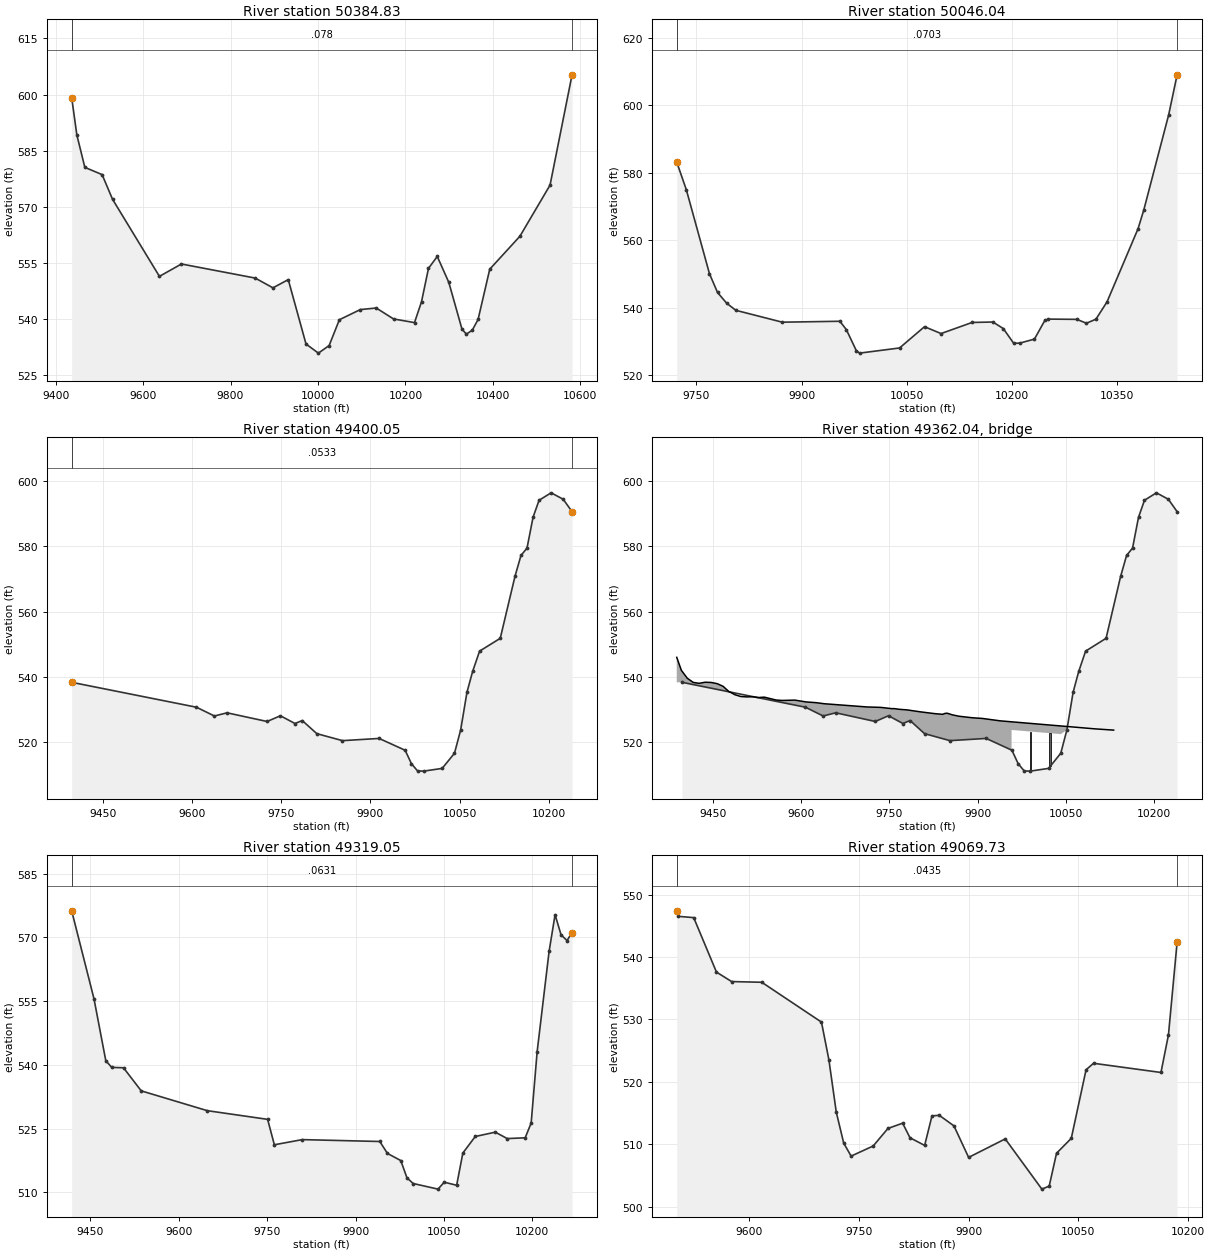
Type RM Length L Ch R = 1 ,50384.83,338.784400,338.784400,338.784400
XS GIS Cut Line= 6
788601.477851724740943.215396512788388.798542986 740612.64484673
 788238.12528831740368.544068279788142.814900282740245.435377483
788064.062781677740156.112975177787932.749410382 740019.07173701
#Sta/Elev= 30
 9436.63599.18339448.459589.20029466.719580.55249506.206578.61879530.109572.0222
9637.347551.43719687.648554.74329856.444550.98319897.024548.37459932.053550.5689
9972.665533.3703   10001530.934310025.54532.959610048.97539.852310096.86542.5672
10133.36542.984610172.84540.066510220.85539.086210236.85544.647210252.85553.5881
10272.93556.754210299.29549.839210329.53537.310610339.59536.020810352.92537.0476
10366.25539.918610392.97553.359510461.94562.149610530.91575.812910581.24605.2703
#Mann= 3 , 0 , 0
 9436.63   0.078       0 9436.63   0.078       010581.24   0.078       0
#XS Ineff= 2 , 0
       0                10281.49       0
Bank Sta=9436.63,10581.24
Exp/Cntr=0.3,0.1

Type RM Length L Ch R = 1 ,50046.04,645.988800,645.988800,645.988800
XS GIS Cut Line= 6
788743.265962885740460.889979635788717.155576428740426.341279777
788662.327972609740360.934843134788566.290181793740259.356049674
788533.055621667740226.720889551788240.446036271739956.747789577
#Sta/Elev= 30
9721.977583.10839735.687574.89089768.638550.04569780.082544.5193 9793.13541.3259
9806.179539.22739872.354535.71089954.505535.98229963.721533.49979977.998527.2397
9982.526526.547310039.56 528.075 10075.1534.3774 10098.7532.340410142.97535.6308
10172.64 535.75810187.42 533.81310202.21529.460810210.85529.509510231.78530.7017
10246.57536.210910251.58536.6245 10292.3536.546210305.88535.395310319.45536.5992
10335.29541.741910379.46563.3847 10387.6568.891510423.13597.131210435.15608.9564
#Mann= 3 , 0 , 0
9721.977  0.0703       09721.977  0.0703       010435.15  0.0703       0
#XS Ineff= 2 , 0
       0                10164.17       0
Bank Sta=9721.977,10435.15
Exp/Cntr=0.3,0.1

Type RM Length L Ch R = 1 ,49400.05,81.005100,81.005100,81.005100
XS GIS Cut Line= 6
788732.887620777 740364.11375691788732.375110418          740115
788778.375600606          740025788838.669441491739939.699623585
789087.785041898739849.376022622 789108.52595675739730.327489644
#Sta/Elev= 30
9397.202538.26449607.258530.61679637.425527.92139658.711528.90119726.094526.2388
9748.555527.99299773.047525.62069785.293526.52669809.785522.50659853.013520.3575
  9914.7521.03559958.504517.40479969.054513.29999979.407511.0551 9989.76511.0024
10020.82511.842610041.53516.481410051.94523.621510062.56535.2191 10072.1541.6022
 10083.8547.8368 10118.6 551.77210143.35570.7692 10153.5577.209510163.65579.4625
 10173.8588.924610183.95594.155610204.25 596.42810224.55594.453610239.45590.6501
#Mann= 3 , 0 , 0
9397.202  0.0533       09397.202  0.0533       010239.45  0.0533       0
#XS Ineff= 2 , 0
       09939.659                       0
Bank Sta=9397.202,10239.45
Exp/Cntr=0.3,0.1

Type RM Length L Ch R = 3 ,49362.04,,,
BEGIN DESCRIPTION:
END DESCRIPTION:
Bridge Culvert--1,0,-1,-1, 0
Deck Dist Width WeirC Skew NumUp NumDn MinLoCord MaxHiCord MaxSubmerge Is_Ogee
26.502550,28.000000,2.6,0, 45, 45, , , 0.95, 0, 0,0,,
 9388.39 9396.19 9406.33 9416.47 9426.39 9436.75 9446.89 9457.03 9467.18 9477.32
 9479.72 9487.35 9497.35 9507.35 9517.35 9527.35 9537.35 9557.35 9567.35 9589.32
 9608.07 9625.68 9639.26 9712.05 9735.25 9755.31 9757.25 9767.50 9779.68 9804.05
 9827.25 9840.61 9844.76 9848.33 9857.12 9868.17 9890.27 9908.49 9937.96 9957.91
 9957.9110055.9110055.9110099.2910131.52
  545.93  541.96  539.51  538.23  537.96  538.29  538.22  537.86  537.04  535.38
  535.21  534.45  533.90  533.79  533.83  533.59  533.71  532.83  532.70  532.80
  532.25  532.01  531.69  530.70  530.57  530.16  530.21  529.97  529.81  529.17
  528.65  528.44  528.72  528.78  528.28  527.86  527.40  527.17  526.45  526.14
  526.14  524.65  524.65  523.98  523.59
 -454.07 -458.04 -460.49 -461.77 -462.04 -461.71 -461.78 -462.14 -462.96 -464.62
 -464.79 -465.55 -466.10 -466.21 -466.17 -466.41 -466.29 -467.17 -467.30 -467.20
 -467.75 -467.99 -468.31 -469.30 -469.43 -469.84 -469.79 -470.03 -470.19 -470.83
 -471.35 -471.56 -471.28 -471.22 -471.72 -472.14 -472.60 -472.83 -473.55 -473.86
  523.64  522.15 -475.35 -476.02 -476.41
 9388.39 9396.19 9406.33 9416.47 9426.39 9436.75 9446.89 9457.03 9467.18 9477.32
 9479.72 9487.35 9497.35 9507.35 9517.35 9527.35 9537.35 9557.35 9567.35 9589.32
 9608.07 9625.68 9639.26 9712.05 9735.25 9755.31 9757.25 9767.50 9779.68 9804.05
 9827.25 9840.61 9844.76 9848.33 9857.12 9868.17 9890.27 9908.49 9937.96 9962.96
 9962.9610060.9610060.9610099.2910131.52
  545.93  541.96  539.51  538.23  537.96  538.29  538.22  537.86  537.04  535.38
  535.21  534.45  533.90  533.79  533.83  533.59  533.71  532.83  532.70  532.80
  532.25  532.01  531.69  530.70  530.57  530.16  530.21  529.97  529.81  529.17
  528.65  528.44  528.72  528.78  528.28  527.86  527.40  527.17  526.45  526.07
  526.07  524.57  524.57  523.98  523.59
 -454.07 -458.04 -460.49 -461.77 -462.04 -461.71 -461.78 -462.14 -462.96 -464.62
 -464.79 -465.55 -466.10 -466.21 -466.17 -466.41 -466.29 -467.17 -467.30 -467.20
 -467.75 -467.99 -468.31 -469.30 -469.43 -469.84 -469.79 -470.03 -470.19 -470.83
 -471.35 -471.56 -471.28 -471.22 -471.72 -472.14 -472.60 -472.83 -473.55 -473.93
  523.57  522.07 -475.43 -476.02 -476.41
Pier Skew, UpSta & Num, DnSta & Num=  ,9990.08, 2 ,9995.12, 2 , 0 , 0 , 0 ,,
    3.00    3.00
 -474.35  525.65
    3.00    3.00
 -474.42  525.58
Pier Skew, UpSta & Num, DnSta & Num=  ,10023.75, 2 ,10028.79, 2 , 0 , 0 , 0 ,,
    3.00    3.00
 -474.86  525.14
    3.00    3.00
 -474.94  525.06
BR Coef=-1 , 0 , 0 ,, 0 ,,,0.8,0,1,0,
WSPro=,,,, 1 ,,,, 0 ,,,, 0 ,,,,-1 ,-1 ,-1 , 0 , 0 , 0 , 0 , 0
BC Design=,, 0 ,, 0 ,,,,,,

Type RM Length L Ch R = 1 ,49319.05,249.316900,249.316900,249.316900
XS GIS Cut Line= 6
788772.883520067740452.787114322788785.667693496740239.117486164
788846.289152712740127.000378802788971.289152712739970.750378802
789136.219708264739916.062878802789158.169789672739786.590500325
#Sta/Elev= 30
9418.345576.23659456.199555.54139476.235540.98479486.253539.41979506.289539.3236
9536.342533.89639648.445 529.2379750.759 527.195 9762.22521.21679809.557522.4296
9941.132521.98689954.098519.18179976.698517.50569987.233513.43659997.768512.1065
10039.91 510.78510050.45512.417610071.52511.692710082.05519.274110103.12523.1636
10137.09524.184610157.38522.672210187.81522.854910197.95526.337510208.09543.0917
10228.38566.702610238.52575.322110248.66570.5941 10258.8569.242210267.33571.1178
#Mann= 3 , 0 , 0
9418.345  0.0631       09418.345  0.0631       010267.33  0.0631       0
#XS Ineff= 2 , 0
       09932.772                       0
Bank Sta=9418.345,10267.33
Exp/Cntr=0.3,0.1

Type RM Length L Ch R = 1 ,49069.73,249.316900,249.316900,249.316900
XS GIS Cut Line= 6
789297.956470937740497.127246425789270.746665776740398.885692507
 789245.30116263740259.005371794789235.204410076740108.821119905
 789242.64902702739949.123460278 789215.59185344739823.446836531
#Sta/Elev= 30
9501.542547.40799503.768546.5244  9524.7546.31749555.773537.58769576.471536.0704
9617.694535.95649699.172529.57249709.294523.54539719.415515.12849729.537510.1827
9739.658508.09269769.839509.71799789.929512.52579810.018513.37089820.063511.0342
9840.086509.80839850.093514.54379860.101514.63029880.116512.93779900.128507.8866
 9950.13510.850410000.16502.801410010.18503.2852 10020.2508.552710040.33 510.941
10060.52 521.93410070.75522.970710162.81521.497710173.04527.534710184.86542.3853
#Mann= 3 , 0 , 0
9501.542  0.0435       09501.542  0.0435       010184.86  0.0435       0
#XS Ineff= 2 , 0
       0                               0
Bank Sta=9501.542,10184.86
Exp/Cntr=0.3,0.1

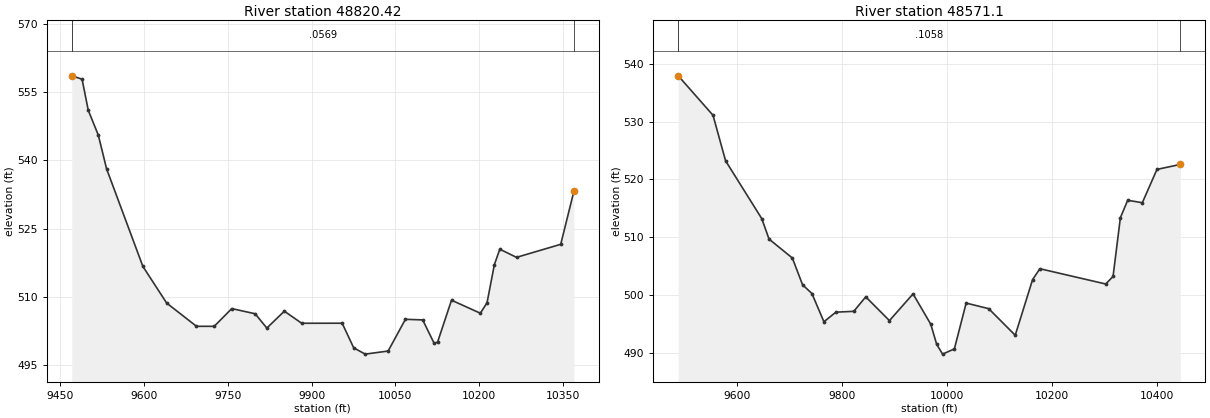
Type RM Length L Ch R = 1 ,48820.42,249.316900,249.316900,249.316900
XS GIS Cut Line= 6
789655.050993919740491.750188813789605.273092598740378.039109096
789563.877507597740266.296340153789525.026745707740141.436397389
 789435.00000003739790.866996646789328.439075649739667.196836531
#Sta/Elev= 30
9470.386558.65059488.863557.91029499.893551.0683 9517.95545.58239532.728538.1671
9597.776516.66159640.433508.58619693.753 503.478 9725.53 503.4729756.948507.3809
 9798.84506.23679819.786503.08629851.129506.81159882.196504.14539954.687504.1576
 9975.36498.73439995.952497.347310037.06498.029710067.98505.019310098.94504.8849
10119.59499.689710125.72500.037410150.55509.226410202.16506.357810214.17508.6498
10227.37 517.08210237.07520.462310266.97518.663310346.17521.537610369.67533.1781
#Mann= 3 , 0 , 0
9470.386  0.0569       09470.386  0.0569       010369.67  0.0569       0
#XS Ineff= 2 , 0
       0                               0
Bank Sta=9470.386,10369.67
Exp/Cntr=0.3,0.1

Type RM Length L Ch R = 1 , 48571.1,283.964500,283.964500,283.964500
XS GIS Cut Line= 6
 789972.52946493740339.656959072789898.544981986740229.510476023
789833.042524874740120.369795635789780.307888269740023.116206378
789687.717847288739842.556777269789413.074492335739576.051003218
#Sta/Elev= 30
9488.349537.92219554.566531.0951 9578.53523.20719647.375513.20469661.303509.6546
9705.673506.38059725.106501.75179742.942500.23099765.826495.34089788.577497.0021
9822.704497.14899845.455499.65689890.593 495.5399935.577500.16659969.315494.9147
9980.561491.43649991.807489.736410014.28490.642310036.71 498.57410079.61497.6087
10130.18493.003510163.22502.636310177.15504.522510302.56501.877910316.49503.1904
10330.43 513.35110344.36516.374610372.23515.9534 10400.1521.717110444.58522.5821
#Mann= 3 , 0 , 0
9488.349  0.1058       09488.349  0.1058       010444.58  0.1058       0
#XS Ineff= 2 , 0
       0                               0
Bank Sta=9488.349,10444.58
Exp/Cntr=0.3,0.1