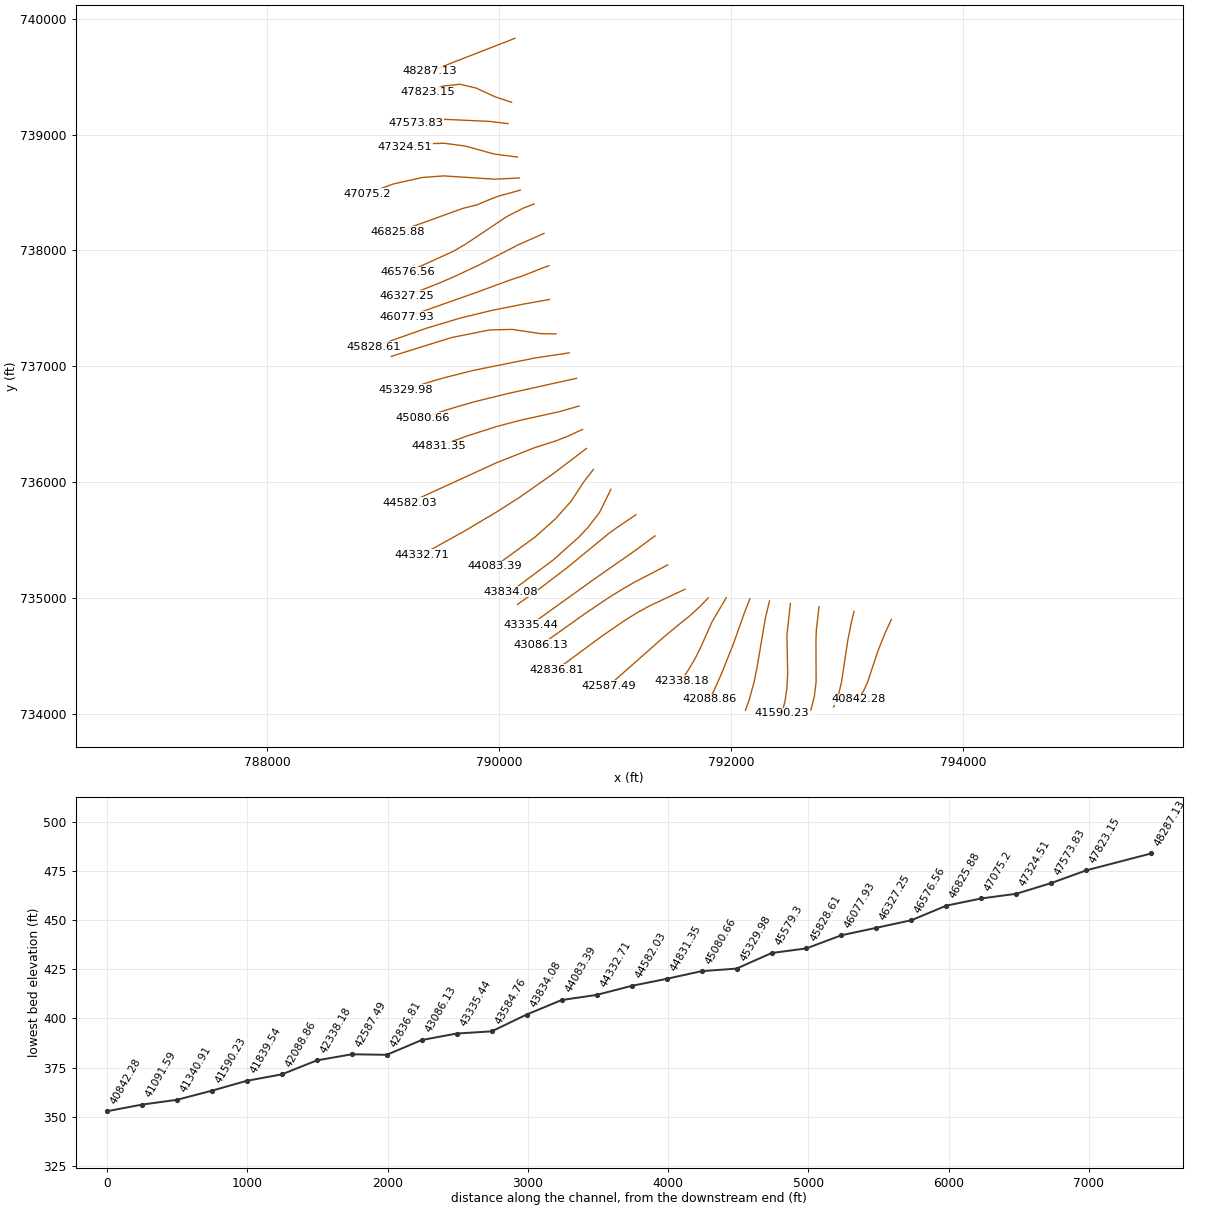
HEC-RAS study 6721_ras.prj: 6721

--- 6721_ras.g01 (geometry) --- (continued)

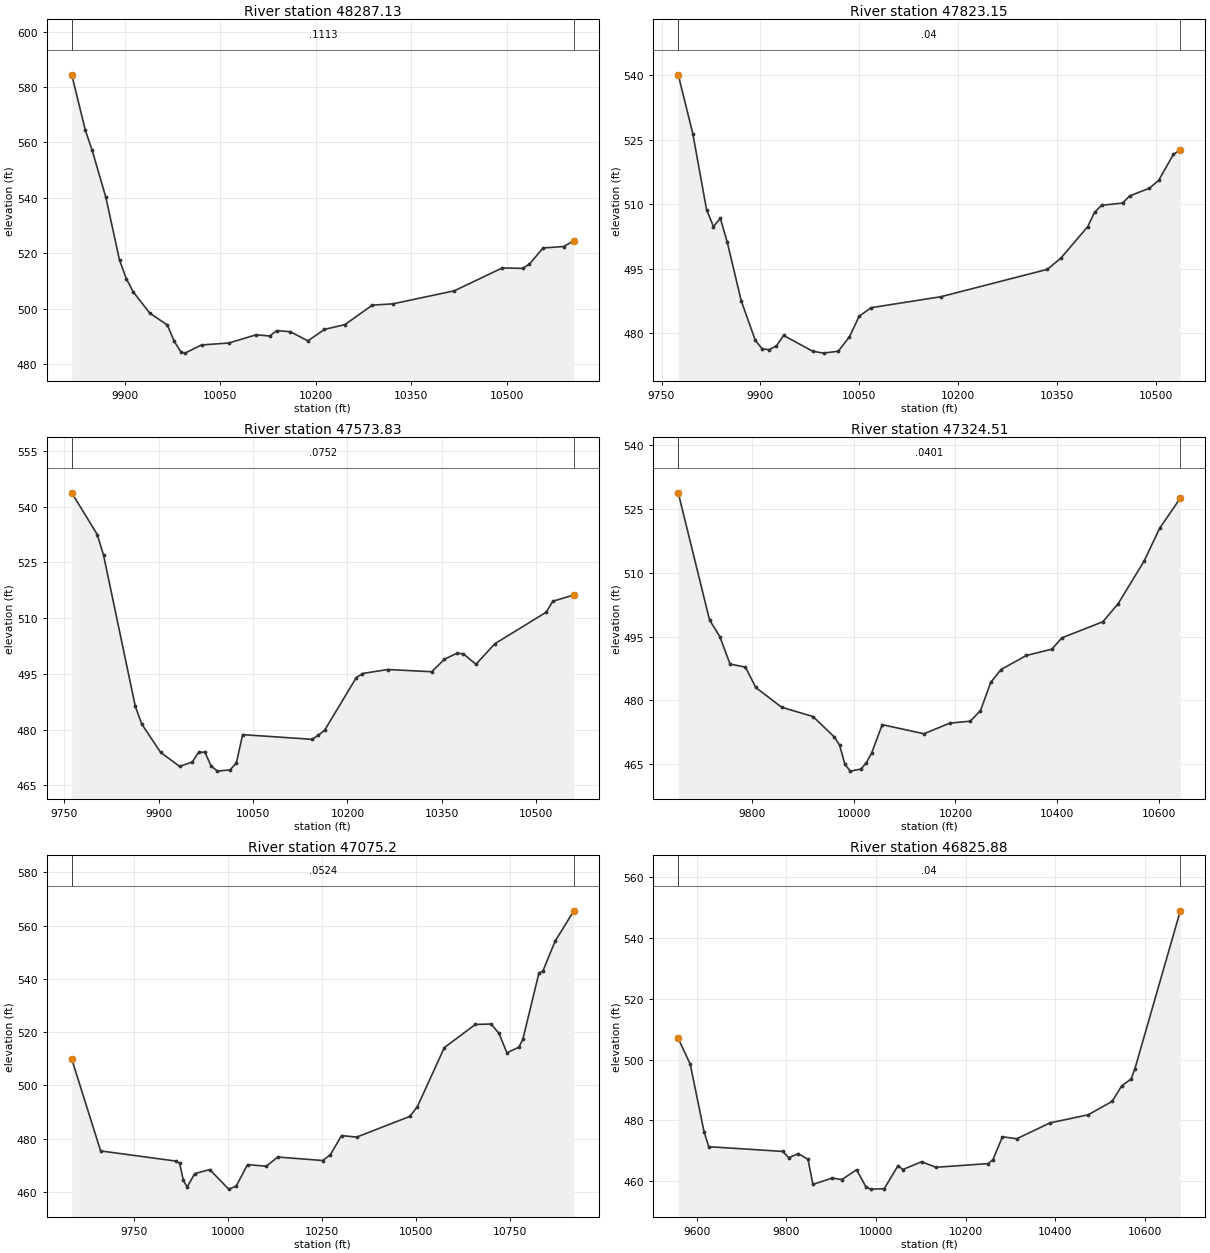
Type RM Length L Ch R = 1 ,48287.13,463.986200,463.986200,463.986200
XS GIS Cut Line= 2
790134.862686753739829.523225427789400.053658962739543.498919874
#Sta/Elev= 30
 9817.03 584.4089838.344564.42199849.075557.12429870.537540.19139891.998517.5369
9902.729510.7953 9913.46506.05869939.772498.30589967.114494.08219977.845 488.224
9988.576484.32959994.908483.917510020.77486.865810063.69487.578110106.62490.5439
10128.08490.098710138.81492.057310160.27491.648910187.88488.335910213.92492.4935
10246.12494.236310289.04501.241210321.23501.713610417.81506.421310492.93514.6643
10525.12514.527910535.85516.089810557.31521.8964 10589.5522.408510605.54524.4547
#Mann= 3 , 0 , 0
 9817.03  0.1113       0 9817.03  0.1113       010605.54  0.1113       0
#XS Ineff= 2 , 0
       0                               0
Bank Sta=9817.03,10605.54
Exp/Cntr=0.3,0.1

Type RM Length L Ch R = 1 ,47823.15,249.316900,249.316900,249.316900
XS GIS Cut Line= 6
790106.361672265739277.729529747789962.432063476739325.839941472
789800.105369659739400.762308006789661.671162477739433.518652435
789512.014966795739417.290029533789385.681582084739363.706362939
#Sta/Elev= 30
9775.347540.14439797.434526.47259818.311508.75779828.807504.77929839.302506.7118
9849.798501.12539870.956487.50479892.367478.27189903.072476.25499913.777476.1035
9924.483477.01369935.371479.41579979.369475.74689995.988475.297310018.31475.7513
10035.32479.114510050.03483.900110068.27485.886210174.26488.445710335.68494.8187
10355.96497.390110397.04504.7592 10407.5508.129410418.03509.7491 10449.9510.2576
10460.73511.935910490.47513.697310504.68515.535510527.02521.5932 10537.6522.6785
#Mann= 3 , 0 , 0
9775.347    0.04       09775.347    0.04       0 10537.6    0.04       0
#XS Ineff= 2 , 0
       0                               0
Bank Sta=9775.347,10537.6
Exp/Cntr=0.3,0.1

Type RM Length L Ch R = 1 ,47573.83,249.316900,249.316900,249.316900
XS GIS Cut Line= 6
790075.100935676739093.852143442789918.463790025739112.973987869
 789538.06490186739130.572345866789475.112110535739128.970170706
789399.301960537739121.392220226789282.703755185739095.417056546
#Sta/Elev= 30
9762.217543.70969802.678532.49749812.768526.87579863.165486.25699873.223  481.55
9903.398 473.8669933.518470.13049953.553471.28279963.571473.86699973.581473.9895
9983.584470.19959993.586468.846610013.59469.1874 10023.6471.0294 10033.6 478.663
10143.76477.404710153.78478.5087 10163.8479.8368 10213.9493.941310223.92495.1053
10263.94496.181810333.97495.588810353.98 498.91510374.01500.560610384.04500.4051
10404.11  497.5910434.33 503.13810515.82511.603410526.09514.527410559.64516.2402
#Mann= 3 , 0 , 0
9762.217  0.0752       09762.217  0.0752       010559.64  0.0752       0
#XS Ineff= 2 , 0
       0                               0
Bank Sta=9762.217,10559.64
Exp/Cntr=0.3,0.1

Type RM Length L Ch R = 1 ,47324.51,249.316800,249.316800,249.316800
XS GIS Cut Line= 6
790156.388468635738805.503534534 789954.07335729738832.059314147
789706.099912169738900.933537681789523.622432599  738924.6234089
 789340.86310665738919.547563812789185.569462271738889.720906858
#Sta/Elev= 30
9654.872528.74759716.469498.87269736.598494.99749756.774488.52849787.038487.8233
9807.318483.0304 9858.16478.38839919.886476.20639961.483471.44089971.999469.5291
9982.524465.02729993.049463.385610014.07463.870510024.56465.343110035.05467.6152
10055.93474.294810138.01472.167310188.72474.656210229.06475.123510249.15477.6023
10269.23484.211810289.32487.233910339.38490.5481 10389.4492.025910409.42 494.706
10489.68498.462410519.96502.742910570.75 512.70610601.45520.439510642.02527.4983
#Mann= 3 , 0 , 0
9654.872  0.0401       09654.872  0.0401       010642.02  0.0401       0
#XS Ineff= 2 , 0
       0                               0
Bank Sta=9654.872,10642.02
Exp/Cntr=0.3,0.1

Type RM Length L Ch R = 1 , 47075.2,249.316900,249.316900,249.316900
XS GIS Cut Line= 6
790171.518612798738625.092761358789960.895909598738614.557004312
789519.605454444738643.132330339789339.291598348738629.822346722
789091.257419736738574.975995874 788858.51548192738490.348726694
#Sta/Elev= 30
9583.152509.86269659.973475.36069860.146471.54939870.158470.71699880.196464.2891
9890.238461.80229910.324466.82949950.496468.356510000.71461.006110020.79462.1276
10050.91470.223110101.04469.615710131.11473.065310251.17471.760610271.19473.8828
10301.21481.133810341.36480.554110482.63488.311810502.91491.950610574.73514.1849
10657.42 522.88710699.26523.042110720.26519.484310741.28512.218110773.11514.3528
10783.73517.302610826.33542.079110837.07542.953210869.27 554.08610919.46565.5772
#Mann= 3 , 0 , 0
9583.152  0.0524       09583.152  0.0524       010919.46  0.0524       0
#XS Ineff= 2 , 0
       0                10144.59       0
Bank Sta=9583.152,10919.46
Exp/Cntr=0.3,0.1

Type RM Length L Ch R = 1 ,46825.88,249.316900,249.316900,249.316900
XS GIS Cut Line= 6
790181.042424147738520.330836256789995.221872734738468.806064133
 789937.76200179738447.978933738789807.220528809 738393.08732131
789690.491618379 738364.36959863789122.197600555738159.470282754
#Sta/Elev= 30
9558.805506.97139585.574498.48749616.465476.19139626.843471.31479792.223469.7609
9805.128467.69439826.671469.05429848.367467.12289859.215458.90589902.608461.0042
9923.706460.48359956.749463.73479977.556458.06589987.778457.350810018.31457.4855
10049.27465.112510059.68463.801110101.82466.362310133.64464.537710250.31465.7569
10260.92467.074810282.13474.583510313.95473.9334 10388.2479.152810473.34481.8227
10526.57486.206410547.86491.283210569.15493.625110577.57496.9504 10678.9 548.956
#Mann= 3 , 0 , 0
9558.805    0.04       09558.805    0.04       0 10678.9    0.04       0
#XS Ineff= 2 , 0
       0                10111.35       0
Bank Sta=9558.805,10678.9
Exp/Cntr=0.3,0.1

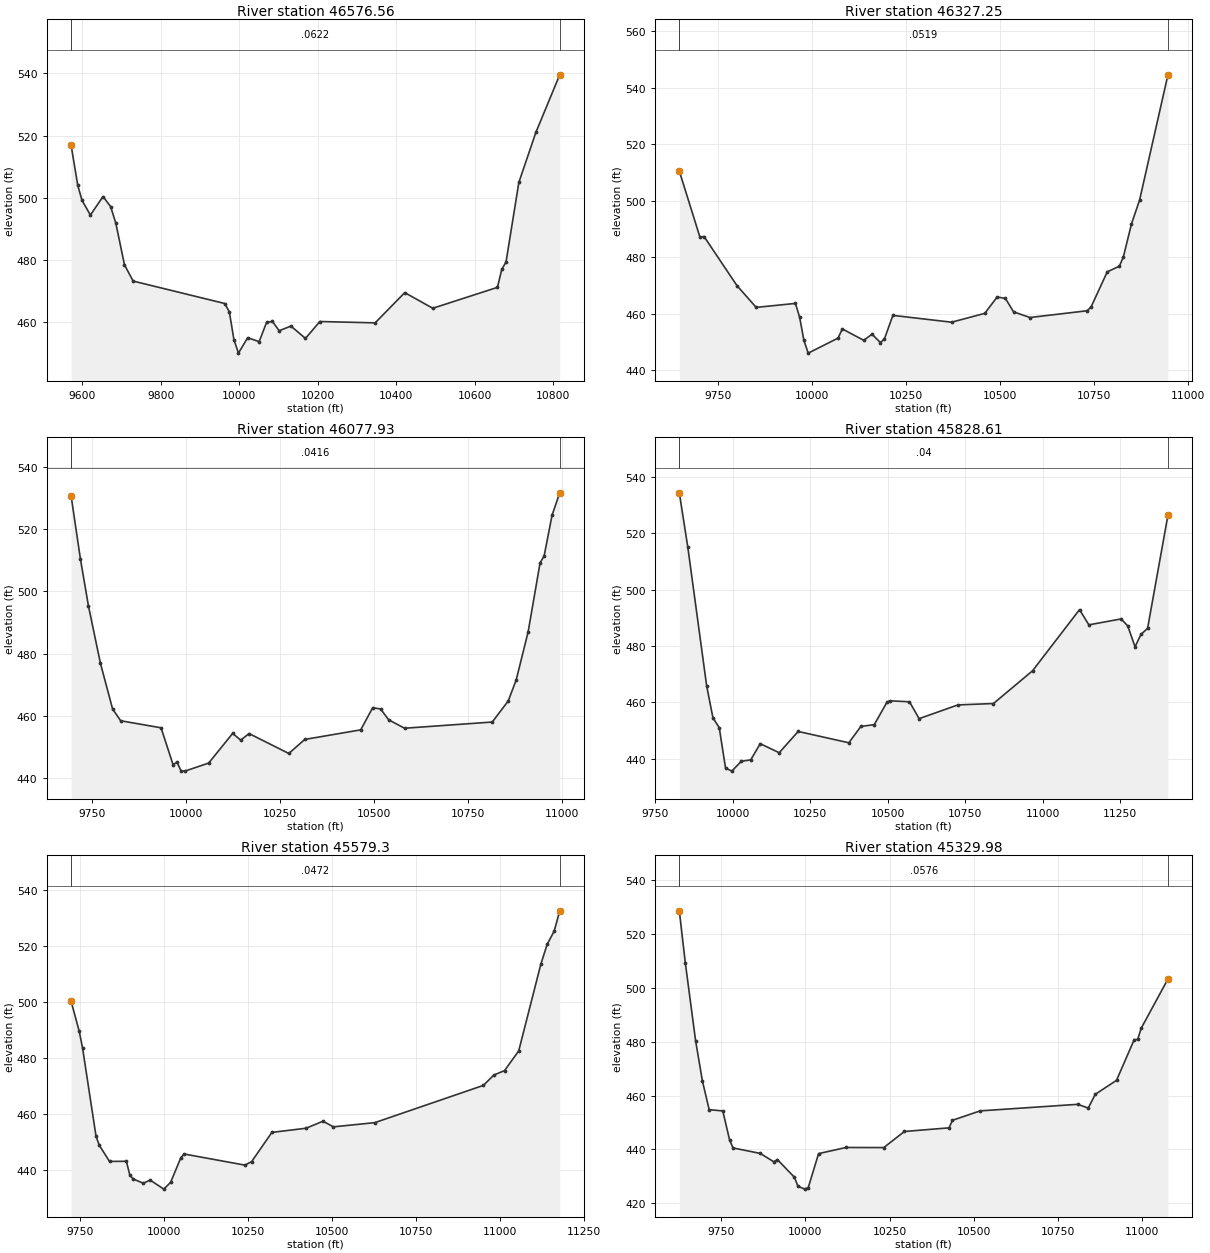
Type RM Length L Ch R = 1 ,46576.56,249.316900,249.316900,249.316900
XS GIS Cut Line= 6
790300.970424374738401.069116679 790209.54101187738366.186003154
790066.613011041738293.235375949789703.706430706738050.681454819
789603.974807607737992.899691405789208.784623403737813.229499146
#Sta/Elev= 30
9571.293516.88549588.319503.93939599.089499.12999620.496 494.4019652.605500.3752
9671.958497.13659685.194491.81399707.259478.38059729.325473.13999962.832465.9088
9974.451463.20599986.071454.2925 9997.69449.932710021.07 454.90310050.33453.6223
10069.42 459.865 10084.3460.133910101.29457.149410131.28458.6428 10168.4454.6697
 10204.9460.111110345.86459.681710421.29 469.42210492.69464.379710657.46471.1168
10668.36476.895710679.27479.275810711.98504.928610755.24520.996710816.02 539.565
#Mann= 3 , 0 , 0
9571.293  0.0622       09571.293  0.0622       010816.02  0.0622       0
#XS Ineff= 2 , 0
       0                10214.33       0
Bank Sta=9571.293,10816.02
Exp/Cntr=0.3,0.1

Type RM Length L Ch R = 1 ,46327.25,249.316900,249.316900,249.316900
XS GIS Cut Line= 6
 790385.71878993 738147.22504804790169.552527729738051.349351008
789825.804958248737875.154853878789613.141630017737774.819430403
789474.863736853737715.800291751789204.751202986 737608.74318292
#Sta/Elev= 30
9647.115510.56469701.975487.13629712.867487.3752 9800.35469.9847 9851.43462.2739
 9955.78463.68669966.955458.79339978.319450.56939989.807446.078710069.22451.4166
10080.42454.651610137.25450.618210159.43452.786910181.61 449.81410192.45451.1353
10214.86459.448510370.94457.0293 10459.1460.155610492.09465.961110513.99 465.454
10535.73460.695610579.23458.692710730.84461.073810741.63462.390610784.74 474.873
10816.95476.846910827.68480.178710849.15491.846910870.63 500.22910946.04544.6311
#Mann= 3 , 0 , 0
9647.115  0.0519       09647.115  0.0519       010946.04  0.0519       0
#XS Ineff= 2 , 0
       0                10219.61       0
Bank Sta=9647.115,10946.04
Exp/Cntr=0.3,0.1

Type RM Length L Ch R = 1 ,46077.93,249.316900,249.316900,249.316900
XS GIS Cut Line= 6
790428.268317295737868.505848248790367.616455439737846.333469094
790194.816172986 737778.45459459790079.786618068737740.286089139
789800.565717313737637.285945189789205.865205984737427.413340805
#Sta/Elev= 30
9694.834530.64949719.608510.40389740.903495.35019772.966476.84099805.198 462.242
9826.686458.45279934.124456.18719965.961 444.3869976.506445.14389987.051  442.41
9997.596442.283310060.77444.873510124.66 454.39410145.98452.234310168.22454.3414
10273.88447.950410316.51452.458210465.21455.530110497.02 462.63510518.23462.2316
10539.43458.760110581.85456.047910815.12458.043110857.54464.789710878.74471.5343
10910.55486.988210942.37509.162310952.97511.278210974.18524.407610994.52531.6078
#Mann= 3 , 0 , 0
9694.834  0.0416       09694.834  0.0416       010994.52  0.0416       0
#XS Ineff= 2 , 0
       0                10160.53       0
Bank Sta=9694.834,10994.52
Exp/Cntr=0.3,0.1

Type RM Length L Ch R = 1 ,45828.61,249.316900,249.316900,249.316900
XS GIS Cut Line= 6
 790431.69547823737576.930179629790208.562422376 737537.44452639
789927.365509777737480.928513354789665.407529953737417.312554138
789372.259282689737329.210889229788913.513707221 737168.06369507
#Sta/Elev= 30
9828.323 534.4089855.512515.26759916.431465.90999936.738454.53839957.044451.0308
9977.351 436.7169997.657435.609710028.09  439.1110058.57439.601610089.17445.3504
10150.37442.142510211.57449.693210374.94445.675510413.74451.475110456.98452.1161
10498.15460.142110508.48460.568610570.46460.225210601.45454.243110726.31459.1078
10841.23 459.61210967.29471.237611118.68492.936111148.81487.541611252.87  489.64
11274.13487.177111297.78479.741511316.81484.152511338.15486.284611403.75526.4554
#Mann= 3 , 0 , 0
9828.323    0.04       09828.323    0.04       011403.75    0.04       0
#XS Ineff= 2 , 0
       0                10221.45       0
Bank Sta=9828.323,11403.75
Exp/Cntr=0.3,0.1

Type RM Length L Ch R = 1 , 45579.3,249.316900,249.316900,249.316900
XS GIS Cut Line= 6
790489.260196195 737280.26720076790354.687404393737282.851120501
790110.525146843737319.238650006789916.125611928737314.139332732
789587.427878584737248.571103903789069.529774759737086.930100132
#Sta/Elev= 30
9724.441500.19429748.716489.45119758.719483.40279798.723452.03939808.724448.7922
9838.769443.09749888.969443.15319899.025438.34829909.081436.83649939.505435.3242
9959.807436.457310000.42 433.22510020.76435.657310051.21444.439710061.29445.7364
10241.73441.7806 10261.8443.023610322.17  453.4510423.55454.9216 10474.4457.4316
10505.15455.419310628.47456.921210951.66470.197410983.06473.909511014.67475.4593
11056.93 482.49811122.92513.465211141.45520.424411162.58525.207211178.93532.4195
#Mann= 3 , 0 , 0
9724.441  0.0472       09724.441  0.0472       011178.93  0.0472       0
#XS Ineff= 2 , 0
       0                10097.44       0
Bank Sta=9724.441,11178.93
Exp/Cntr=0.3,0.1

Type RM Length L Ch R = 1 ,45329.98,249.316900,249.316900,249.316900
XS GIS Cut Line= 6
790602.795686885737116.776094147790311.546959349737073.152261197
789779.181872734736966.181523489789517.563417214736900.225560594
789378.210472056736859.047089512789189.796095822736797.342572758
#Sta/Elev= 30
9625.515528.45459643.491509.02179673.795 480.3719693.998465.4384  9714.2454.7482
9754.605454.29249774.808443.55439784.909440.57619865.845438.54569906.392435.4237
9916.529436.28549967.548429.67759977.757426.36389998.175425.3074 10008.4425.8675
10039.07438.473910120.71440.738910232.69440.707810293.77446.666510426.47448.0257
10436.68450.819710518.76454.304810808.55456.740510839.83455.356410860.69460.4524
10923.79465.627910976.17480.659810986.68480.819110997.19484.966411076.46503.1767
#Mann= 3 , 0 , 0
9625.515  0.0576       09625.515  0.0576       011076.46  0.0576       0
#XS Ineff= 2 , 0
       0                10121.73       0
Bank Sta=9625.515,11076.46
Exp/Cntr=0.3,0.1

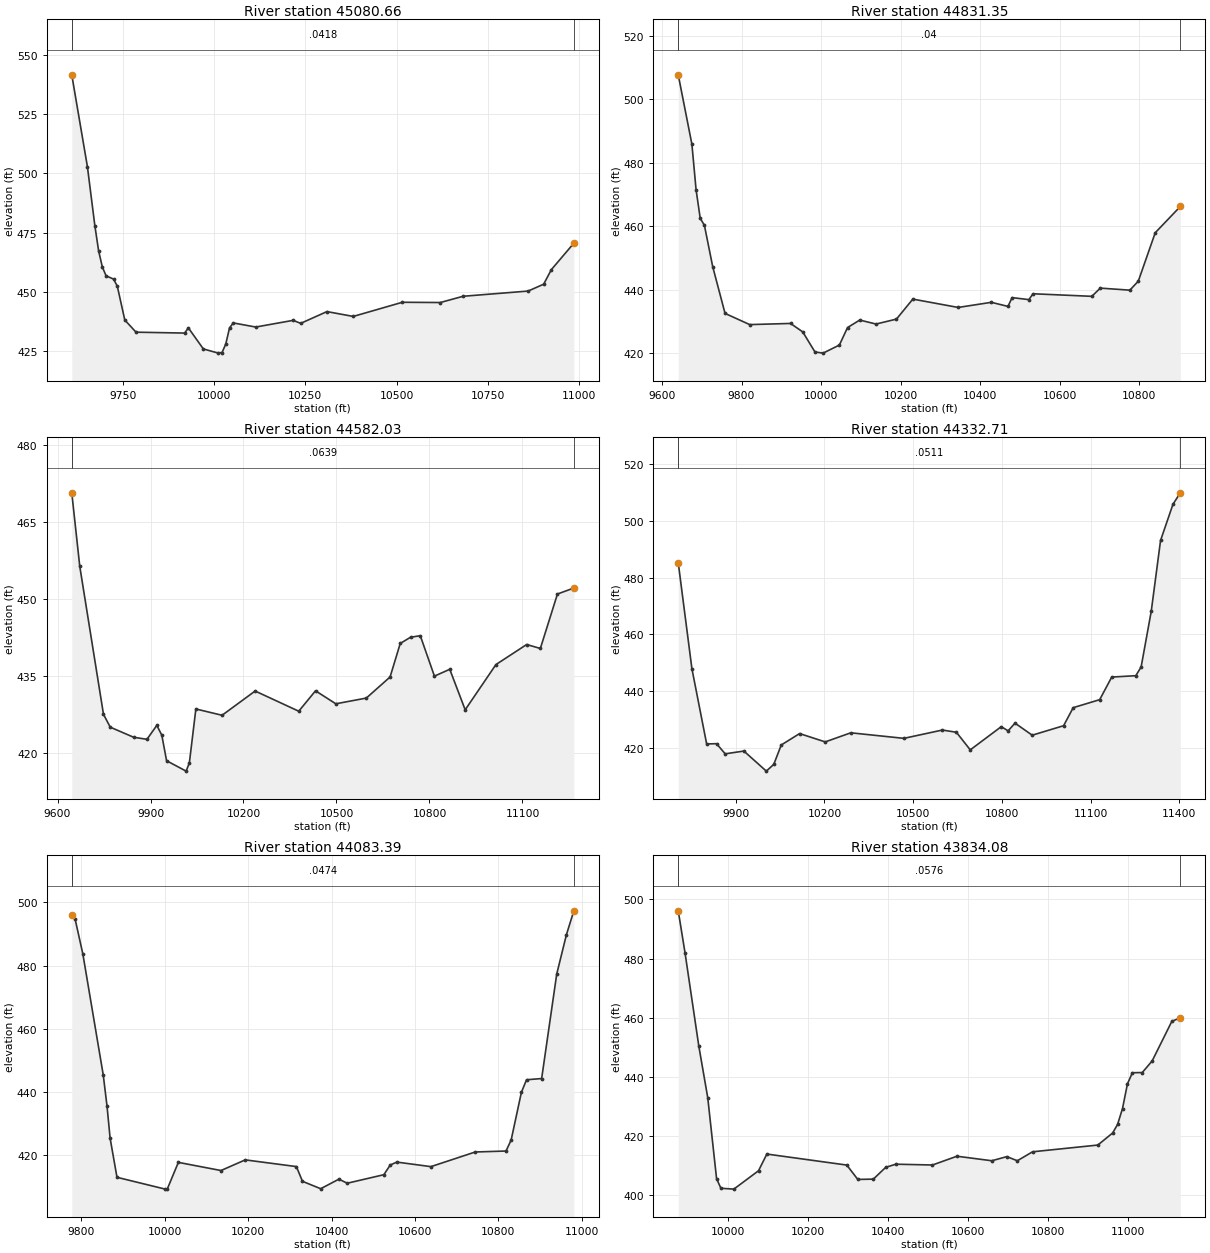
Type RM Length L Ch R = 1 ,45080.66,249.316900,249.316900,249.316900
XS GIS Cut Line= 6
 790666.58888075736897.552906709790070.106582837736765.118028084
789800.533229259736698.670707962789653.312936261 736657.31163794
789531.612131004736620.093064035789336.940348112 736554.71146073
#Sta/Elev= 30
9610.758541.7212 9653.49502.94699673.965477.90119684.203467.29839694.441460.4526
9704.679456.71959725.155455.32069735.392452.32969755.868438.02729786.582432.8765
9919.673432.50149929.911434.68819970.863425.792710011.82424.018310022.07424.2634
10032.32427.884610042.56434.694610052.81436.794810114.29  435.0510216.76437.8831
 10237.3436.605310309.26441.583610381.22439.540810515.56445.523810619.43445.4181
10681.95448.065810859.83450.266210902.39453.175510923.44459.331410984.98470.5185
#Mann= 3 , 0 , 0
9610.758  0.0418       09610.758  0.0418       010984.98  0.0418       0
#XS Ineff= 2 , 0
       0                10069.17       0
Bank Sta=9610.758,10984.98
Exp/Cntr=0.3,0.1

Type RM Length L Ch R = 1 ,44831.35,249.316900,249.316900,249.316900
XS GIS Cut Line= 6
790687.872942026736658.107217254790522.567954938736610.764305802
790177.292547293736534.202959659789978.493260853736481.748982784
789730.179007685736402.805601825789476.073593858736310.356624886
#Sta/Elev= 30
9640.807507.70089675.181485.83719685.638471.54999696.095462.52669706.551460.3644
9727.454447.32489758.509432.59929820.558429.07859923.153429.44469953.836426.7815
9984.519420.467210004.98420.100610045.94422.641510066.41428.143110097.13430.5123
10138.09429.254310189.43430.812310230.65 437.10710344.57434.477610427.97436.0947
10469.77434.807310480.22437.5724 10522.3436.943510532.82438.786310680.63437.9787
10701.86440.563710776.19439.920210797.43 442.74710840.02 457.99810903.07466.2568
#Mann= 3 , 0 , 0
9640.807    0.04       09640.807    0.04       010903.07    0.04       0
#XS Ineff= 2 , 0
       0                10069.59       0
Bank Sta=9640.807,10903.07
Exp/Cntr=0.3,0.1

Type RM Length L Ch R = 1 ,44582.03,249.316900,249.316900,249.316900
XS GIS Cut Line= 6
790717.811954832736455.990581281790582.978468835736394.601182275
790481.115661802736355.068149152 790299.65980904736297.160426046
789976.130137653736169.082806683789227.159120049735826.201631248
#Sta/Elev= 30
 9646.02470.74419671.808456.42359748.331 427.5959770.156425.09289845.651423.1244
9888.558422.72699920.372 425.4429936.487423.53049951.871418.554710014.86416.5277
10025.35418.116410046.34428.638310130.88427.406910237.56432.131910378.24428.2007
10432.34432.175810497.86 429.64510596.29430.759710672.85434.868710705.71441.4075
10738.78442.602410770.31442.912510815.94435.035810865.38436.365310915.15428.4734
11014.35437.287111113.56441.195711157.65440.422311212.77  451.03 11265.7452.1987
#Mann= 3 , 0 , 0
 9646.02  0.0639       0 9646.02  0.0639       0 11265.7  0.0639       0
#XS Ineff= 2 , 0
       0                10068.62       0
Bank Sta=9646.02,11265.7
Exp/Cntr=0.3,0.1

Type RM Length L Ch R = 1 ,44332.71,249.316900,249.316900,249.316900
XS GIS Cut Line= 6
790751.823019638736292.737470147790470.340288665736077.916373039
790172.525095826735869.004382875789968.540980464735739.319723891
789716.493710527735589.403656819789328.572976619735373.192271312
#Sta/Elev= 30
 9705.89485.21459752.094447.94639801.947421.48259835.383421.58019864.526418.0057
9927.745418.986510003.62411.927610028.86 414.31110054.11421.119910116.08425.1332
10202.67422.202810289.12425.402310468.55423.452210598.63426.374610646.03425.5944
10692.92419.402210797.64427.556510820.91426.092210844.18428.797810902.35424.5618
11008.43427.8977 11040.9434.238511130.45437.054411171.13445.004311252.48445.4799
 11270.5448.564611304.62468.099611336.14493.023111378.12505.769111402.91509.7814
#Mann= 3 , 0 , 0
 9705.89  0.0511       0 9705.89  0.0511       011402.91  0.0511       0
#XS Ineff= 2 , 0
       0                10132.48       0
Bank Sta=9705.89,11402.91
Exp/Cntr=0.3,0.1

Type RM Length L Ch R = 1 ,44083.39,249.316900,249.316900,249.316900
XS GIS Cut Line= 6
790812.085409503736111.212539712790733.918392651736011.443027541
790618.525893496735835.999850559790484.360434927735684.943514836
790308.939714155735528.595463492789961.060963819735275.064974867
#Sta/Elev= 30
9776.683495.93049784.796494.64379803.253483.69449852.171445.45729861.269435.5809
9868.671425.43859885.172 413.066   10001409.329110006.13409.449110032.43417.7868
10134.74415.208510192.94418.577110315.66416.455910330.23411.801410373.95409.4571
10417.68412.481810437.66411.194510525.52413.891110540.93416.963610556.68417.8774
10638.42416.438510744.83421.072810818.66421.375210830.97424.858610855.58439.9475
10867.88443.906610904.14 444.29110940.39477.3706 10963.7489.8227 10981.4497.3185
#Mann= 3 , 0 , 0
9776.683  0.0474       09776.683  0.0474       0 10981.4  0.0474       0
#XS Ineff= 2 , 0
       0                10187.93       0
Bank Sta=9776.683,10981.4
Exp/Cntr=0.3,0.1

Type RM Length L Ch R = 1 ,43834.08,249.316900,249.316900,249.316900
XS GIS Cut Line= 6
790963.171594342735939.613025627790865.370759686735741.805603428
790762.518479628735608.028903492790687.489053313735528.831722872
790466.486290629735331.348733946790097.446909739735056.177359288
#Sta/Elev= 30
9875.484496.13549892.574481.84879926.957450.34429949.277432.91849971.396405.4894
9982.187402.243910014.58401.949710076.36408.175610097.17413.819410297.14410.0885
10324.69 405.22710363.59405.338210394.39409.316710419.75410.385710511.43410.1152
10572.69413.083710659.83411.553310697.52412.951310723.69411.549210761.79414.5836
10925.03416.862510962.11 420.94210974.47 423.83210986.84429.2273 10999.2437.5853
11011.56441.339211036.28441.407311061.01445.335111110.14458.710511131.43459.9457
#Mann= 3 , 0 , 0
9875.484  0.0576       09875.484  0.0576       011131.43  0.0576       0
#XS Ineff= 2 , 0
       0                10468.41       0
Bank Sta=9875.484,11131.43
Exp/Cntr=0.3,0.1

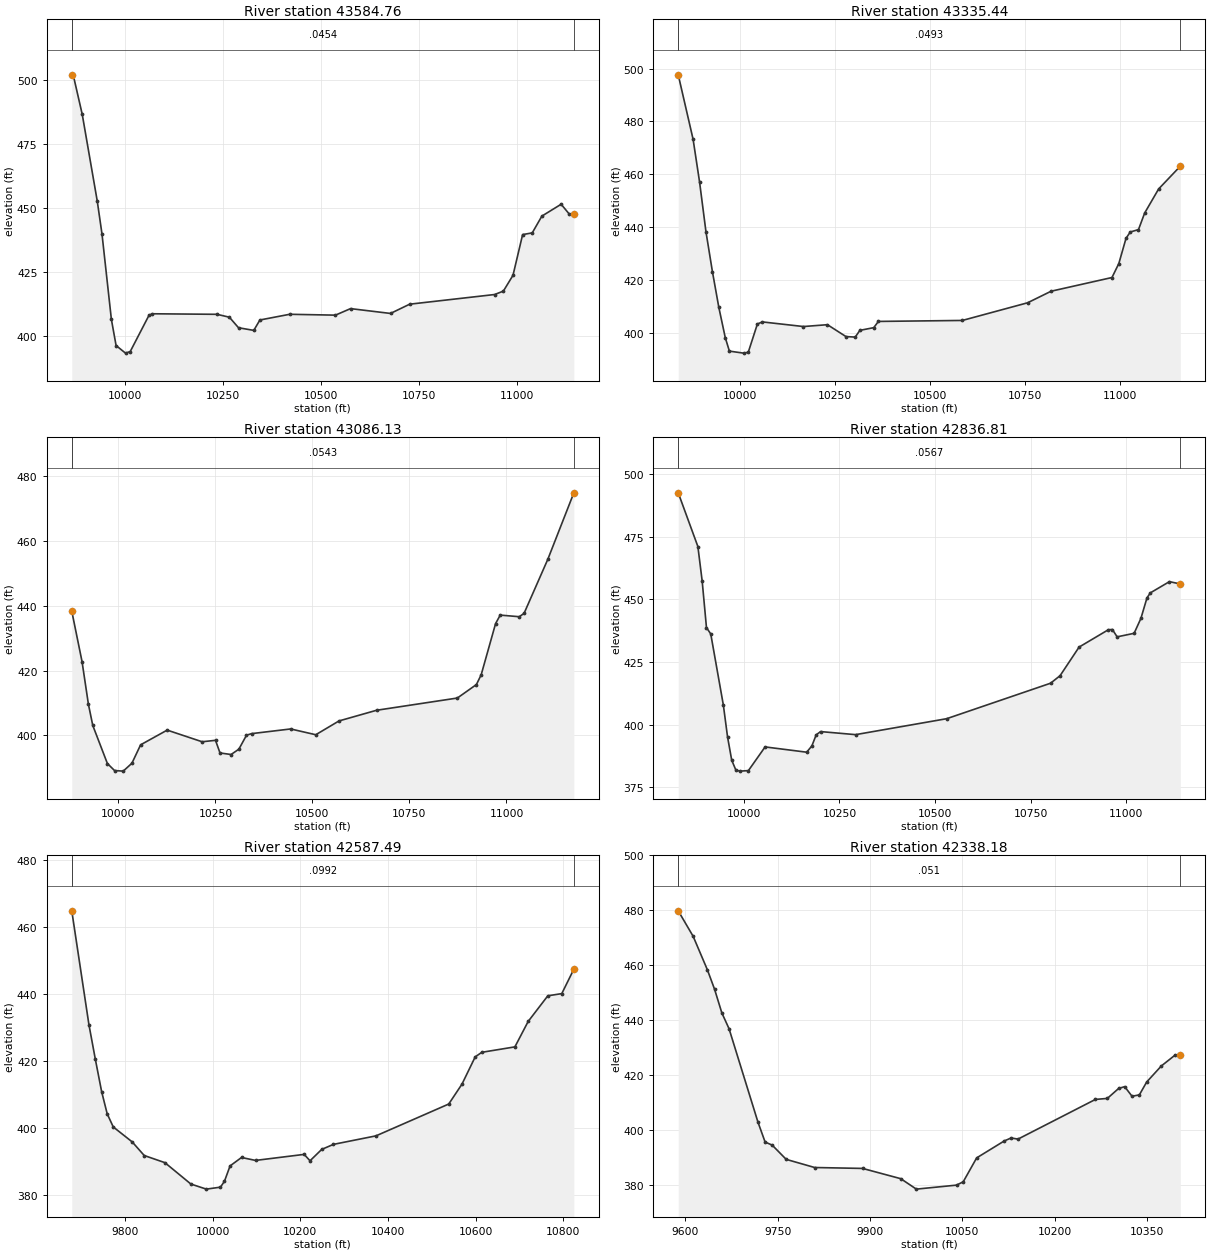
Type RM Length L Ch R = 1 ,43584.76,249.316900,249.316900,249.316900
XS GIS Cut Line= 6
791178.151765424735720.287858302791006.169252939735603.843758064
790939.863626855735555.438275414790585.439312294735263.958791814
 790330.73397811735070.355188924790158.587346783734947.974411987
#Sta/Elev= 30
9865.084 502.0849868.934501.92889891.691   486.79930.025452.80829942.087439.9697
9966.073406.57019978.066396.366710002.05393.400410014.08394.012710062.17408.2393
10070.71408.768610235.36408.556410266.82407.429110290.15403.312910329.09402.2826
10344.66  406.3410420.63408.568510537.16408.233210575.76 410.78410677.58408.8977
10726.45412.512310942.99416.286510965.32417.625610989.86423.796211014.39439.6967
11038.93440.358811063.47446.912911112.55451.543911132.83447.794711144.96447.8079
#Mann= 3 , 0 , 0
9865.084  0.0454       09865.084  0.0454       011144.96  0.0454       0
#XS Ineff= 2 , 0
       0                10553.84       0
Bank Sta=9865.084,11144.96
Exp/Cntr=0.3,0.1

Type RM Length L Ch R = 1 ,43335.44,249.316900,249.316900,249.316900
XS GIS Cut Line= 6
791343.483217779735538.133831814791213.908345437735443.123999894
791142.267390341735390.536183937790825.556146731735170.212323491
790375.861271052734847.421138771 790268.44003964734771.518307236
#Sta/Elev= 30
9838.325497.61119877.447473.18339894.359457.1225 9911.27438.19729928.182423.1532
9945.093409.57489962.005398.15699972.846393.036810010.06392.276910022.47392.5944
10046.52403.310510059.68404.090610167.61402.341910230.72403.038410279.45398.5432
10303.81398.345610315.99400.895510352.54401.919410364.72404.276610585.51404.6477
   10757 411.32510819.03415.710310979.05420.896310997.09426.198411015.98435.7342
11027.23438.134311048.76439.026411065.02 445.31111101.75454.412811158.76463.0309
#Mann= 3 , 0 , 0
9838.325  0.0493       09838.325  0.0493       011158.76  0.0493       0
#XS Ineff= 2 , 0
       0                10504.27       0
Bank Sta=9838.325,11158.76
Exp/Cntr=0.3,0.1

Type RM Length L Ch R = 1 ,43086.13,249.316900,249.316900,249.316900
XS GIS Cut Line= 6
791452.580185049 735287.85255398791164.444415553735137.674372962
791061.591075086735078.492303697790944.072811258735005.586842221
790735.799285688734865.280143316790360.477729719734598.040637466
#Sta/Elev= 30
9879.831438.36129906.328 422.7739922.752409.59729933.968403.08469971.606391.3465
9990.046389.173110012.44388.994110034.83391.427310057.22397.110510125.69401.6506
10215.69398.056410250.25398.497810261.84394.598610290.36394.123210310.41395.7673
10330.08400.067910342.98400.560910443.89402.0069 10508.6400.222510568.54404.4847
10665.28407.772110873.46411.548410922.56415.707910934.83418.713610971.98434.5251
10983.94437.135711033.04436.637611045.32437.6648 11106.7 454.39511173.63474.8654
#Mann= 3 , 0 , 0
9879.831  0.0543       09879.831  0.0543       011173.63  0.0543       0
#XS Ineff= 2 , 0
       0                10384.88       0
Bank Sta=9879.831,11173.63
Exp/Cntr=0.3,0.1

Type RM Length L Ch R = 1 ,42836.81,249.316800,249.316800,249.316800
XS GIS Cut Line= 6
791600.705691923735077.532469646 791294.94263618734934.040655318
791189.428135713734875.802797111791083.290212356734810.056442019
790891.236600898734677.985014201790492.160592538734383.262674629
#Sta/Elev= 30
9828.486492.47679879.828471.05719891.052457.30649902.275438.72889913.499436.1732
9946.438407.80939957.359395.1397 9968.28385.82239979.201 381.8629990.122381.4611
10011.93 381.67110055.54391.118710164.16389.014510177.72391.489110189.14395.9375
10200.56397.235210292.09396.015410530.16402.373310801.76416.525710826.62419.5275
10876.35430.942810952.85437.863410963.37437.9484 10975.8435.027111020.18436.4372
11037.96442.392111053.85450.592311062.82 452.59111112.55457.051811140.94456.1177
#Mann= 3 , 0 , 0
9828.486  0.0567       09828.486  0.0567       011140.94  0.0567       0
#XS Ineff= 2 , 0
       0                10338.84       0
Bank Sta=9828.486,11140.94
Exp/Cntr=0.3,0.1

Type RM Length L Ch R = 1 ,42587.49,249.316900,249.316900,249.316900
XS GIS Cut Line= 6
791802.066695228735003.303215433791736.659180711734935.043073864
791656.447869325734860.234535181791493.813808333734728.422446701
791405.490194514734653.946960939790944.132822889734246.617397321
#Sta/Elev= 30
9679.158464.7445 9718.28430.78019732.734420.58119747.187 410.8419759.907404.1923
 9773.76400.27059816.988395.80359844.336391.75469891.498389.62139950.665383.2458
9985.923381.725610018.11382.314310027.23384.068910040.03388.652310066.18391.1654
10098.05390.289310208.93392.088610222.29390.1833   10249 393.57910275.72395.0771
 10372.6397.612610538.52407.110410568.68413.038510598.85421.179210613.93422.5415
10689.35424.159410719.52431.730610764.38439.392410796.23440.050510823.72447.3407
#Mann= 3 , 0 , 0
9679.158  0.0992       09679.158  0.0992       010823.72  0.0992       0
#XS Ineff= 2 , 0
       0                               0
Bank Sta=9679.158,10823.72
Exp/Cntr=0.3,0.1

Type RM Length L Ch R = 1 ,42338.18,249.316900,249.316900,249.316900
XS GIS Cut Line= 6
791957.699015569735005.351009115791835.543100876734797.497195036
791734.346173215734570.181892728791689.728502688734482.255587992
791638.875764277734394.665632496791570.565826363734289.174307361
#Sta/Elev= 30
9588.575479.83849612.847470.54589635.923458.39149647.657451.27549659.391442.7249
9671.125436.95719718.062 403.0019729.707395.73819741.138394.63369763.998389.4374
9810.202386.47849888.024386.14819950.067382.4166 9975.37378.618410040.65380.0741
10051.56 381.29610073.36  389.9810118.06396.124410129.28397.222710140.49396.8103
10266.29411.245310285.63411.609410304.05415.247410313.82415.886810325.73412.4042
10337.63412.889110349.54417.580510373.36423.416510396.14427.447310404.17427.3738
#Mann= 3 , 0 , 0
9588.575   0.051       09588.575   0.051       010404.17   0.051       0
#XS Ineff= 2 , 0
       0                               0
Bank Sta=9588.575,10404.17
Exp/Cntr=0.3,0.1

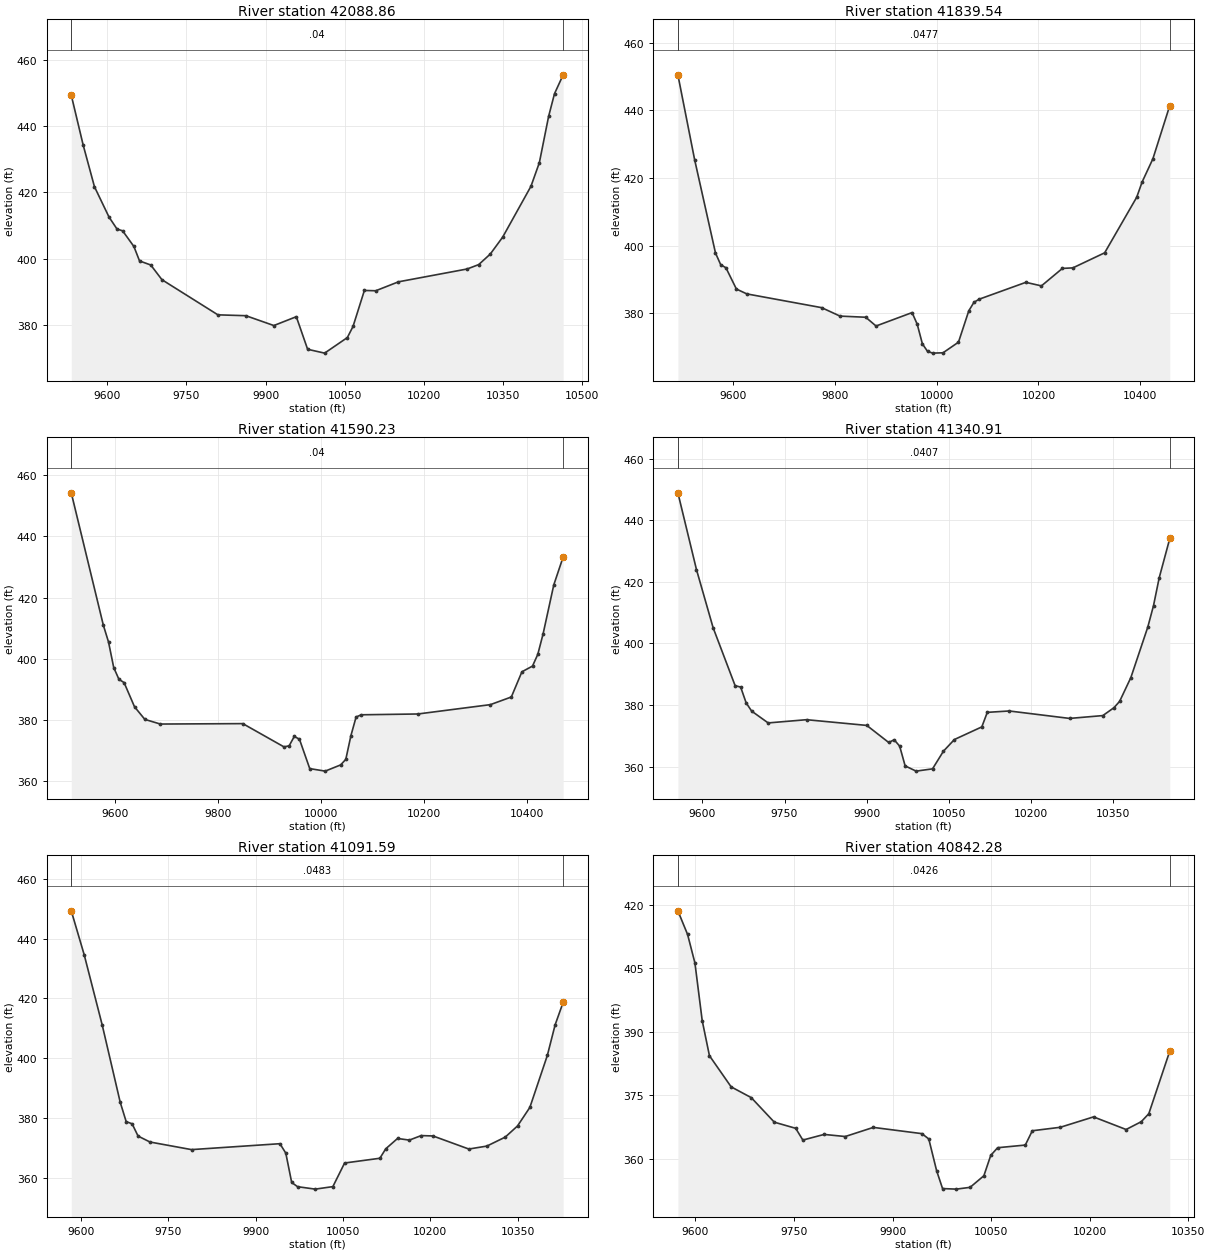
Type RM Length L Ch R = 1 ,42088.86,249.316900,249.316900,249.316900
XS GIS Cut Line= 6
 792161.11701014734995.814864208792111.767650001734867.499371468
792019.472061963734607.442280144791918.778343012734354.343224114
791854.796847143734210.584694474791814.468295163734130.512755746
#Sta/Elev= 30
9531.619449.35049554.165434.32049575.614421.71399603.176412.58259618.355408.9572
 9629.04408.40799650.411403.68589661.096399.32679682.374398.10499703.596 393.666
9809.707383.06619862.763382.80439915.818379.83779958.405382.50459979.856 372.673
10012.09371.514710055.17376.206810065.95379.560810087.49390.423410109.03390.3302
10152.12393.028710282.41 396.902 10304.3398.223810326.19401.394110349.72406.5028
10403.38421.8505 10419.3 428.96710436.88  442.9510448.04449.791610464.47455.4781
#Mann= 3 , 0 , 0
9531.619    0.04       09531.619    0.04       010464.47    0.04       0
#XS Ineff= 2 , 0
       0                               0
Bank Sta=9531.619,10464.47
Exp/Cntr=0.3,0.1

Type RM Length L Ch R = 1 ,41839.54,249.316900,249.316900,249.316900
XS GIS Cut Line= 6
792330.672554451734976.698307747792296.498389409 734835.77704724
792223.465582146734405.632365227792197.382627599734276.844417627
792156.067270199734125.905428162792123.290448018734033.855994115
#Sta/Elev= 30
9491.098 450.5449523.943425.49979565.027397.85619575.298394.38869585.569393.4919
 9606.11387.20319626.652385.76399773.679381.69959809.751379.20289860.377378.8603
9880.628376.26979951.505380.2389 9961.63376.77499971.756370.99829981.881368.7657
9992.006368.251810012.28368.349510042.69 371.48810062.97380.764410073.11383.2763
10083.31384.194810175.14389.183910205.77388.135910246.98393.302710267.59393.4623
10330.07397.9145 10393.1414.353910403.68418.849210424.85 425.70310458.11441.4698
#Mann= 3 , 0 , 0
9491.098  0.0477       09491.098  0.0477       010458.11  0.0477       0
#XS Ineff= 2 , 0
       0                               0
Bank Sta=9491.098,10458.11
Exp/Cntr=0.3,0.1

Type RM Length L Ch R = 1 ,41590.23,249.316900,249.316900,249.316900
XS GIS Cut Line= 6
792510.939244811734956.374122075792480.711104395734679.517406158
792487.243251907734357.185985172792480.892588843734225.157095712
792464.066106195734111.410579322792437.374793823734007.510126548
#Sta/Elev= 30
9515.364454.23859577.673410.9598 9587.77405.44549597.867397.08919607.964393.2559
9618.061392.15549638.244384.26849658.328380.13269688.455 378.6159848.692378.7529
9928.723371.14319938.729371.50139948.734374.5597 9958.74373.65659978.751364.0389
10008.77363.215110038.79365.2511 10048.8367.0633 10058.8374.8549 10068.8380.9108
10078.81381.641510188.84381.905210329.78384.962710370.45387.462810391.02395.7066
10411.58397.572810421.86401.406610432.14408.084810452.91424.112810471.17433.2801
#Mann= 3 , 0 , 0
9515.364    0.04       09515.364    0.04       010471.17    0.04       0
#XS Ineff= 2 , 0
       09738.185                       0
Bank Sta=9515.364,10471.17
Exp/Cntr=0.3,0.1

Type RM Length L Ch R = 1 ,41340.91,249.316900,249.316900,249.316900
XS GIS Cut Line= 6
792758.040246937734928.514695372 792734.63756508734726.603342515
792731.332124869734637.704745542792732.678234751734279.540444814
792717.812718571734155.438547801792687.359790715734036.601842087
#Sta/Elev= 30
9555.241448.86819589.168423.9696 9619.53405.12539659.809386.27749669.879385.8419
9679.949380.69549689.989 378.0389720.085374.2044 9790.23375.25239900.269373.3961
9940.274367.85859950.277368.7373 9960.28366.66879970.284360.26539990.291358.5629
 10020.3359.3017 10040.3365.050510060.31368.824810110.32372.917610120.33377.6356
10160.34378.081410270.63375.666210331.31376.585210351.79379.162710362.04 381.215
10382.52388.916310413.46405.312710423.87 412.25110434.28421.293210453.63434.0615
#Mann= 3 , 0 , 0
9555.241  0.0407       09555.241  0.0407       010453.63  0.0407       0
#XS Ineff= 2 , 0
       0  9806.1        10153.15       0
Bank Sta=9555.241,10453.63
Exp/Cntr=0.3,0.1

Type RM Length L Ch R = 1 ,41091.59,249.316900,249.316900,249.316900
XS GIS Cut Line= 6
793060.192400217734886.432332008793038.194845312734800.429299792
 793005.87382447734636.984548392792951.165265997 734273.85849693
 792928.81341478734181.487757537792883.669160686734062.419646858
#Sta/Elev= 30
9583.172 449.299 9605.42434.57159636.343411.07939667.244385.23779677.506378.7426
9687.737 377.9939697.967373.88659718.429371.89989789.776369.35379941.677371.3355
9951.785368.17549961.894358.35759972.003356.943810002.33356.126310032.63356.9631
10052.82364.869310113.41366.459910123.51  369.6310143.78373.084410164.08372.5387
10184.38374.052310204.67373.927910266.24369.548710297.26370.537810328.81  373.54
10349.89377.271110371.13383.490610401.12400.864910414.52411.123910428.35418.6829
#Mann= 3 , 0 , 0
9583.172  0.0483       09583.172  0.0483       010428.35  0.0483       0
#XS Ineff= 2 , 0
       09791.285        10149.18       0
Bank Sta=9583.172,10428.35
Exp/Cntr=0.3,0.1

Type RM Length L Ch R = 1 ,40842.28,249.316900,249.316900,249.316900
XS GIS Cut Line= 6
793382.540641857734818.244403393793331.330971283734709.231605625
793265.730782903 734545.94526861793175.983020697734275.403494943
793146.613957622734210.319766947793097.475910629734128.296391101
#Sta/Elev= 30
9573.345418.61979588.123413.0218 9599.28406.27249610.351392.64259621.364384.3341
9654.403376.95739685.037374.40679720.101368.59749752.669 367.1449763.525364.3647
9795.897365.70039828.001365.20439870.793367.36239944.709365.88589955.186364.6258
9967.066357.13659976.142352.88389997.097352.753710018.05353.177510039.01355.9144
10049.48360.740510059.96 362.55410102.09 363.18310112.74366.569710155.33367.3913
 10205.9369.851110255.46366.865310278.51368.708610290.03370.603110321.97385.4334
#Mann= 3 , 0 , 0
9573.345  0.0426       09573.345  0.0426       010321.97  0.0426       0
#XS Ineff= 2 , 0
       09842.299        10163.15       0
Bank Sta=9573.345,10321.97
Exp/Cntr=0.3,0.1