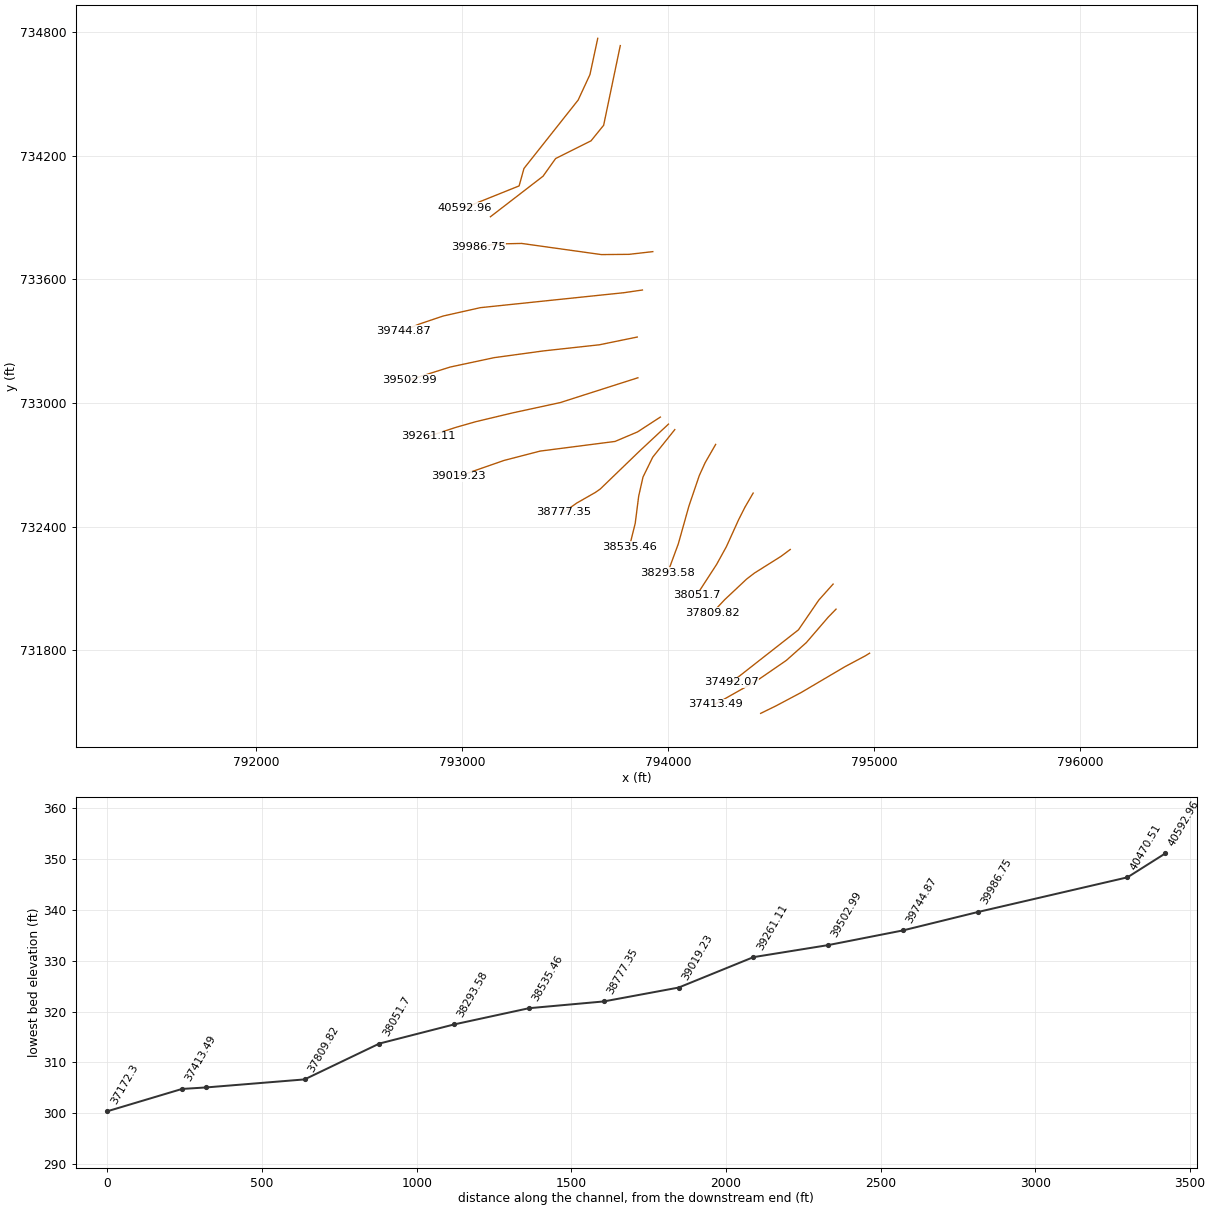
HEC-RAS study 6721_ras.prj: 6721

--- 6721_ras.g01 (geometry) --- (continued)

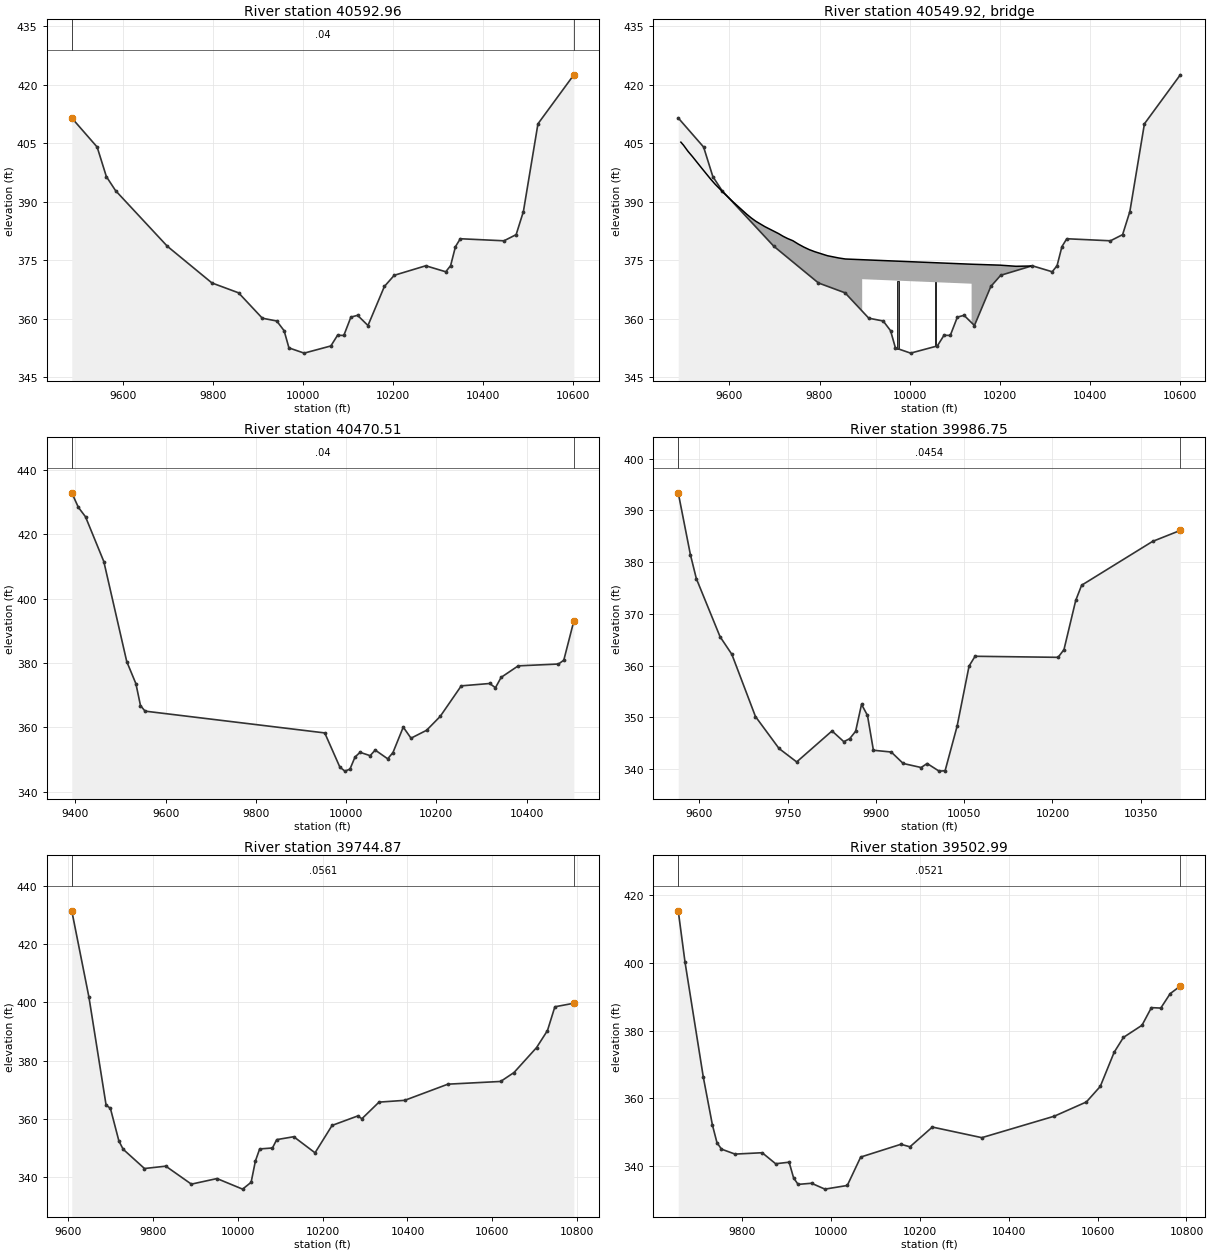
Type RM Length L Ch R = 1 ,40592.96,122.447900,122.447900,122.447900
XS GIS Cut Line= 6
793658.181513821734770.116698232793620.421097154734594.335448232
793563.129430488734470.637531566793300.108597154734138.606281566
793276.671097154734053.970864899793011.046097154733947.200031566
#Sta/Elev= 30
9486.265 411.4939542.639404.02459563.095 396.4529583.551392.84339698.385378.5826
 9797.57369.15129856.718366.62089909.464360.10929941.516359.38879957.864356.8989
9968.598352.490310002.36351.145910061.68352.987510076.51355.728710090.47355.6847
10106.17360.3833   10121  360.8510144.11358.229310180.53 368.25110202.44371.1188
10272.48373.561410316.85372.022210327.63373.591410338.41378.474610349.19380.4969
10446.19379.971210473.17381.5512 10489.3387.485810521.63409.991610601.33422.5597
#Mann= 3 , 0 , 0
9486.265    0.04       09486.265    0.04       010601.33    0.04       0
#XS Ineff= 2 , 0
       0                10223.23       0
Bank Sta=9486.265,10601.33
Exp/Cntr=0.3,0.1

Type RM Length L Ch R = 3 ,40549.92,,,
BEGIN DESCRIPTION:
END DESCRIPTION:
Bridge Culvert--1,0,-1,-1, 0
Deck Dist Width WeirC Skew NumUp NumDn MinLoCord MaxHiCord MaxSubmerge Is_Ogee
42.223950,38.000000,2.6,0, 31, 30, , , 0.95, 0, 0,0,,
 9492.12 9497.80 9507.86 9517.92 9538.04 9558.16 9568.22 9588.34 9608.46 9638.64
 9648.70 9658.76 9678.88 9709.06 9719.12 9729.18 9740.87 9753.03 9765.18 9777.34
 9789.50 9817.66 9842.38 9857.47 9894.79 9894.7910137.7910137.7910200.7810236.47
10268.36
  405.28  404.53  402.94  401.57  398.66  395.81  394.49  392.13  389.91  386.76
  385.81  384.97  383.59  381.82  381.13  380.55  379.99  379.12  378.36  377.70
  377.17  376.14  375.57  375.30  375.12  375.12  373.96  373.96  373.72  373.43
  373.50
 -594.72 -595.47 -597.06 -598.43 -601.34 -604.19 -605.51 -607.87 -610.09 -613.24
 -614.19 -615.03 -616.41 -618.18 -618.87 -619.45 -620.01 -620.88 -621.64 -622.30
 -622.83 -623.86 -624.43 -624.70 -624.88  370.12  368.96 -626.04 -626.28 -626.57
 -626.50
 9492.12 9497.80 9507.86 9517.92 9538.04 9558.16 9568.22 9588.34 9608.46 9638.64
 9648.70 9658.76 9678.88 9709.06 9719.12 9729.18 9740.87 9753.03 9765.18 9777.34
 9789.50 9817.66 9853.50 9873.32 9873.3210116.3210116.3210200.7810236.4710268.36
  405.28  404.53  402.94  401.57  398.66  395.81  394.49  392.13  389.91  386.76
  385.81  384.97  383.59  381.82  381.13  380.55  379.99  379.12  378.36  377.70
  377.17  376.14  375.36  375.23  375.23  374.06  374.06  373.72  373.43  373.50
 -594.72 -595.47 -597.06 -598.43 -601.34 -604.19 -605.51 -607.87 -610.09 -613.24
 -614.19 -615.03 -616.41 -618.18 -618.87 -619.45 -620.01 -620.88 -621.64 -622.30
 -622.83 -623.86 -624.64 -624.77  370.23  369.06 -625.94 -626.28 -626.57 -626.50
Pier Skew, UpSta & Num, DnSta & Num=  ,9975.12, 2 ,9953.66, 2 , 0 , 0 , 0 ,,
    4.00    4.00
 -625.26  374.74
    4.00    4.00
 -625.16  374.84
Pier Skew, UpSta & Num, DnSta & Num=  ,10057.45, 2 ,10035.99, 2 , 0 , 0 , 0 ,,
    4.00    4.00
 -625.66  374.34
    4.00    4.00
 -625.55  374.45
BR Coef=-1 , 0 , 0 ,, 0 ,,,0.8,0,1,0,
WSPro=,,,, 1 ,,,, 0 ,,,, 0 ,,,,-1 ,-1 ,-1 , 0 , 0 , 0 , 0 , 0
BC Design=,, 0 ,, 0 ,,,,,,

Type RM Length L Ch R = 1 ,40470.51,483.761400,483.761400,483.761400
XS GIS Cut Line= 6
793767.556513821734734.960448232793686.827347154734348.241698232
793625.629430488734272.720864899793453.754430488734186.783364899
793392.556513821734100.845864899793137.348180488733904.231281566
#Sta/Elev= 30
9392.078432.89469406.722428.38359422.506425.4577 9463.13411.5363 9513.91380.4762
9534.222 373.6019544.378366.79529554.534365.07459952.736358.30559986.277347.6717
9997.458346.436310008.64347.067110019.82350.8205   10031352.280510053.36351.2368
10064.54  352.98 10092.2350.267710103.85352.182810126.68360.104910143.92356.6721
 10178.4359.124710208.58363.433910255.27372.927310318.39373.660610331.01  372.34
10343.63375.5646 10381.5379.141310470.75379.708710482.49380.903110504.78393.0717
#Mann= 3 , 0 , 0
9392.078    0.04       09392.078    0.04       010504.78    0.04       0
#XS Ineff= 2 , 0
       0                               0
Bank Sta=9392.078,10504.78
Exp/Cntr=0.3,0.1

Type RM Length L Ch R = 1 ,39986.75,241.880800,241.880800,241.880800
XS GIS Cut Line= 6
  793925.4225758733735.011385847793809.679010015733721.829927607
793676.045305621733720.639722994793288.769225907733774.774636186
793163.861283247733772.036047364793078.729811243733757.559660642
#Sta/Elev= 30
9564.173393.4025  9584.8381.47169594.901376.83139635.203365.59679655.282362.1813
9695.391 350.1599735.414343.98069765.428341.38159825.473347.3716 9845.53345.2962
9855.558345.88039865.587 347.3099875.634352.51799885.713350.36849895.793343.6387
9926.081343.29939946.408341.08399976.898340.30179987.062341.078310007.41339.6045
 10017.6339.673810037.97348.273810058.34359.921410068.53361.805610209.59361.6028
10219.59363.093910239.59  372.6210249.59375.541210370.08 384.00810417.26386.1378
#Mann= 3 , 0 , 0
9564.173  0.0454       09564.173  0.0454       010417.26  0.0454       0
#XS Ineff= 2 , 0
       0 9612.68                       0
Bank Sta=9564.173,10417.26
Exp/Cntr=0.3,0.1

Type RM Length L Ch R = 1 ,39744.87,241.880700,241.880700,241.880700
XS GIS Cut Line= 6
793875.087006185733548.767110838793785.023210586733535.673249362
793088.336419026733463.054654044792907.695392106733422.457621864
792791.424845578733383.242877591792713.763375994733351.069399769
#Sta/Elev= 30
9608.602431.3864 9649.11 401.7749689.531364.77069699.636363.69619719.732352.4757
9729.781349.64649780.022343.05359830.262343.85869890.552337.69499950.876339.6097
10011.29335.986410031.41338.327610041.48 345.61510051.54349.761310081.71350.0912
10091.75352.9548 10131.9353.950410182.09348.438110222.25357.822910282.52361.0581
 10292.6360.130210332.93 365.81110393.43366.4231 10495.3371.965910619.65372.8959
10651.19375.965710704.32384.5084   10730 390.34410747.44398.488910792.19399.7097
#Mann= 3 , 0 , 0
9608.602  0.0561       09608.602  0.0561       010792.19  0.0561       0
#XS Ineff= 2 , 0
       0                               0
Bank Sta=9608.602,10792.19
Exp/Cntr=0.3,0.1

Type RM Length L Ch R = 1 ,39502.99,241.880700,241.880700,241.880700
XS GIS Cut Line= 6
793849.790063761733320.511106416793666.183968332733282.896935371
793396.485413764 733253.41085585793156.025646628 733220.57118387
792942.231514186733174.960991316792743.638113147733112.410996557
#Sta/Elev= 30
9657.616415.43069672.838400.26839714.004366.20619734.487 352.0429744.653346.8462
9754.819344.92749785.317343.45899846.303343.86489876.567340.60329906.832 341.064
 9916.92336.41359927.008334.49779957.184334.83269987.334333.095210037.57334.1774
10067.71342.581410158.24346.366910178.39345.615510228.77351.458410339.97348.3219
10503.02354.680210574.98358.8841 10606.2363.480210637.45373.595810658.29377.9867
10699.97381.5689 10721.1386.789710742.22386.661310763.35390.931310786.11393.1689
#Mann= 3 , 0 , 0
9657.616  0.0521       09657.616  0.0521       010786.11  0.0521       0
#XS Ineff= 2 , 0
       0                               0
Bank Sta=9657.616,10786.11
Exp/Cntr=0.3,0.1

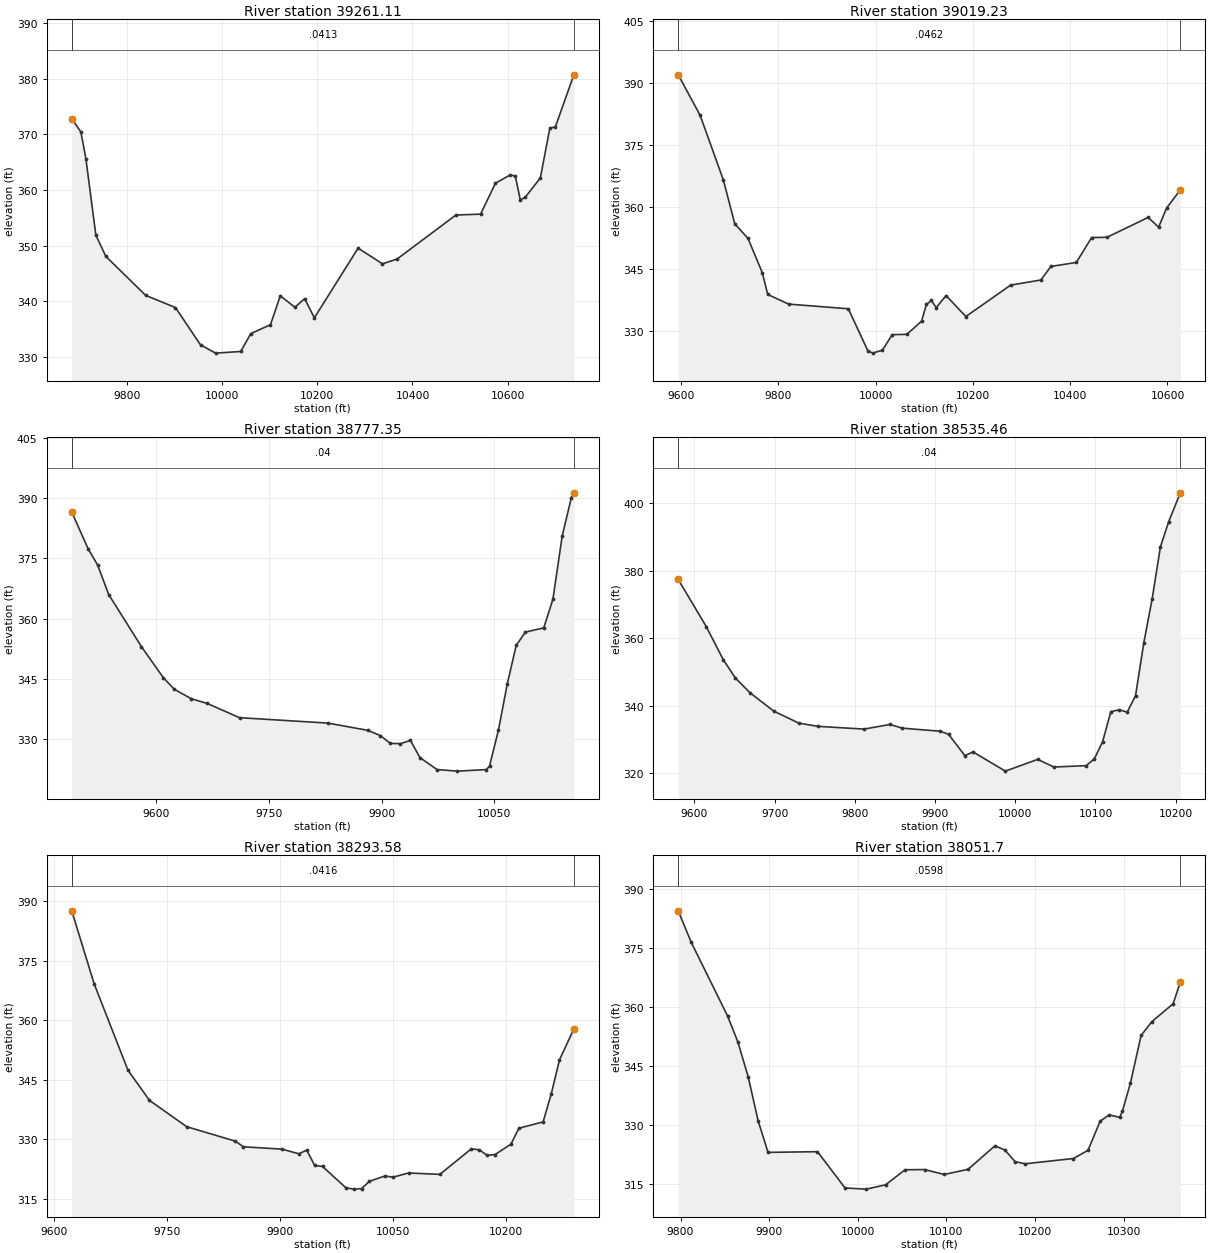
Type RM Length L Ch R = 1 ,39261.11,241.880700,241.880700,241.880700
XS GIS Cut Line= 6
793852.981468698733122.853067347793476.065281999733002.378995391
793242.912084452732951.910124757793066.601461711 732909.79179729
 792970.69893412732882.462865689792838.223924204732838.941380374
#Sta/Elev= 30
9684.176372.79839703.296370.45429713.799365.66999734.803351.89879755.807348.0966
 9839.41341.09639902.027 338.9079954.693332.20419986.446330.723110039.29331.0222
10060.19334.224310101.64335.823710122.23341.0116   10153338.962310173.43340.4972
10193.86337.061410285.77349.578810336.91346.758710367.67347.624110491.17355.5203
10543.09355.688210574.28361.238910605.54362.735710616.05362.512310626.57358.2218
10637.08358.743410668.61362.185610688.63371.154510700.15371.3484   10739380.7051
#Mann= 3 , 0 , 0
9684.176  0.0413       09684.176  0.0413       0   10739  0.0413       0
#XS Ineff= 2 , 0
       0                               0
Bank Sta=9684.176,10739
Exp/Cntr=0.3,0.1

Type RM Length L Ch R = 1 ,39019.23,241.880700,241.880700,241.880700
XS GIS Cut Line= 6
793962.039796941732932.173407817793851.289731718732860.117946184
793742.204702821732813.906108637793378.641889087732767.044856442
793203.774155099732721.757250433792983.295151314732644.996076776
#Sta/Elev= 30
 9594.23392.07439639.238382.28619687.022366.62269710.394 356.0319737.691352.4964
9767.143344.15959778.196 338.9279821.193 336.5969943.908335.46479984.014325.3215
 9994.04324.732510014.08325.456810034.13329.205510064.21 329.27610094.39332.4516
10104.45336.516310114.51 337.48710124.57335.744810144.87338.666910185.46 333.588
10277.58341.187710339.66342.429910360.44345.707410412.61346.6745 10444.1352.6985
10475.65352.7573 10560.4357.576310581.79355.213310598.28359.846510626.41364.2414
#Mann= 3 , 0 , 0
 9594.23  0.0462       0 9594.23  0.0462       010626.41  0.0462       0
#XS Ineff= 2 , 0
       0                               0
Bank Sta=9594.23,10626.41
Exp/Cntr=0.3,0.1

Type RM Length L Ch R = 1 ,38777.35,241.880700,241.880700,241.880700
XS GIS Cut Line= 6
794001.416032015732897.901499518793862.087409526732768.069008052
793669.992416454732582.637315673793646.363791096732566.249420654
793555.980034225732514.612371169793492.279400707732469.660912142
#Sta/Elev= 30
9487.578386.52449509.532377.28849521.925373.36449536.777 365.9659580.321353.0038
9609.518345.26219624.117342.38319646.583340.03399667.914338.8567 9710.89335.3133
9828.416333.9649 9881.81332.15859898.396 330.8519911.734328.91279925.072328.8407
 9938.41 329.6549951.164325.35599973.844322.4002   10001 322.00310039.57322.3867
10043.78323.287210055.58332.201410067.37343.717510079.21353.295710091.45356.6261
10115.93357.669410128.17364.855110140.41380.490710152.65390.104210155.98391.3061
#Mann= 3 , 0 , 0
9487.578    0.04       09487.578    0.04       010155.98    0.04       0
#XS Ineff= 2 , 0
       0                               0
Bank Sta=9487.578,10155.98
Exp/Cntr=0.3,0.1

Type RM Length L Ch R = 1 ,38535.46,241.880800,241.880800,241.880800
XS GIS Cut Line= 6
794032.082593565732871.210232988 793925.05017563732737.607404009
793877.738504946732640.864731112793856.818745663732548.008981417
793840.084845014732416.554385283793811.524416204732301.312612166
#Sta/Elev= 30
9579.837377.39749614.722363.45419636.031353.62649651.184 348.1969669.213343.8828
9698.751338.45129730.073334.88139754.227333.91779811.432333.10959843.882334.4806
9859.134333.38359906.642332.4763  9916.9331.56979937.188325.24889947.332326.3578
9987.664320.671410027.99324.149610048.16321.884310088.53322.295310098.73324.3579
10108.93329.397110119.13338.242210129.33338.822610139.57338.152110149.94  342.97
 10160.3358.661710170.66371.624710181.02387.063910191.38394.518810205.78403.0177
#Mann= 3 , 0 , 0
9579.837    0.04       09579.837    0.04       010205.78    0.04       0
#XS Ineff= 2 , 0
       0                               0
Bank Sta=9579.837,10205.78
Exp/Cntr=0.3,0.1

Type RM Length L Ch R = 1 ,38293.58,241.880700,241.880700,241.880700
XS GIS Cut Line= 6
794230.411029385732799.490143716794179.041613939732710.048659039
794150.996627433732648.332573586794100.843116064732500.907626885
 794049.26157125732317.069062293793997.860310642732177.414612137
#Sta/Elev= 30
9623.208387.55899652.834369.2293 9697.79347.42769726.391339.82119775.873 333.192
9840.409329.55469851.078 328.1499902.085327.55049924.744326.38699935.212327.2939
 9945.68 323.4439956.097323.19219987.244317.81039997.626317.480610008.01317.6102
10018.39319.450710039.17320.797510049.56320.485610070.33321.540210111.89321.1979
10153.61327.608210164.14327.397710174.67325.9866 10185.2326.183610206.27328.8051
10216.96332.8272   10249334.405210259.85341.483910270.71350.0078 10289.8357.8301
#Mann= 3 , 0 , 0
9623.208  0.0416       09623.208  0.0416       0 10289.8  0.0416       0
#XS Ineff= 2 , 0
       0                               0
Bank Sta=9623.208,10289.8
Exp/Cntr=0.3,0.1

Type RM Length L Ch R = 1 , 38051.7,241.880700,241.880700,241.880700
XS GIS Cut Line= 6
794412.412577064732563.213014226794372.602306114732494.769486702
794341.328372991732432.920113901794282.741698313732303.621895304
794234.796813049 732216.63878301794138.506474443732068.278937252
#Sta/Elev= 30
9797.418384.51379812.161376.46199853.194357.72679864.762351.12089876.331342.3207
9887.545331.14389898.751323.0569 9954.59323.24019985.679313.999410009.49313.7104
10031.45314.803910053.41318.639410075.37318.6852 10097.7317.436110124.61318.7602
 10154.8324.719510166.04323.660510177.63320.698510189.11320.157510243.41321.5013
10259.86323.5735 10273.6330.999310283.66332.577410295.71331.980110298.69333.4987
10307.77340.698310319.82352.805710331.87356.299210355.97360.866510364.07366.3977
#Mann= 3 , 0 , 0
9797.418  0.0598       09797.418  0.0598       010364.07  0.0598       0
#XS Ineff= 2 , 0
       0                               0
Bank Sta=9797.418,10364.07
Exp/Cntr=0.3,0.1

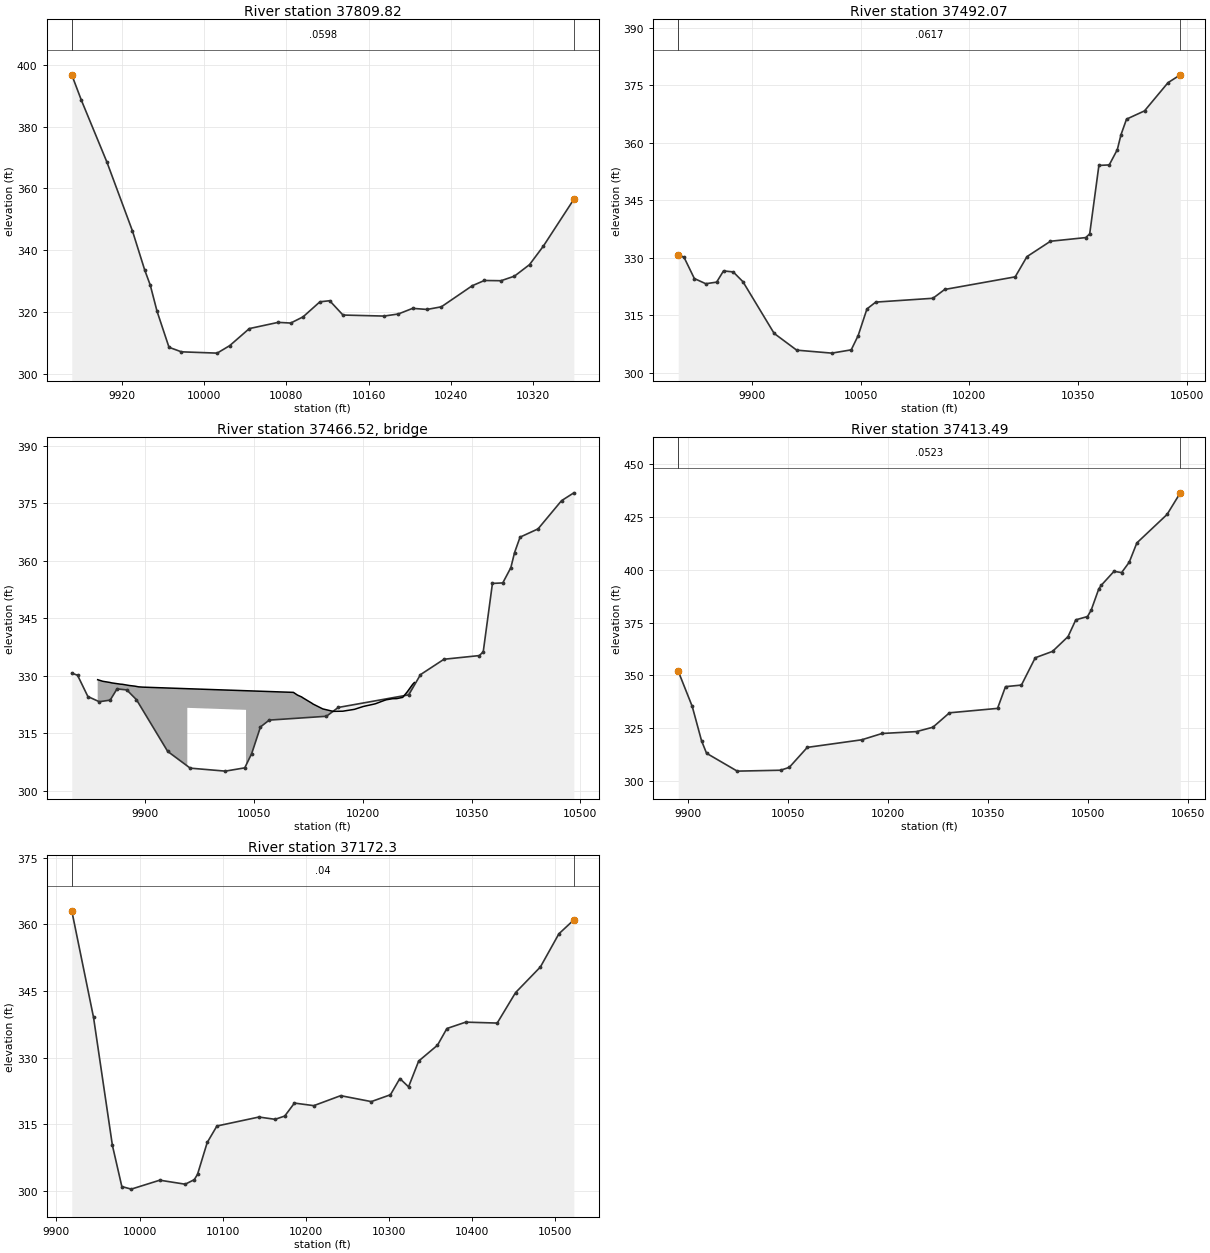
Type RM Length L Ch R = 1 ,37809.82,317.750500,317.750500,317.750500
XS GIS Cut Line= 6
794592.404904677732289.572886244 794547.20700521732255.981358972
794418.508812774 732175.00272274794380.307177385732145.599555216
794274.311385904732046.108219476794215.551809436731983.310761217
#Sta/Elev= 30
9871.528396.82389880.899388.56519905.743368.50759930.487 346.2769942.452 333.558
9947.847328.67299954.417320.2173 9966.06308.53869978.118307.075710012.86 306.653
10025.03 309.07310044.12314.601610072.14316.618610084.39316.400410096.36318.4038
10112.76323.279710122.25323.633110135.17318.9933   10175318.658710188.95319.3333
 10202.9321.158310216.85320.8058 10230.8321.657610260.85328.494110272.64 330.187
10288.81330.113210301.86 331.593 10316.5335.3215 10329.9341.2925 10359.6356.4966
#Mann= 3 , 0 , 0
9871.528  0.0598       09871.528  0.0598       0 10359.6  0.0598       0
#XS Ineff= 2 , 0
       0                               0
Bank Sta=9871.528,10359.6
Exp/Cntr=0.3,0.1

Type RM Length L Ch R = 1 ,37492.07,78.586700,78.586700,78.586700
XS GIS Cut Line= 4
794800.304120779732121.570114508794730.778816521732043.759230077
794632.315642238731899.722734481 794306.59752354731644.534129664
#Sta/Elev= 30
9798.573330.66739806.533  330.139820.794324.5628 9836.55323.20559851.559323.6242
9861.025326.55469874.435326.29059887.845323.72879930.879310.22899961.983305.8525
10010.44305.0743 10037.2305.931110046.78 309.65910058.89316.6173   10071318.4036
10149.91319.403710166.13321.705510263.41325.003110279.63330.286410312.06334.3048
 10360.7335.259710366.17336.231110378.87354.112410393.13354.248110404.28358.2423
10409.35362.145210416.98366.204710441.77368.3593 10474.2375.733310491.17377.7824
#Mann= 3 , 0 , 0
9798.573  0.0617       09798.573  0.0617       010491.17  0.0617       0
#XS Ineff= 2 , 0
       09894.449        10127.94       0
Bank Sta=9798.573,10491.17
Exp/Cntr=0.3,0.1

Type RM Length L Ch R = 3 ,37466.52,,,
BEGIN DESCRIPTION:
END DESCRIPTION:
Bridge Culvert--1,0,-1,-1, 0
Deck Dist Width WeirC Skew NumUp NumDn MinLoCord MaxHiCord MaxSubmerge Is_Ogee
29.293350,20.000000,2.6,0, 41, 41, , , 0.95, 0, 0,0,,
 9834.31 9841.25 9851.19 9853.57 9865.88 9868.32 9878.20 9885.46 9890.51 9896.42
 9957.95 9957.9510038.9510038.9510104.1610104.3310109.9110115.7210117.5710130.29
10131.3210144.8610145.0710158.8310159.4310172.5810174.0010186.3310188.5610200.08
10203.1310213.8310217.7010227.5810232.2710241.3310246.8410255.0810261.4110268.83
10271.16
  328.96  328.55  328.24  328.13  327.79  327.76  327.44  327.28  327.10  327.02
  326.61  326.61  326.08  326.08  325.65  325.65  324.94  324.45  324.21  322.76
  322.61  321.33  321.32  320.70  320.69  320.73  320.78  321.15  321.22  321.93
  322.07  322.51  322.69  323.40  323.71  324.00  324.02  324.34  325.80  327.75
  328.22
 -671.04 -671.45 -671.76 -671.87 -672.21 -672.24 -672.56 -672.72 -672.90 -672.98
 -673.39  321.61  321.08 -673.92 -674.35 -674.35 -675.06 -675.55 -675.79 -677.24
 -677.39 -678.67 -678.68 -679.30 -679.31 -679.27 -679.22 -678.85 -678.78 -678.07
 -677.93 -677.49 -677.31 -676.60 -676.29 -676.00 -675.98 -675.66 -674.20 -672.25
 -671.78
 9834.31 9841.25 9851.19 9853.57 9865.88 9868.32 9878.20 9885.46 9890.51 9896.42
 9963.50 9963.5010044.5010044.5010104.1610104.3310109.9110115.7210117.5710130.29
10131.3210144.8610145.0710158.8310159.4310172.5810174.0010186.3310188.5610200.08
10203.1310213.8310217.7010227.5810232.2710241.3310246.8410255.0810261.4110268.83
10271.16
  328.96  328.55  328.24  328.13  327.79  327.76  327.44  327.28  327.10  327.02
  326.58  326.58  326.04  326.04  325.65  325.65  324.94  324.45  324.21  322.76
  322.61  321.33  321.32  320.70  320.69  320.73  320.78  321.15  321.22  321.93
  322.07  322.51  322.69  323.40  323.71  324.00  324.02  324.34  325.80  327.75
  328.22
 -671.04 -671.45 -671.76 -671.87 -672.21 -672.24 -672.56 -672.72 -672.90 -672.98
 -673.42  321.58  321.04 -673.96 -674.35 -674.35 -675.06 -675.55 -675.79 -677.24
 -677.39 -678.67 -678.68 -679.30 -679.31 -679.27 -679.22 -678.85 -678.78 -678.07
 -677.93 -677.49 -677.31 -676.60 -676.29 -676.00 -675.98 -675.66 -674.20 -672.25
 -671.78
BR Coef=-1 , 0 , 0 ,, 0 ,,,0.8,0,1,0,
WSPro=,,,, 1 ,,,, 0 ,,,, 0 ,,,,-1 ,-1 ,-1 , 0 , 0 , 0 , 0 , 0
BC Design=,, 0 ,, 0 ,,,,,,

Type RM Length L Ch R = 1 ,37413.49,241.181500,241.181500,241.181500
XS GIS Cut Line= 6
794814.660460953732000.090389392794776.344073195731960.721111043
794670.476645936731837.690231577794573.641150975731751.461281083
794430.522250093731652.906776772794227.353077601731538.302805054
#Sta/Elev= 30
9884.865352.04879905.923335.34969919.877319.13189927.392313.22329973.461 304.775
10038.51305.197610051.66 306.55110078.72316.002410160.48319.588810191.02322.5753
 10242.8323.471110267.44325.543410292.27332.355910364.51334.446910376.46344.7321
10400.37345.464110421.14358.3947 10447.1361.4064 10470.4368.397110482.05376.3292
10499.62377.883310505.08380.843610516.53390.931410520.16392.615510539.43399.2581
10550.88 398.67110562.33403.592910573.78412.704910619.14426.163910639.04436.3883
#Mann= 3 , 0 , 0
9884.865  0.0523       09884.865  0.0523       010639.04  0.0523       0
#XS Ineff= 2 , 0
       0                10136.61       0
Bank Sta=9884.865,10639.04
Exp/Cntr=0.3,0.1

Type RM Length L Ch R = 1 , 37172.3,241.181600,241.181600,241.181600
XS GIS Cut Line= 6
794977.384867541731786.153508338794958.013608052731774.178061076
794857.703779605731720.619083071794645.856983392731595.671706446
794522.918603325731530.426350054794448.855773159731494.187681461
#Sta/Elev= 30
9918.446363.0294 9944.64339.03379967.336310.23379978.684300.96419990.033300.3873
10024.33302.398610054.93301.495310065.86302.516610069.75303.718210081.41310.8834
10093.07314.593210143.63316.614310163.07316.102210174.69316.835610186.35319.7567
10209.63319.177210241.99321.424310278.82320.089910301.86321.629710313.18 325.281
10323.66323.410310335.83329.216210358.47332.780710369.79336.538810392.43337.9746
10430.32337.766310452.42344.624610482.29350.395410504.55357.863510522.53360.9913
#Mann= 3 , 0 , 0
9918.446    0.04       09918.446    0.04       010522.53    0.04       0
#XS Ineff= 2 , 0
       0                               0
Bank Sta=9918.446,10522.53
Exp/Cntr=0.3,0.1