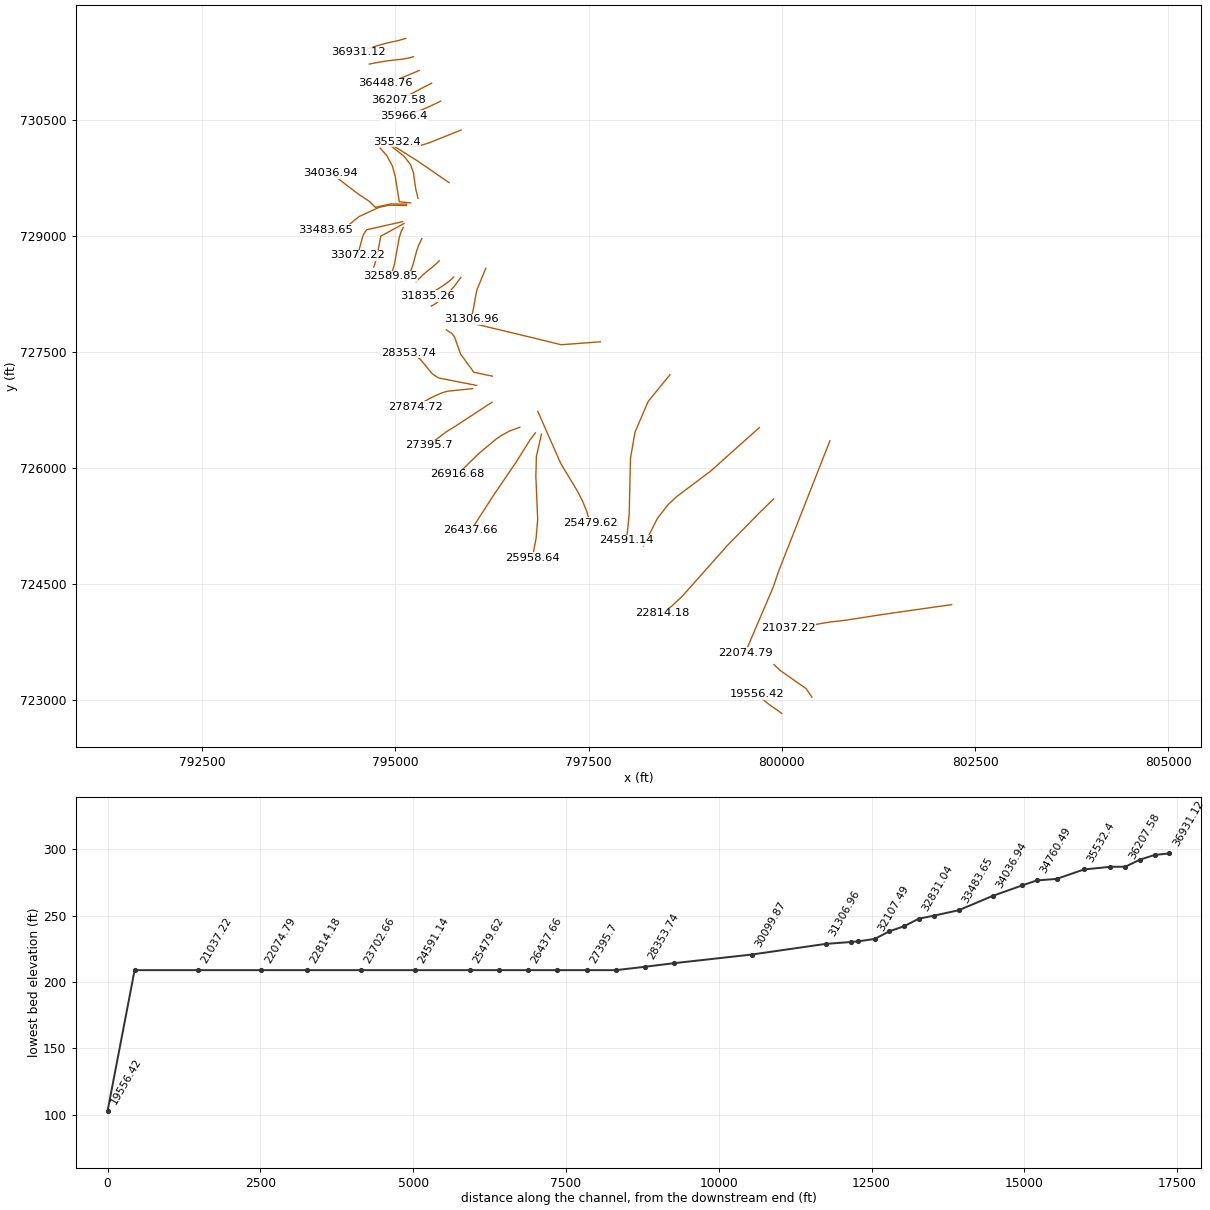
HEC-RAS study 6721_ras.prj: 6721

--- 6721_ras.g01 (geometry) --- (continued)

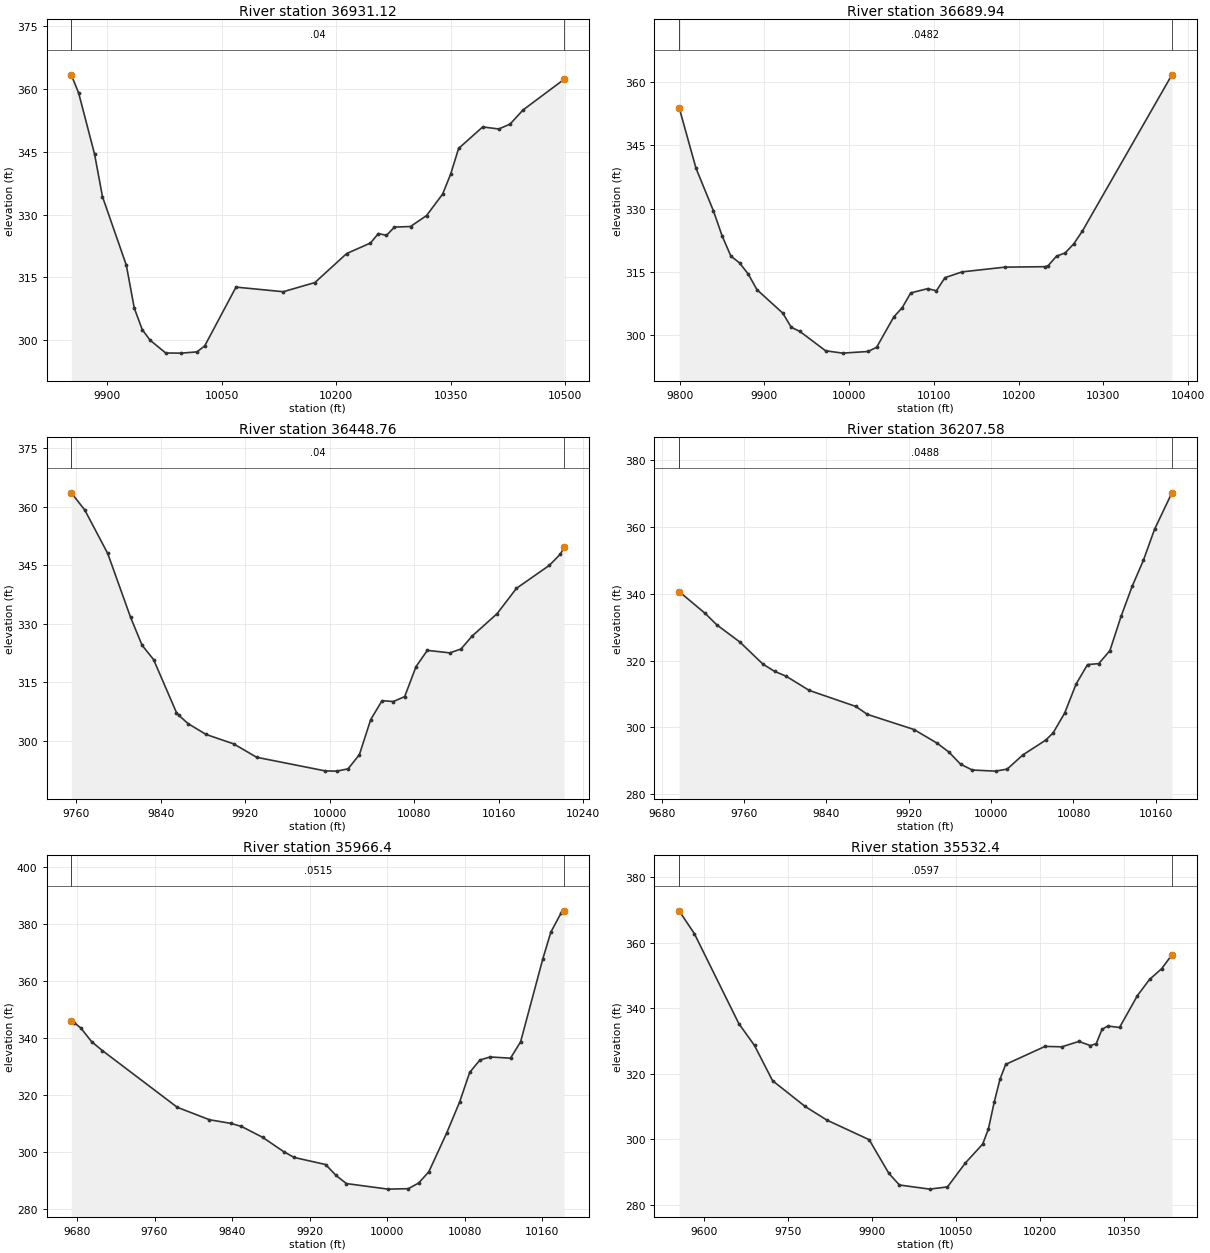
Type RM Length L Ch R = 1 ,36931.12,241.181500,241.181500,241.181500
XS GIS Cut Line= 6
795134.034037352731560.424233467795040.976571656731532.870022181
794878.556010009731496.324290602794751.268578661731460.547134828
794607.287972463 731414.01722879794514.158162458731381.961661345
#Sta/Elev= 30
9853.051363.32739862.653358.99939883.503344.43149893.909 334.2579925.126317.9275
9935.531 307.7149945.937302.57149956.244300.03649976.724296.97979997.204296.9454
10017.63297.240710027.84298.674210068.83312.6923 10130.7311.592110172.25313.7864
 10213.8320.698910244.97323.203910255.43325.476810265.94325.027610276.45327.0073
10297.47327.147810318.49329.7591 10339.5334.871810350.01339.625810360.52345.7803
10392.05350.899310413.15350.410610427.86351.574710444.88354.940310498.65362.2512
#Mann= 3 , 0 , 0
9853.051    0.04       09853.051    0.04       010498.65    0.04       0
#XS Ineff= 2 , 0
       0                               0
Bank Sta=9853.051,10498.65
Exp/Cntr=0.3,0.1

Type RM Length L Ch R = 1 ,36689.94,241.181500,241.181500,241.181500
XS GIS Cut Line= 6
795234.167680523731322.361286017795152.699264894731301.930338854
795078.672850957731289.663892679794897.326805577731270.021794876
794739.594750342731243.290843129794661.392359477731227.064246754
#Sta/Elev= 30
9799.432353.91949819.359339.5416 9839.93329.46569850.216323.50769860.502318.7581
9870.788317.14229881.074314.47319891.245310.80969921.654305.2711 9931.79301.9008
9941.927300.9276 9972.22296.35049992.322295.792710022.46296.1838 10032.5297.1951
10052.59304.336510062.63306.5546 10072.7310.042710092.85311.062410102.93310.5453
10113.01313.645610133.17315.017810183.83316.144810230.81316.249210234.55316.4482
10244.69318.749310254.83 319.50310264.97321.653610275.12324.668610380.75361.6569
#Mann= 3 , 0 , 0
9799.432  0.0482       09799.432  0.0482       010380.75  0.0482       0
#XS Ineff= 2 , 0
       0                               0
Bank Sta=9799.432,10380.75
Exp/Cntr=0.3,0.1

Type RM Length L Ch R = 1 ,36448.76,241.181500,241.181500,241.181500
XS GIS Cut Line= 6
795306.793082385731144.493410094795087.212663605731052.106767927
795080.269322539731049.334677446794982.275741809731011.344863126
794921.302942036730991.342728432794871.667218763730977.028988146
#Sta/Elev= 30
9755.299363.59839768.094359.17639789.792348.0416 9811.49331.63149822.339324.5037
9833.188320.85739854.886307.25189857.135  306.569865.735304.44419882.921301.6454
9909.132299.2178 9930.83295.78799995.908292.290110006.65292.237810017.38292.8228
 10028.1296.465310038.83305.456810049.55310.303110060.28310.0867   10071311.3483
10081.73 319.03710092.45323.203910113.76322.560110124.28323.548510134.81326.8524
10158.54332.627810176.83339.111410208.05345.017510218.46 347.88810221.93349.6216
#Mann= 3 , 0 , 0
9755.299    0.04       09755.299    0.04       010221.93    0.04       0
#XS Ineff= 2 , 0
       0                               0
Bank Sta=9755.299,10221.93
Exp/Cntr=0.3,0.1

Type RM Length L Ch R = 1 ,36207.58,241.181600,241.181600,241.181600
XS GIS Cut Line= 6
795467.653698104730979.178842451 795360.43835689730924.860459955
795162.002142528730820.017830361795112.346735059730796.301600139
795058.598268462730773.629489296795039.055639267730766.826513103
#Sta/Elev= 30
9696.905340.6787  9722.3334.1164 9733.51330.7142 9755.93325.5632 9778.35318.9454
9789.561   316.89800.771315.34889823.247311.08439868.502306.28339879.815303.8971
 9925.07299.36969947.697295.2403 9959.01292.60619970.324288.98969981.638 287.241
10004.27286.907710015.56287.512510030.79291.754110053.17296.219710060.37298.4379
10071.45304.303310082.53312.975510093.61318.814210104.53319.101710115.38323.0004
10126.23333.273610137.09342.318710147.94350.0702 10158.7 359.28910175.58370.2428
#Mann= 3 , 0 , 0
9696.905  0.0488       09696.905  0.0488       010175.58  0.0488       0
#XS Ineff= 2 , 0
       0                               0
Bank Sta=9696.905,10175.58
Exp/Cntr=0.3,0.1

Type RM Length L Ch R = 1 , 35966.4,433.992100,433.992100,433.992100
XS GIS Cut Line= 6
795583.911292118730746.292597721795436.323551229730676.517202485
795359.928426198730643.458978054795284.921185714730614.440626781
795175.404759847730577.373407938 795111.78961991730559.349688991
#Sta/Elev= 30
9674.076345.7228  9677.1345.23719683.933343.35579694.994338.59929706.055335.4762
9783.484315.55759816.668311.19679838.768309.91919849.664308.85439871.457305.0532
9893.249300.01999904.145297.96099936.614295.48729947.363291.65589958.112288.8033
   10001286.856710022.03287.022710032.59288.994910043.15292.947910061.64306.6046
10074.82 317.33110085.37327.836710095.93332.157710106.49333.215210127.46332.7857
10137.87338.533110160.81367.614210169.12377.016710179.44 383.56610182.75384.4696
#Mann= 3 , 0 , 0
9674.076  0.0515       09674.076  0.0515       010182.75  0.0515       0
#XS Ineff= 2 , 0
       0                               0
Bank Sta=9674.076,10182.75
Exp/Cntr=0.3,0.1

Type RM Length L Ch R = 1 , 35532.4,446.831700,446.831700,446.831700
XS GIS Cut Line= 6
795850.299967692730374.091955406795433.435789948730206.867085933
795307.274306864730169.242728643795242.636432843730163.976898057
795175.274771752730170.921192289795018.096096951730224.647879091
#Sta/Elev= 30
9554.926369.72789582.116362.78319661.655335.30559689.584328.65829721.824317.9246
9780.058310.05639818.754 305.914 9894.39 299.9229929.574289.64959948.415286.1132
10002.41  284.8510034.23285.528310066.04292.793710097.14298.601310107.42303.2471
 10117.7311.382910127.98318.328810138.22322.900110208.49328.377110238.57 328.255
 10268.9 329.89810289.55328.628810299.87329.2049 10310.2333.576110320.52334.6022
10341.53334.145310373.55343.897310395.16348.808810416.77352.081510435.04356.2894
#Mann= 3 , 0 , 0
9554.926  0.0597       09554.926  0.0597       010435.04  0.0597       0
#XS Ineff= 2 , 0
       0                               0
Bank Sta=9554.926,10435.04
Exp/Cntr=0.3,0.1

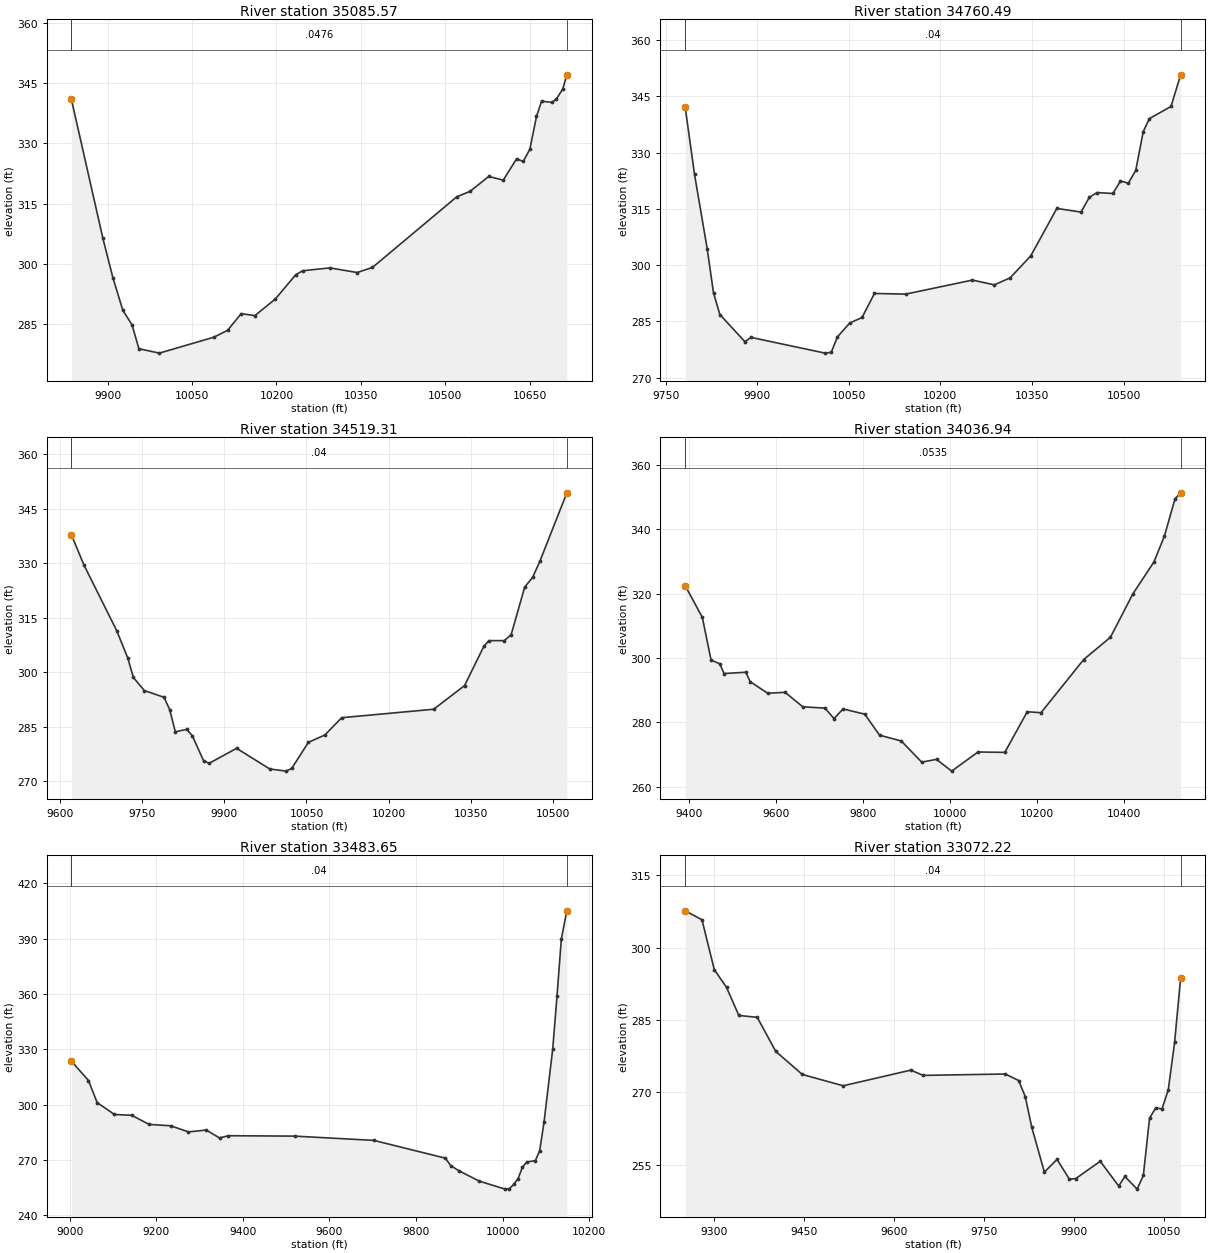
Type RM Length L Ch R = 1 ,35085.57,325.083800,325.083800,325.083800
XS GIS Cut Line= 3
795693.849955291729693.325308755795281.668847412729976.275942385
794959.299519956730178.915354386
#Sta/Elev= 30
9835.549340.91649891.516306.29939909.185296.55929926.854288.43139943.319284.7808
9955.448278.84399991.837277.744610088.87281.716710113.13 283.42510137.39287.5785
10161.65 287.08410198.04291.225910234.43297.291710246.56298.256810295.07298.9778
10343.38297.820710370.69299.087710520.55316.680410544.18318.032110577.38321.7488
10603.23320.829110626.86326.127610638.67325.497810650.48328.524110662.29336.6892
10671.33340.503310690.12340.193710697.73341.045710708.91343.518810716.27347.0605
#Mann= 3 , 0 , 0
9835.549  0.0476       09835.549  0.0476       010716.27  0.0476       0
#XS Ineff= 2 , 0
       0                               0
Bank Sta=9835.549,10716.27
Exp/Cntr=0.3,0.1

Type RM Length L Ch R = 1 ,34760.49,241.181500,241.181500,241.181500
XS GIS Cut Line= 6
795292.298030161729490.556624084795263.049532248729608.206794923
 795233.21586792729819.216321905795197.145325825729922.471692132
795114.577133209730031.845579604794934.366164562730173.863174157
#Sta/Elev= 30
9782.093342.0167 9797.34324.16189818.083304.35939828.455292.56149838.826286.8525
9879.757279.62299889.965280.752310011.21276.562410021.28276.785310031.35280.8751
 10051.5284.583310071.73286.055710092.03292.454810143.34292.288110252.54296.0211
10288.48294.753110314.34296.6261 10348.1302.484110390.81315.116810430.43314.1326
10443.86318.043810456.49319.335410482.55319.088310495.04322.411210507.93 321.837
10520.01325.231610532.32335.580110542.25339.025110577.81342.286710593.57350.7029
#Mann= 3 , 0 , 0
9782.093    0.04       09782.093    0.04       010593.57    0.04       0
#XS Ineff= 2 , 0
       0                               0
Bank Sta=9782.093,10593.57
Exp/Cntr=0.3,0.1

Type RM Length L Ch R = 1 ,34519.31,482.363100,482.363100,482.363100
XS GIS Cut Line= 6
 795197.44729948729430.520918667795049.450942457729445.320554376
794996.528157145729776.975205883794958.699070752729913.329976812
794886.433010876730045.018542096794801.908742934730139.813699931
#Sta/Elev= 30
 9620.85337.86419643.409329.65019703.709311.41099723.808303.92379733.858298.6091
9753.958294.99369789.895293.13769800.215289.76099810.535283.62969831.176 284.309
9841.497282.56629862.063275.68229872.131274.95519922.469279.08819982.875273.4069
10013.07272.809510023.13273.5793 10053.4280.721810083.75282.774110114.22287.5163
10282.28 289.84710338.54296.345610373.99307.200910383.09308.724810410.91308.7391
 10423.6310.323310448.49323.492810462.94326.143910476.31330.647110525.42349.4283
#Mann= 3 , 0 , 0
 9620.85    0.04       0 9620.85    0.04       010525.42    0.04       0
#XS Ineff= 2 , 0
       09777.736                       0
Bank Sta=9620.85,10525.42
Exp/Cntr=0.3,0.1

Type RM Length L Ch R = 1 ,34036.94,553.293100,553.293100,553.293100
XS GIS Cut Line= 6
795144.370788634729414.679475427794936.037455291729417.283642098
794740.072493255729372.598122135794660.670313627729451.967045709
794518.449209481729545.824246556794163.916566938729817.495995387
#Sta/Elev= 30
 9390.26322.48899429.634312.64299449.636 299.4189469.637298.23019479.638295.2132
9529.642295.60439539.643292.69829579.646289.08989620.001289.36469660.674284.8651
9711.754284.46839732.484  281.219753.215284.20639803.012282.59599837.299276.0523
9887.238274.2563 9934.13267.68559968.238268.544510003.11264.890310063.75270.8393
10125.26270.712110176.97283.342310208.53283.032510306.67299.546910368.31306.4828
10419.81319.946910468.23329.846610492.44337.917910516.65349.398810529.73351.3398
#Mann= 3 , 0 , 0
 9390.26  0.0535       0 9390.26  0.0535       010529.73  0.0535       0
#XS Ineff= 2 , 0
       09810.379                       0
Bank Sta=9390.26,10529.73
Exp/Cntr=0.3,0.1

Type RM Length L Ch R = 1 ,33483.65,411.433000,411.433000,411.433000
XS GIS Cut Line= 6
795144.370788634729396.450308755794917.808288604729401.658642098
794787.599955261729373.012808755794527.183288604729253.221142083
794321.454121977729083.950308755794092.287455291729081.346142083
#Sta/Elev= 30
 9003.75323.51259043.131313.06019063.137301.09519103.147294.62499143.158294.1923
9183.168289.25689233.248288.49139274.204285.17659315.161286.19319345.878281.9125
9366.523 283.1179519.224282.89569702.343280.58089868.026270.92599879.804266.9408
9898.398264.18979945.769258.511110005.77254.143610015.77254.386210025.77256.7053
10035.78259.842410045.78265.991910055.78268.813510075.78269.616610085.78275.0917
10095.78290.560910115.78329.988210125.78358.956410135.78 389.91510148.49405.1009
#Mann= 3 , 0 , 0
 9003.75    0.04       0 9003.75    0.04       010148.49    0.04       0
#XS Ineff= 2 , 0
       0  9608.9                       0
Bank Sta=9003.75,10148.49
Exp/Cntr=0.3,0.1

Type RM Length L Ch R = 1 ,33072.22,241.181500,241.181500,241.181500
XS GIS Cut Line= 6
 795092.28745532729188.116975427794629.086316258729083.327391401
794612.910339296729064.547991842794590.534508973729027.862245739
 794576.42428875728995.243512675794510.648761392728755.488525689
#Sta/Elev= 30
9251.522307.61759279.499305.76399300.004295.4482 9320.51291.75559341.015285.9542
9371.773285.56599402.531278.52899446.928273.73439515.311271.39219628.091274.6322
9648.596273.54289785.824273.82619808.125272.47679819.095 269.1569829.982262.8088
9851.062253.50999872.136256.1459 9892.83252.06399903.177252.15169944.356255.7591
9975.132250.6268 9985.39252.605410005.93 249.98910016.26252.815510026.64264.6822
10037.02266.825810047.41266.591710057.87270.549410068.46280.389710078.54293.7469
#Mann= 3 , 0 , 0
9251.522    0.04       09251.522    0.04       010078.54    0.04       0
#XS Ineff= 2 , 0
       09633.216                       0
Bank Sta=9251.522,10078.54
Exp/Cntr=0.3,0.1

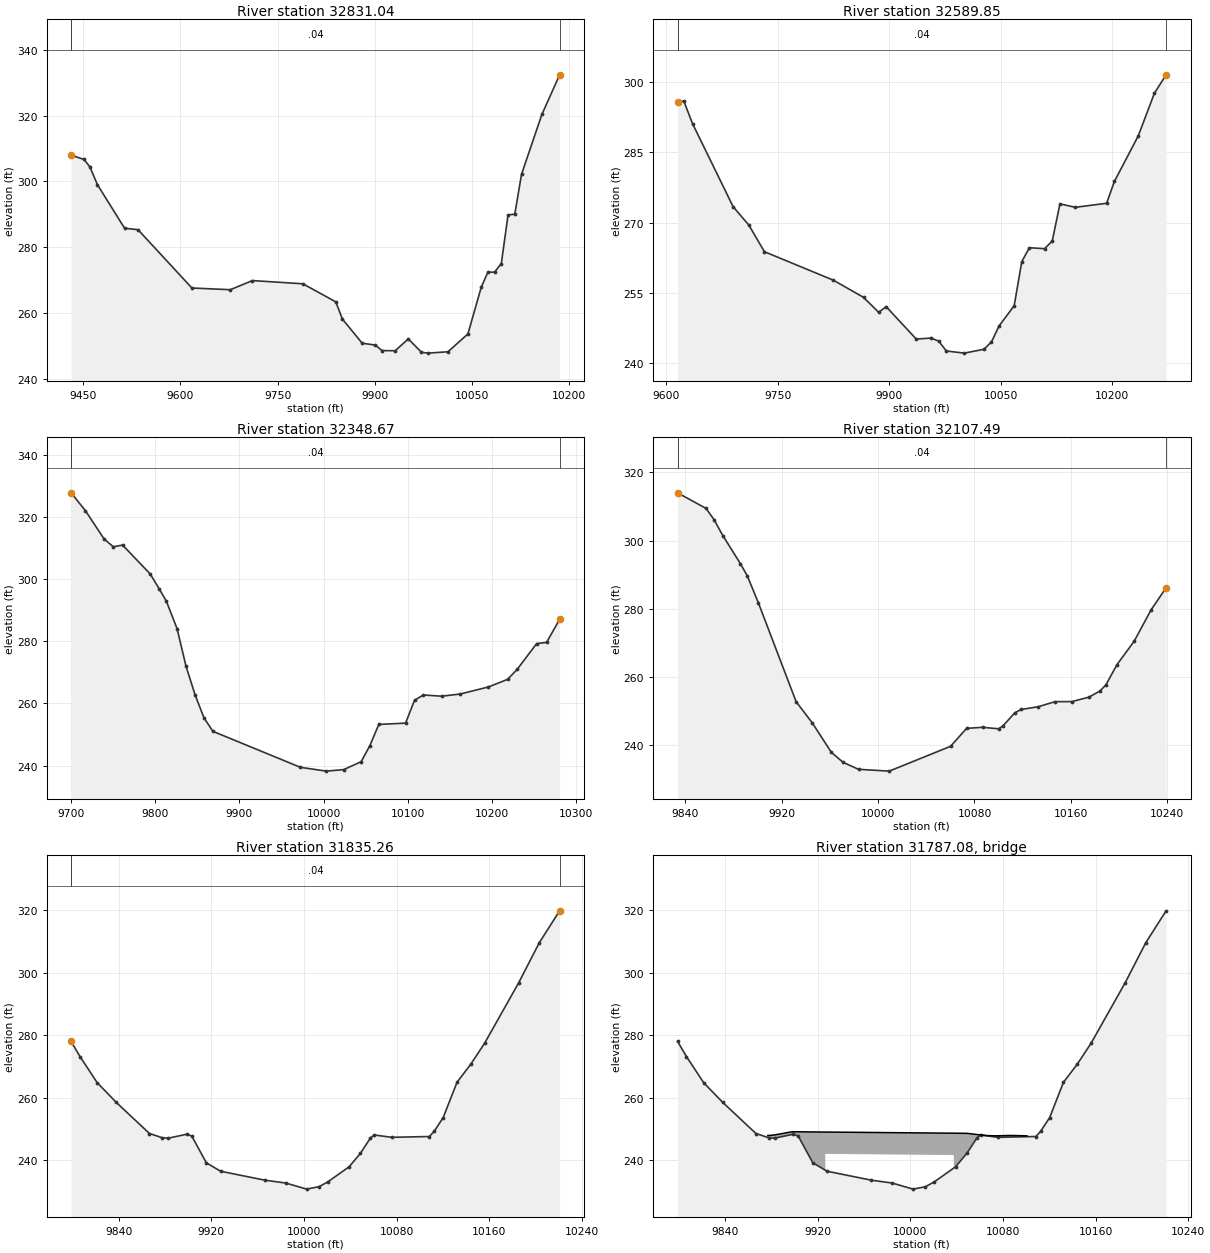
Type RM Length L Ch R = 1 ,32831.04,241.181500,241.181500,241.181500
XS GIS Cut Line= 6
795110.516621947729164.679475427794810.148533136728999.978989169
794767.917982996728776.642041519794750.069672644728701.013526306
 794731.21599865728635.289463729794718.446122468728599.170180589
#Sta/Elev= 30
9431.144308.00089451.276306.68399460.245304.3888 9471.65299.07449513.673 285.786
9534.472285.32769617.668267.59059676.934 267.0759711.148269.84899788.947268.8736
9839.828263.37719850.005258.14259880.534250.80739900.886250.22189911.062 248.566
9931.415248.49669951.768252.0982 9972.12248.03369982.296247.781710012.96248.1912
10043.79253.617710064.34267.800810074.61272.384410084.96272.434610095.37 275.037
10105.77289.824910116.17290.043710126.58302.193710157.99320.385510185.39332.4409
#Mann= 3 , 0 , 0
9431.144    0.04       09431.144    0.04       010185.39    0.04       0
#XS Ineff= 2 , 0
       09739.406                       0
Bank Sta=9431.144,10185.39
Exp/Cntr=0.3,0.1

Type RM Length L Ch R = 1 ,32589.85,241.181500,241.181500,241.181500
XS GIS Cut Line= 6
795100.652815431729112.180264316795075.839489658729064.730761354
795050.054703263728986.906831769794987.381294216 728637.88076882
794953.877018179 728526.55808771794934.367182379728480.518435296
#Sta/Elev= 30
9615.504295.77519623.926295.95779635.655291.13439690.246273.37759711.355269.4534
9732.253 263.769 9824.85 257.6879865.489 254.0169885.809250.82079895.958 252.012
9936.385245.09769956.598245.30979966.705244.62859976.811242.5483   10001242.0878
 10027.4242.910510037.53244.494910047.66247.889310068.02252.213610078.23261.6309
10088.45264.623310108.91264.414910119.24266.077710129.57274.000210150.23273.2558
10192.29274.119410202.82278.8103 10234.8288.515610256.52297.635810272.25301.5794
#Mann= 3 , 0 , 0
9615.504    0.04       09615.504    0.04       010272.25    0.04       0
#XS Ineff= 2 , 0
       0 9780.13                       0
Bank Sta=9615.504,10272.25
Exp/Cntr=0.3,0.1

Type RM Length L Ch R = 1 ,32348.67,241.181600,241.181600,241.181600
XS GIS Cut Line= 6
795341.771335596728969.842487122795301.344079455728884.463063904
795274.979287426728811.591316677795227.914364808728634.921592785
795203.590396958728565.866920879795132.114553377728431.913153508
#Sta/Elev= 30
9700.028327.72939716.956322.02019739.248312.89039750.193310.37589761.138310.9409
9793.973301.64539804.624296.88289813.208292.85669825.893284.04499836.527271.9523
9847.162262.86849857.796   255.49868.431251.04549972.377239.476110003.26238.2543
10023.89238.748310044.53241.300610054.85246.468810065.45 253.26610097.26253.6882
10107.86261.055810118.46262.730210140.12262.346110162.15263.0465 10195.5265.3047
10218.38267.755610229.81270.982610252.82279.249310264.67279.632910280.17287.0594
#Mann= 3 , 0 , 0
9700.028    0.04       09700.028    0.04       010280.17    0.04       0
#XS Ineff= 2 , 0
       0                               0
Bank Sta=9700.028,10280.17
Exp/Cntr=0.3,0.1

Type RM Length L Ch R = 1 ,32107.49,272.232900,272.232900,272.232900
XS GIS Cut Line= 6
795566.083120955728681.951918573795536.325365959728651.356370627
795484.955788758728604.829711483795398.933286178728537.150638117
795352.564612897728496.485107205795266.264258461 728409.55486933
#Sta/Elev= 30
9833.493313.9678 9857.14309.40669863.731306.1404 9871.09301.44989885.642293.2539
9891.453289.60619900.538281.80189931.929 252.8289945.421246.57379961.265237.9481
9970.986 235.0489983.766233.019310009.22232.487710060.17239.752510073.47245.0096
10086.77245.316410100.07244.8798 10103.7245.734810113.37249.5229 10118.7250.5366
 10132.8 251.32810146.89252.828510160.98 252.84910175.07254.150610184.12255.9304
10189.16257.747410198.32263.657710212.51270.475210226.71279.740510239.11286.1689
#Mann= 3 , 0 , 0
9833.493    0.04       09833.493    0.04       010239.11    0.04       0
#XS Ineff= 2 , 0
       0                               0
Bank Sta=9833.493,10239.11
Exp/Cntr=0.3,0.1

Type RM Length L Ch R = 1 ,31835.26,120.975300,120.975300,120.975300
XS GIS Cut Line= 6
795753.945618429728470.159832837795709.173459014728429.492118761
795667.901830558728396.587130549795624.566123541728365.428762035
795453.026006795 728253.59310607795411.275689767728225.098765418
#Sta/Elev= 30
9798.857278.03159806.531273.18419821.404264.79979837.961 258.4489866.548248.5013
9877.469247.16219882.589246.9893 9898.63248.25689903.047247.70769915.699239.1008
9928.016236.4084 9966.27233.53659984.242232.630310002.27230.671710012.99231.4502
10020.65233.005310039.03237.845110048.74 242.14410057.41 247.04410060.66 248.039
10075.79247.280910108.33247.542110112.55249.240410120.25   253.610132.17264.9034
10144.09270.723410156.01277.430410185.52296.859310203.26309.661110220.83319.8928
#Mann= 3 , 0 , 0
9798.857    0.04       09798.857    0.04       010220.83    0.04       0
#XS Ineff= 2 , 0
       0                               0
Bank Sta=9798.857,10220.83
Exp/Cntr=0.3,0.1

Type RM Length L Ch R = 3 ,31787.08,,,
BEGIN DESCRIPTION:
END DESCRIPTION:
Bridge Culvert--1,0,-1,-1, 0
Deck Dist Width WeirC Skew NumUp NumDn MinLoCord MaxHiCord MaxSubmerge Is_Ogee
51.487650,18.000000,2.6,0, 19, 19, , , 0.95, 0, 0,0,,
 9876.78 9881.84 9888.65 9894.59 9898.23 9926.47 9926.4710037.4710037.4710048.35
10049.9010060.3010066.0210073.0510082.1510085.8010098.2710098.5510100.74
  247.84  248.00  248.44  248.87  249.07  248.97  248.97  248.60  248.60  248.56
  248.52  248.05  247.83  247.76  247.84  247.88  247.78  247.77  247.73
 -752.16 -752.00 -751.56 -751.13 -750.93 -751.03  241.97  241.60 -751.40 -751.44
 -751.48 -751.95 -752.17 -752.24 -752.16 -752.12 -752.22 -752.23 -752.27
 9876.78 9881.84 9888.65 9894.59 9898.23 9908.93 9908.9310019.9310019.9310048.35
10049.9010060.3010066.0210073.0510082.1510085.8010098.2710098.5510100.74
  247.84  248.00  248.44  248.87  249.07  249.03  249.03  248.66  248.66  248.56
  248.52  248.05  247.83  247.76  247.84  247.88  247.78  247.77  247.73
 -752.16 -752.00 -751.56 -751.13 -750.93 -750.97  242.03  241.66 -751.34 -751.44
 -751.48 -751.95 -752.17 -752.24 -752.16 -752.12 -752.22 -752.23 -752.27
BR Coef=-1 , 0 , 0 ,, 0 ,,,0.8,0,1,0,
WSPro=,,,, 1 ,,,, 0 ,,,, 0 ,,,,-1 ,-1 ,-1 , 0 , 0 , 0 , 0 , 0
BC Design=,, 0 ,, 0 ,,,,,,

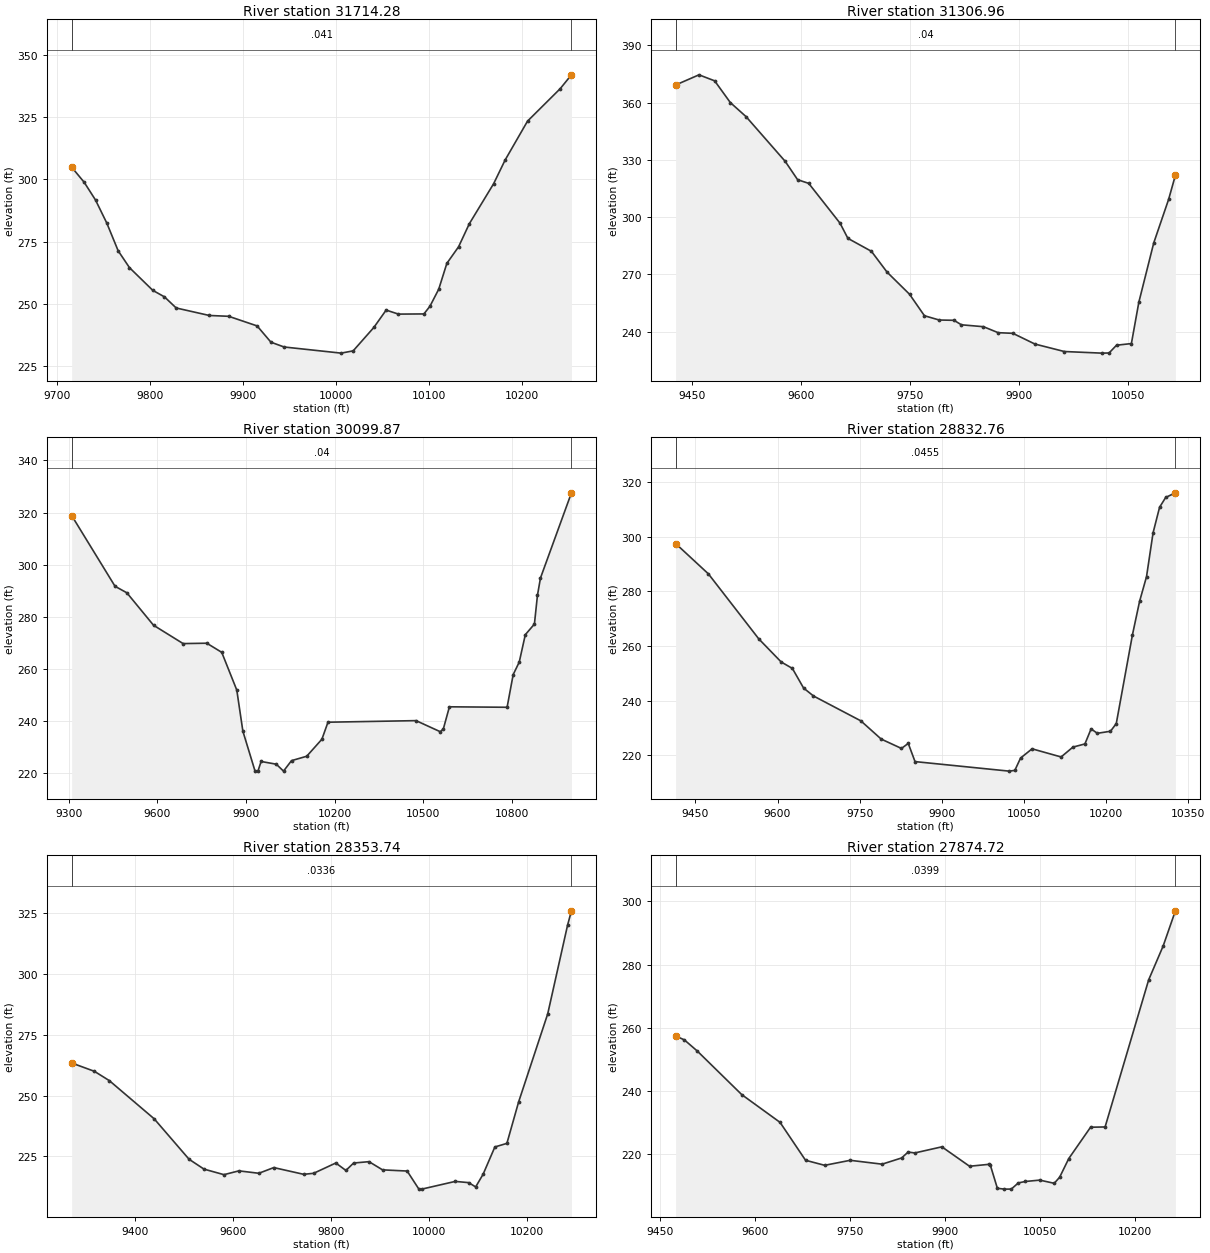
Type RM Length L Ch R = 1 ,31714.28,407.324200,407.324200,407.324200
XS GIS Cut Line= 6
795846.283906511728466.084451692795758.691052608728346.763685436
 795662.99327173 728244.86836498795589.473402291728180.760465129
795530.940480092728135.951951782795464.645018597728093.850482324
#Sta/Elev= 30
9715.593 304.9279729.094298.83729741.274291.72229753.454282.40959765.634271.3081
9777.814264.53349802.878255.41349815.477 252.7859828.076248.32169863.652245.3138
9884.581 244.9789915.154241.10999930.001234.57539944.139232.644110005.53 230.176
10018.49231.086110040.71240.480410053.97247.475810067.23245.860910094.62245.9309
10101.08249.009410110.55255.8676 10119.3266.2639 10131.9272.909810143.46282.1722
10169.68298.310310181.96307.7722 10206.1323.430510241.26 336.47510253.35 342.042
#Mann= 3 , 0 , 0
9715.593   0.041       09715.593   0.041       010253.35   0.041       0
#XS Ineff= 2 , 0
       0                               0
Bank Sta=9715.593,10253.35
Exp/Cntr=0.3,0.1

Type RM Length L Ch R = 1 ,31306.96,1207.088500,1207.088500,1207.088500
XS GIS Cut Line= 6
796168.872618288 728584.83558169796057.537835598728313.474930897
796046.182486802728267.360035807 796033.79588291728204.145906121
796012.278894395728074.989638358795977.173533142727925.897366464
#Sta/Elev= 30
9426.703369.24489458.953374.5799 9480.57 371.4279502.188360.04319523.806352.7023
9577.851329.25199594.976 319.6349610.278317.71969653.514296.84659664.322288.9018
9696.749282.13069718.367271.20829749.341259.62679769.913248.35879790.293246.1205
9810.674245.97239820.864243.62059851.334242.6192 9871.61239.48299891.885239.1488
9922.299233.5287 9962.85229.617210014.28228.774910024.55228.848910034.82232.9133
10055.35233.785810065.62255.452410086.15286.487410106.69 309.32610116.03321.9468
#Mann= 3 , 0 , 0
9426.703    0.04       09426.703    0.04       010116.03    0.04       0
#XS Ineff= 2 , 0
       0                               0
Bank Sta=9426.703,10116.03
Exp/Cntr=0.3,0.1

Type RM Length L Ch R = 1 ,30099.87,1267.111900,1267.111900,1267.111900
XS GIS Cut Line= 5
797651.511507154727633.446692809797144.567062706727595.252248377
796800.057514101727679.562144175796484.166672051727755.652639002
795993.037114769727873.247040004
#Sta/Elev= 30
9309.375318.85189456.301291.70569496.415289.1924 9586.67276.75269686.953269.7076
 9767.18269.85279817.756266.35339868.786251.85459889.376236.08399930.556220.7962
9940.851220.91839951.146224.464510002.62223.424210027.04220.7657 10054.1224.7875
10105.57226.473510157.05232.997910177.63239.539510475.93240.1423 10558.2235.8805
10568.48236.979110589.04245.450110784.42245.271210804.98257.803210825.55262.6121
10846.11273.129810876.96277.197610887.24288.251510897.52294.891911002.37327.5634
#Mann= 3 , 0 , 0
9309.375    0.04       09309.375    0.04       011002.37    0.04       0
#XS Ineff= 2 , 0
       0                               0
Bank Sta=9309.375,11002.37
Exp/Cntr=0.3,0.1

Type RM Length L Ch R = 1 ,28832.76,479.019200,479.019200,479.019200
XS GIS Cut Line= 6
796253.589415133727188.432586893 796014.10095799727239.411353797
795842.743711144727474.967962489795764.446392983727695.682390511
795726.877526909727743.336864948795659.120385587 727786.97854358
#Sta/Elev= 30
9413.828 297.544 9473.73286.43859565.746262.65389606.643254.20649627.091251.8541
9647.539244.67649665.593241.76889752.155232.66499789.254226.00279826.352222.5701
9838.718224.42079851.084217.756610022.86 214.27210033.35214.538310043.85219.0532
10064.84222.433110117.88219.452810139.41223.052510161.36224.223310172.68229.7258
10184.01 228.11310208.08228.858510218.65231.6742 10248.2264.166810261.17276.3564
 10273.9285.436510285.84301.458410297.73 310.81310308.89314.406910326.61316.0932
#Mann= 3 , 0 , 0
9413.828  0.0455       09413.828  0.0455       010326.61  0.0455       0
#XS Ineff= 2 , 0
       0                               0
Bank Sta=9413.828,10326.61
Exp/Cntr=0.3,0.1

Type RM Length L Ch R = 1 ,28353.74,479.019300,479.019300,479.019300
XS GIS Cut Line= 6
796050.635256201727068.737635165795555.940677881727165.680095807
795475.005054176727220.724836603795322.553839535727406.110320717
795260.512175739 727450.44960694795167.812920153727494.249735415
#Sta/Elev= 30
9269.671263.40959316.175259.98359346.745256.15199438.457240.45979509.789223.8371
9540.359219.7758 9581.12217.50429611.691219.06659652.451218.07479683.022220.4138
9744.163217.64379764.544218.06619809.895222.2985 9830.46219.23979846.331222.2885
9877.772222.84739905.461219.47549955.757218.99439979.685211.58189985.604211.5582
10054.11214.732410081.61214.225310095.86212.459410111.14217.693410135.13228.8886
10159.74230.368510183.72247.404110243.19283.577510283.91320.136410291.73325.9496
#Mann= 3 , 0 , 0
9269.671  0.0336       09269.671  0.0336       010291.73  0.0336       0
#XS Ineff= 2 , 0
       0                               0
Bank Sta=9269.671,10291.73
Exp/Cntr=0.3,0.1

Type RM Length L Ch R = 1 ,27874.72,479.019200,479.019200,479.019200
XS GIS Cut Line= 6
795998.775167239727027.630540156795681.164705724726994.235188022
795631.601632357726982.647270679795576.982324779726962.218523204
795457.873023897726907.581867963795258.240284353726795.837240979
#Sta/Elev= 30
9474.851257.45169488.708256.19879508.827252.71679579.243238.88239639.599230.1131
9679.837218.11949710.015216.52119750.253218.10689800.559216.88419831.368218.8474
9841.638220.71459852.176220.43499894.883222.36979938.541216.22679969.523216.8422
9971.464 216.4949982.438209.25769993.412208.989110004.43209.006310015.51210.9579
10026.59211.407310049.24211.841910072.16210.832510080.72212.768810095.08218.6601
10129.46228.572310152.38228.656710221.14275.213810244.06285.948210263.27297.0315
#Mann= 3 , 0 , 0
9474.851  0.0399       09474.851  0.0399       010263.27  0.0399       0
#XS Ineff= 2 , 0
       0                               0
Bank Sta=9474.851,10263.27
Exp/Cntr=0.3,0.1

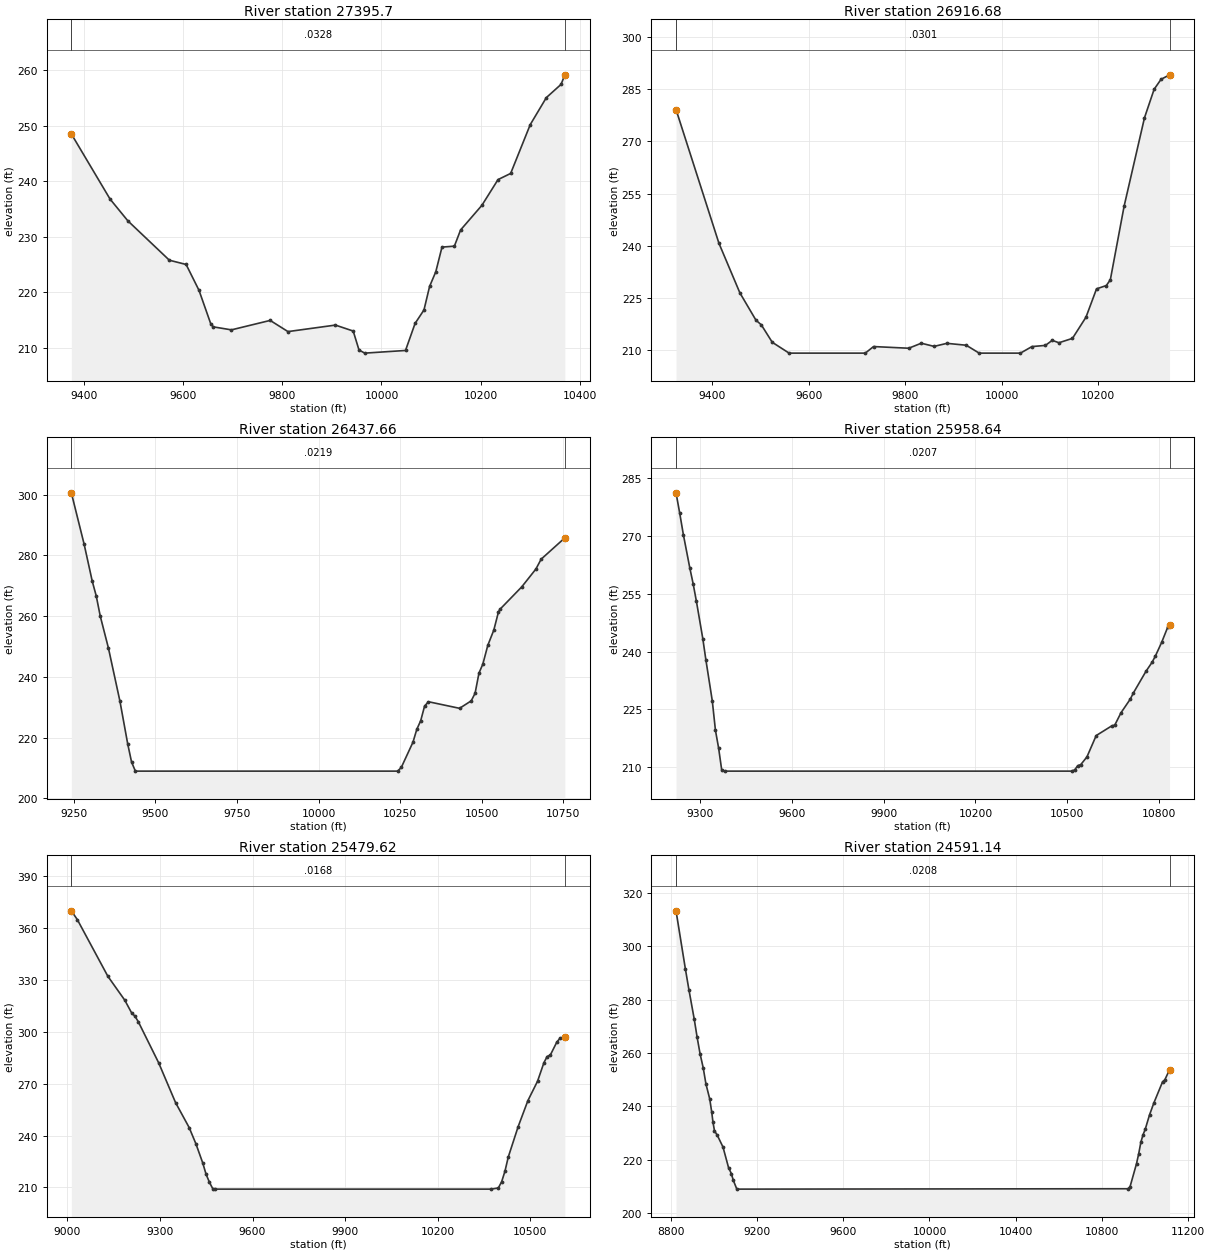
Type RM Length L Ch R = 1 , 27395.7,479.019300,479.019300,479.019300
XS GIS Cut Line= 6
796250.288033992726851.723746255 795773.27187714726539.432192951
795701.425236851726496.659555972795654.974807352726465.670688823
795564.349777162726397.915553704 795428.92382127726292.011570111
#Sta/Elev= 30
9374.913248.53569452.948236.78479488.805232.85799572.472 225.7529606.272224.9844
9632.234220.31499656.139214.21979661.043213.72719697.557213.18689775.663214.8902
 9811.52212.8741 9907.14214.04819942.997212.97289954.688209.55129966.324208.9891
10048.42209.467610067.71214.352610085.64216.780510096.97221.030510109.46223.6695
10121.94  228.1210146.91228.2878 10159.4231.2062 10202.4235.660810234.87240.2986
10260.32241.4091 10299.8250.215410332.27255.091710361.87 257.47510369.59259.2016
#Mann= 3 , 0 , 0
9374.913  0.0328       09374.913  0.0328       010369.59  0.0328       0
#XS Ineff= 2 , 0
       0                               0
Bank Sta=9374.913,10369.59
Exp/Cntr=0.3,0.1

Type RM Length L Ch R = 1 ,26916.68,479.019200,479.019200,479.019200
XS GIS Cut Line= 6
796609.465743553726526.511557411796475.790429205726478.343776524
796360.447148621726414.098731652796303.402829349726374.797604784
796087.501302361726195.365712136795802.631332278725917.915537179
#Sta/Elev= 30
9325.479279.20549414.293240.67839457.733226.35859490.967218.4998 9502.14217.1352
9524.825212.1124 9559.69208.9891 9717.48208.98979734.591210.88279807.428210.4007
9833.445211.84399859.965210.93379886.544211.80969926.599211.26199953.357208.9891
10038.81208.9891 10062.6210.8733 10090.6211.217910104.61212.670510118.61211.9832
10146.61213.243810174.62219.356810196.44227.520210216.63228.463310225.01230.1161
10253.58251.361110295.75276.825710315.72285.0471   10330287.906110347.68289.2112
#Mann= 3 , 0 , 0
9325.479  0.0301       09325.479  0.0301       010347.68  0.0301       0
#XS Ineff= 2 , 0
       0                               0
Bank Sta=9325.479,10347.68
Exp/Cntr=0.3,0.1

Type RM Length L Ch R = 1 ,26437.66,479.019300,479.019300,479.019300
XS GIS Cut Line= 6
796810.837919088 726455.14408435796742.227773696726364.546652213
796560.453062564 726073.73777625796279.628431499725662.539749622
796018.294811636725258.018934518795974.949183792725195.149369434
#Sta/Elev= 30
9242.423300.61469281.401283.8012 9306.48271.53079318.754266.66339331.028260.0285
9356.133249.48429391.389232.00039415.243  217.929426.969211.99039438.694208.9891
10242.45208.989110253.66210.197910289.37218.489310301.28222.760810313.18225.5889
10325.09230.4105   10337231.836710432.24229.668410467.95232.120210479.86234.6253
10491.76241.262110503.67244.243410518.87250.4126 10537.3255.442610551.29 261.315
10555.73262.225610622.72269.6374 10666.3 275.53710682.32278.769410755.02285.7947
#Mann= 3 , 0 , 0
9242.423  0.0219       09242.423  0.0219       010755.02  0.0219       0
#XS Ineff= 2 , 0
       0                               0
Bank Sta=9242.423,10755.02
Exp/Cntr=0.3,0.1

Type RM Length L Ch R = 1 ,25958.64,479.019200,479.019200,479.019200
XS GIS Cut Line= 6
796889.184762627726437.423521891 796823.99589631726151.106567979
796816.957248777725893.633884802796840.874243617725333.227755114
796819.714107037725087.597868845796771.258333623724839.809327871
#Sta/Elev= 30
9221.159281.24119233.096276.00919245.101270.40419266.456261.63579277.134 257.633
9287.812 253.0729308.641243.41139318.993237.75539339.699227.23779350.051219.5769
9360.337215.00289370.526209.27169380.715208.989110514.36208.989110524.41209.2883
10534.47210.396410544.53 210.68710564.64212.6779 10594.9218.219510645.55220.7272
10655.68220.940210675.95224.138210706.36227.686110716.57229.295610757.44234.8774
 10777.9237.2783 10788.2238.833110808.81242.391110829.42246.487810834.76246.9104
#Mann= 3 , 0 , 0
9221.159  0.0207       09221.159  0.0207       010834.76  0.0207       0
#XS Ineff= 2 , 0
       0                               0
Bank Sta=9221.159,10834.76
Exp/Cntr=0.3,0.1

Type RM Length L Ch R = 1 ,25479.62,888.480400,888.480400,888.480400
XS GIS Cut Line= 6
796842.332266137726732.699886888797139.697264141726057.417119353
797354.486706392725702.103817811797422.711940878725568.833459013
797476.356739981  725435.4651935797519.047117907725289.708043093
#Sta/Elev= 30
9012.927369.96279032.358364.8768 9131.16332.12669186.051318.27639208.007 311.005
9218.985309.02169229.963305.79399295.831282.05129350.721258.98889394.633244.6155
 9416.59235.18189438.546224.18799449.524217.56389460.502212.8976 9471.48209.1117
9479.879208.989110372.37208.989110396.35209.644410407.04213.235110417.73219.2895
10428.42227.475710460.49245.087510492.09260.168110523.43271.413510544.18282.1759
10554.55285.680410564.93286.582810585.68293.975110596.05296.263510611.92297.2172
#Mann= 3 , 0 , 0
9012.927  0.0168       09012.927  0.0168       010611.92  0.0168       0
#XS Ineff= 2 , 0
       0                               0
Bank Sta=9012.927,10611.92
Exp/Cntr=0.3,0.1

Type RM Length L Ch R = 1 ,24591.14,888.480400,888.480400,888.480400
XS GIS Cut Line= 6
798551.644440965727205.862691127798272.024123013726864.300137982
  798100.3269988726465.619933531798041.340713978726123.809811667
798024.725408018725395.443108574797989.189424962725063.091490299
#Sta/Elev= 30
8824.786313.25818867.885 291.616 8884.62283.65548909.082 272.7318922.659265.8711
8936.237259.72018950.967254.38998963.392248.42178980.956242.79748989.928238.0573
8996.318 233.9579003.102230.84429016.275229.14149042.622224.73959068.414217.0167
 9081.18214.83029090.257212.31659106.713208.989110919.77209.1332 10929.8209.8258
10959.97218.519510970.04222.1952 10980.1226.518710990.17229.350711000.24231.3708
11020.38 236.81411040.54241.302111080.96249.234211091.06249.8993 11113.2253.7334
#Mann= 3 , 0 , 0
8824.786  0.0208       08824.786  0.0208       0 11113.2  0.0208       0
#XS Ineff= 2 , 0
       0                               0
Bank Sta=8824.786,11113.2
Exp/Cntr=0.3,0.1

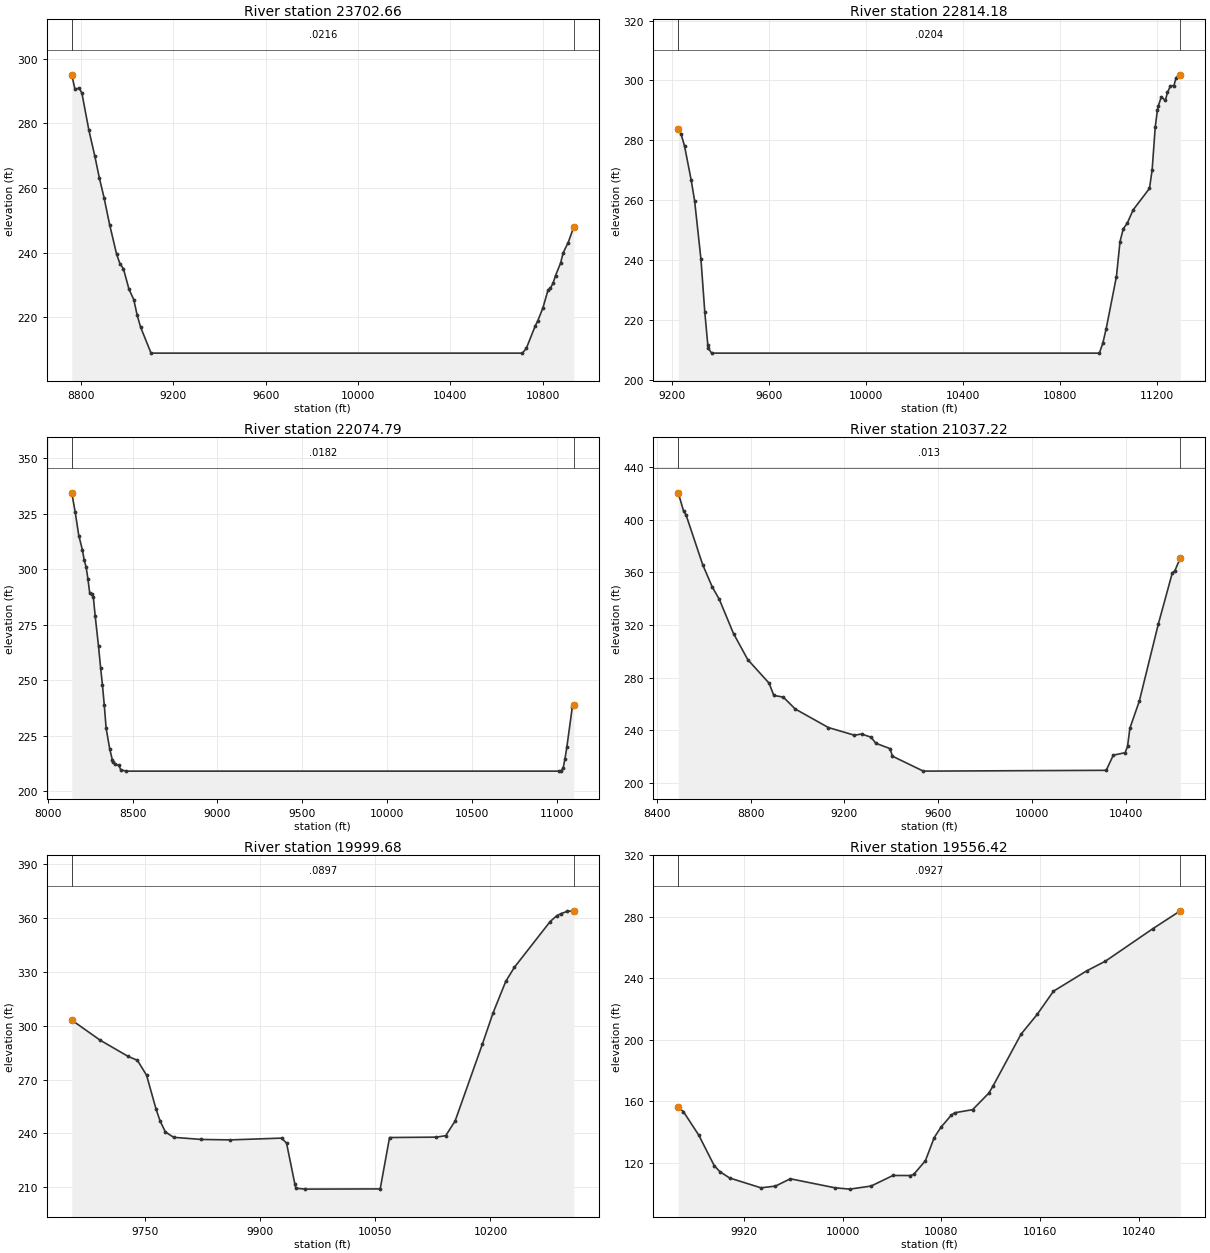
Type RM Length L Ch R = 1 ,23702.66,888.480300,888.480300,888.480300
XS GIS Cut Line= 6
799709.755819352726523.797766016799074.512070179725956.565736726
798641.368400693725631.334420815 798534.23553136 725532.27463536
 798391.48073405725350.571203843798210.091997206724992.546729505
#Sta/Elev= 30
8761.217294.99238774.603290.67198794.063 290.8188805.034289.33578835.367277.8575
8860.839269.93038880.193263.25578901.214256.93558925.019248.70738955.047239.6273
8969.845236.60648984.787235.07559008.881228.73349029.613225.52339044.555220.6186
9059.497 216.9429104.322208.989110711.54208.989110728.44210.471110767.23217.4337
10778.37219.022810800.24 222.983 10822.1228.419210833.04229.134410843.97 230.564
 10854.9232.976210876.76236.829410887.69239.955310909.55243.1731 10934.1248.0193
#Mann= 3 , 0 , 0
8761.217  0.0216       08761.217  0.0216       0 10934.1  0.0216       0
#XS Ineff= 2 , 0
       0                               0
Bank Sta=8761.217,10934.1
Exp/Cntr=0.3,0.1

Type RM Length L Ch R = 1 ,22814.18,739.392900,739.392900,739.392900
XS GIS Cut Line= 6
799893.804297497725599.963087668799708.785162061725419.194212183
 799301.81459102725004.560216933798720.161045641724349.712883368
798577.211794049 724213.29582645798450.293429226724121.336406648
#Sta/Elev= 30
9226.588283.7317 9238.76 282.0179252.585278.11099280.236266.63959294.064259.8716
9320.237240.35719336.174222.61099348.738211.5404 9350.21210.67269364.247208.9891
10962.95208.989110977.05  212.2310991.15217.128111033.44 234.55611048.15246.1897
11061.77250.535211077.88 252.32411102.31256.803411169.73263.966711180.63270.1225
11193.28284.315811202.38290.102711205.93 291.45411218.59294.533311235.02293.3194
11243.89 295.99411256.33298.2113 11270.3298.254211279.66300.984511296.82301.8825
#Mann= 3 , 0 , 0
9226.588  0.0204       09226.588  0.0204       011296.82  0.0204       0
#XS Ineff= 2 , 0
       0                               0
Bank Sta=9226.588,11296.82
Exp/Cntr=0.3,0.1

Type RM Length L Ch R = 1 ,22074.79,1037.567900,1037.567900,1037.567900
XS GIS Cut Line= 6
800622.683867335726353.459857389799962.034635127 724672.65018706
799940.264485329724611.222657725799939.625184238 724609.32758674
 799890.82598272724463.373138294799524.400555909723606.955921054
#Sta/Elev= 30
8141.561334.44438161.396325.93878182.885 315.1978204.375 308.657 8215.12304.0122
8225.864301.08818236.609295.69518247.354289.25388258.099288.81358268.843287.3209
8279.588278.91518299.249 265.1998311.822255.35978322.567 247.6718333.312238.5737
8344.056228.28248365.546218.84938381.258213.91058387.035212.9482 8397.78212.0019
8419.269211.54948430.014209.60558462.248208.989111015.24208.989111026.12 209.222
11036.99210.380711047.87214.547711058.75  219.7611091.38 238.04111100.13238.6618
#Mann= 3 , 0 , 0
8141.561  0.0182       08141.561  0.0182       011100.13  0.0182       0
#XS Ineff= 2 , 0
       09116.443                       0
Bank Sta=8141.561,11100.13
Exp/Cntr=0.3,0.1

Type RM Length L Ch R = 1 ,21037.22,1037.542300,1037.542300,1037.542300
XS GIS Cut Line= 6
802198.094516442724232.043619151801358.208526103724112.575619502
800818.376817247724029.233844726800618.369172067724006.577597051
800310.689691287723953.461679485 800081.31297576723931.253470091
#Sta/Elev= 30
8492.003420.2862 8515.33406.14418525.431403.44258596.136365.74238636.538348.9704
 8666.84339.43678727.444313.45198788.048293.68488878.954275.76558899.155266.4492
8939.558265.18898990.061256.19969131.471242.08849242.578236.2586 9272.88237.1698
9313.282 234.7559333.484230.17279394.183226.07359404.301 220.3469535.841208.9891
10314.93209.601410345.25221.107810395.78223.006810405.85227.8261 10415.9241.5905
10456.09 262.23310536.46320.324810596.74359.643210606.79360.898610630.59 370.883
#Mann= 3 , 0 , 0
8492.003   0.013       08492.003   0.013       010630.59   0.013       0
#XS Ineff= 2 , 0
       0                               0
Bank Sta=8492.003,10630.59
Exp/Cntr=0.3,0.1

Type RM Length L Ch R = 1 ,19999.68,443.258400,443.258400,443.258400
XS GIS Cut Line= 4
800390.226784945723034.488359451800313.837896019723145.599470586
799978.768451601723379.974470586799898.907340497723456.363359451
#Sta/Elev= 30
 9654.42303.16179691.447291.97449727.853  282.969739.988 280.7529751.903272.4354
9764.259253.57569769.554246.93099776.394240.84289787.205237.85489823.104236.6756
 9861.06 236.4269927.784237.41489934.282234.6499 9945.23211.61449946.485209.4777
9958.689208.989110056.32209.108110068.52237.741310129.54237.956110141.74238.7841
10153.95246.956310189.48289.777110203.38307.1721 10219.9324.699910231.05332.5098
10277.77358.073510286.41361.373210292.23362.545310300.24363.807110308.67364.0675
#Mann= 3 , 0 , 0
 9654.42  0.0897       0 9654.42  0.0897       010308.67  0.0897       0
#XS Ineff= 2 , 0
       0                               0
Bank Sta=9654.42,10308.67
Exp/Cntr=0.3,0.1

Type RM Length L Ch R = 1 ,19556.42,740.400300,740.400300,740.400300
XS GIS Cut Line= 6
799998.320069925722824.761823184 799943.77613765722865.680564257
799858.353417342722923.253216472799818.290998891722953.205538489
799755.365603697723006.418410213799678.628484405723075.649022202
#Sta/Elev= 30
9866.641156.01779870.791153.20319883.293  137.819895.794118.00189900.365 114.091
9908.295 109.9469933.693103.54399945.427104.65949957.505109.42669993.739103.5496
10005.78102.6916   10023104.711410040.76111.584310054.51111.540510057.46112.2207
   10067121.195510074.16136.278410079.49142.844710087.86150.730710090.64152.3829
10105.27154.415110118.36165.148210121.61169.500210144.56203.585310157.65216.4631
10170.76231.4755 10197.7244.730210212.94251.072110251.57 272.30610273.62 283.818
#Mann= 3 , 0 , 0
9866.641  0.0927       09866.641  0.0927       010273.62  0.0927       0
#XS Ineff= 2 , 0
       0                               0
Bank Sta=9866.641,10273.62
Exp/Cntr=0.3,0.1