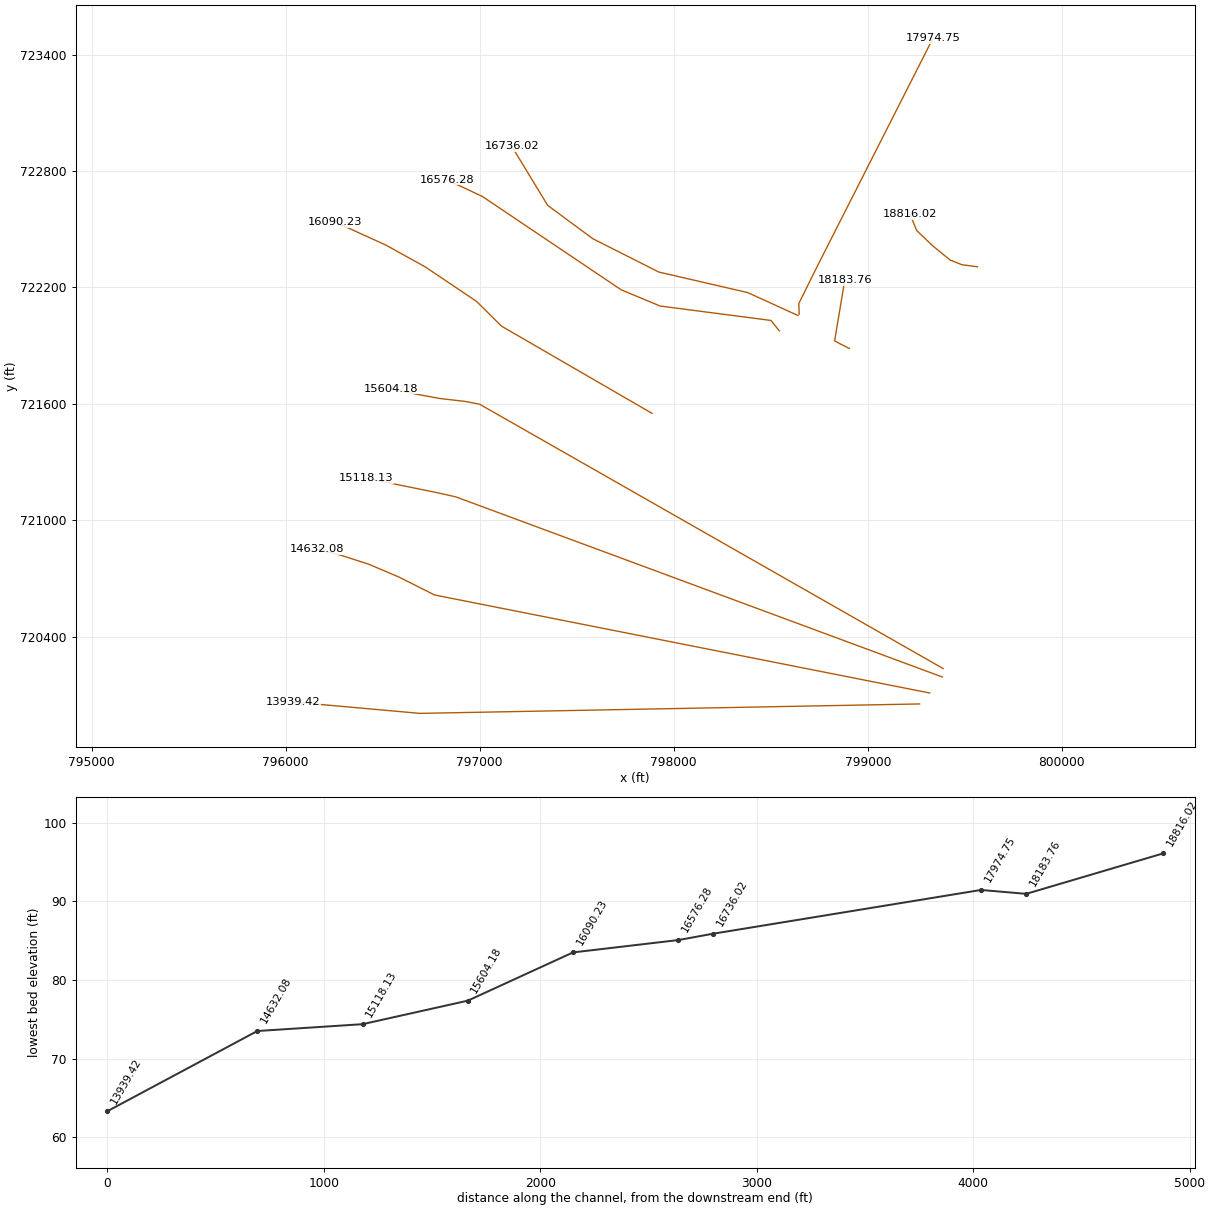
HEC-RAS study 6721_ras.prj: 6721

--- 6721_ras.g01 (geometry) --- (continued)

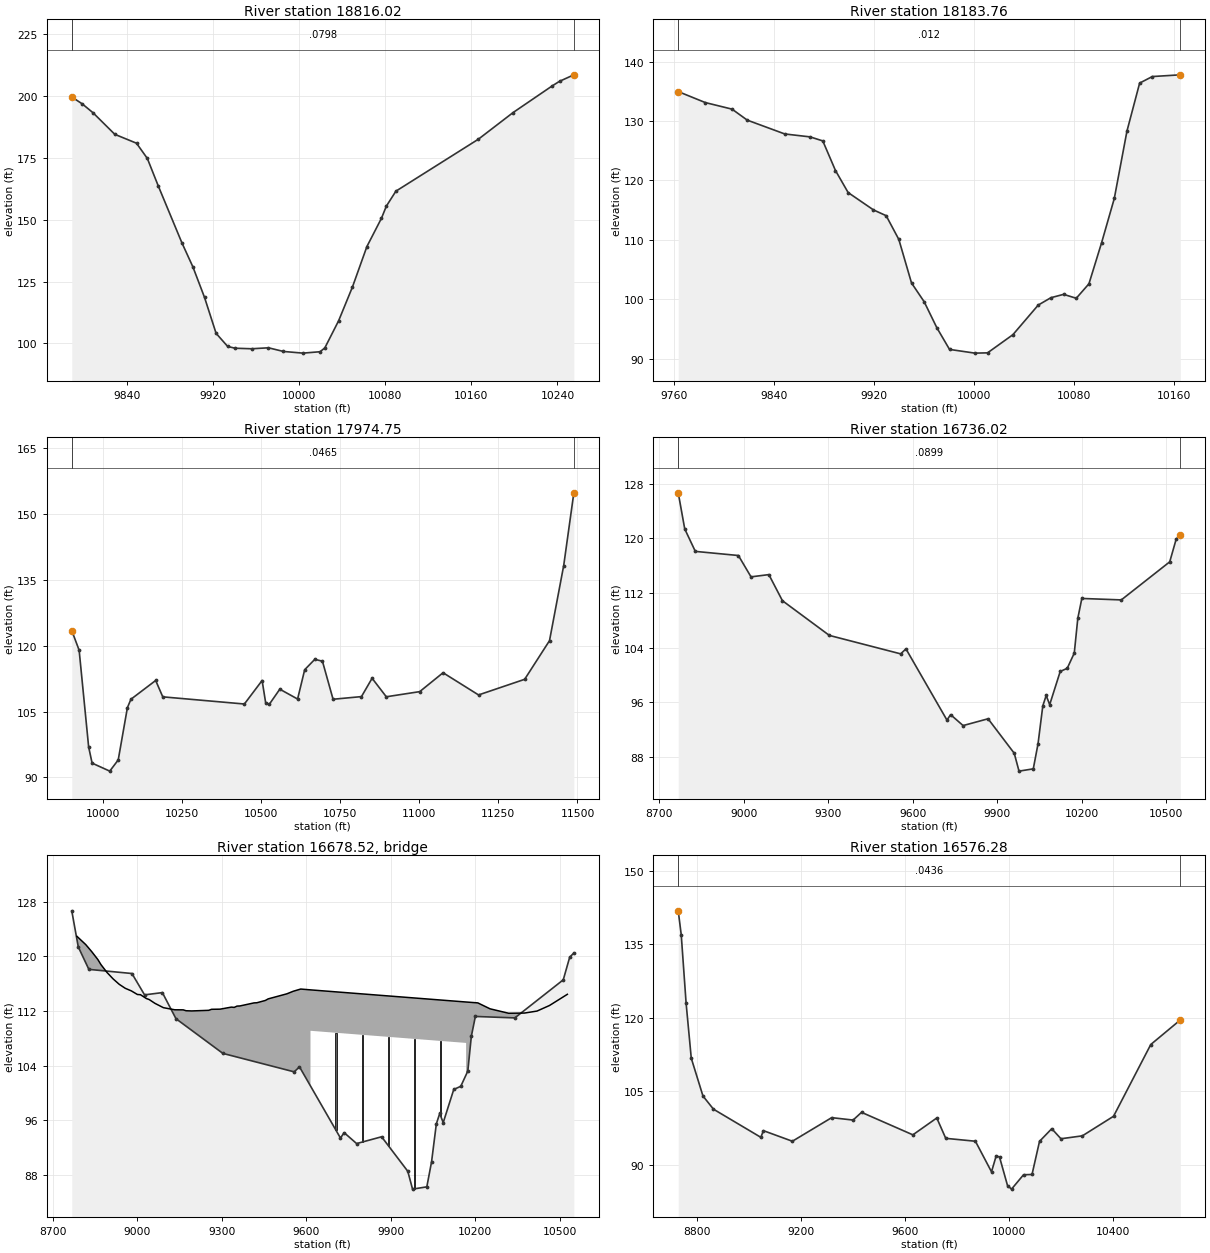
Type RM Length L Ch R = 1 ,18816.02,632.265300,632.265300,632.265300
XS GIS Cut Line= 6
799564.681079796722306.448440127799484.819968685722316.865106794
  799423.9561385722341.210638868 799334.49938819722414.329523482
799251.428822407722493.663398486799217.458857574 722577.28177346
#Sta/Elev= 30
9788.392199.61789798.155196.8173 9808.24193.19799828.409184.51499848.579180.9274
9858.664174.76359868.748 163.7299890.834140.62889901.047130.90519911.817118.6155
9922.588104.08129933.35898.781469940.28398.067699955.591  97.8499971.30798.23805
9985.19796.7626710003.3796.0852910019.28 96.651610023.6898.1953910036.53109.1832
10049.39122.838310062.82139.178410076.28150.539710080.91155.507710089.75161.5361
10166.41182.533610198.79 193.33510235.19 204.11610241.96205.958510255.22208.5647
#Mann= 3 , 0 , 0
9788.392  0.0798       09788.392  0.0798       010255.22  0.0798       0
#XS Ineff= 2 , 0
       0                               0
Bank Sta=9788.392,10255.22
Exp/Cntr=0.3,0.1

Type RM Length L Ch R = 1 ,18183.76,209.008500,209.008500,209.008500
XS GIS Cut Line= 4
798904.339291096721885.744183779798857.464291096721909.181683779
798828.818457723721924.806683779798881.209227383722237.089669883
#Sta/Elev= 30
9763.512134.95239785.134133.10719806.569131.99779818.727130.14959848.746127.8223
9869.025127.32999879.165126.65179889.305121.67379899.444117.96169919.724115.0419
9929.864114.07179940.003110.07149950.143102.75239960.28399.587829970.42395.21472
9980.56291.5709810000.8490.9460310010.9890.9917410031.2694.0476210051.5499.03462
10061.68100.272810071.82100.834310081.96100.1773 10092.1102.611910102.24 109.529
10112.38116.964610122.52 128.31110132.66136.3819 10142.8137.4823 10165.2137.7721
#Mann= 3 , 0 , 0
9763.512   0.012       09763.512   0.012       0 10165.2   0.012       0
#XS Ineff= 2 , 0
       0                               0
Bank Sta=9763.512,10165.2
Exp/Cntr=0.3,0.1

Type RM Length L Ch R = 1 ,17974.75,1238.722800,1238.722800,1238.722800
XS GIS Cut Line= 4
798646.286056003722061.717816249798644.362861937722116.849379479
798731.908365676722293.843550081799335.308441113723483.586455007
#Sta/Elev= 30
9901.908123.44569925.205118.95839955.22396.949839966.16793.2581610021.9591.43879
10048.7393.9889610077.73105.893810088.89107.802210167.04112.075510189.47108.3492
10447.36106.719610503.42112.069410514.63107.008210525.85106.622710559.32110.0944
10615.55107.853810637.97114.524610669.86116.887310694.04116.464310727.67107.8015
10817.37108.404910851.01112.579710895.86108.365211001.48109.537311075.26113.8398
11187.39 108.783 11333.1112.342111411.64121.140611456.49138.243711488.54154.7986
#Mann= 3 , 0 , 0
9901.908  0.0465       09901.908  0.0465       011488.54  0.0465       0
#XS Ineff= 2 , 0
       0                10159.95       0
Bank Sta=9901.908,11488.54
Exp/Cntr=0.3,0.1

Type RM Length L Ch R = 1 ,16736.02,159.743900,159.743900,159.743900
XS GIS Cut Line= 6
798640.060854137722055.244013056798381.380298585722173.299568608
797923.046965271722279.202346385 797582.76918745722451.077346385
797350.130298585722622.952346385797164.567547888722928.004128203
#Sta/Elev= 30
8766.952126.67828790.075121.38198827.682118.0926 8980.71117.48799025.533114.3574
9088.917114.68759137.131110.8605 9303.84105.77249557.216103.06799576.005103.7973
9721.64793.360529734.65794.154399779.01892.552919867.738 93.54919960.76288.49183
9977.67285.87368 10028.486.2077110045.3189.8926910062.22 95.440710074.2496.96321
10086.6495.6197210124.06100.481910149.06100.952710174.06103.185310186.56108.2777
10200.89111.190510341.12110.977510513.16116.561210535.94119.867110550.76120.4993
#Mann= 3 , 0 , 0
8766.952  0.0899       08766.952  0.0899       010550.76  0.0899       0
#XS Ineff= 2 , 0
       09569.082                       0
Bank Sta=8766.952,10550.76
Exp/Cntr=0.3,0.1

Type RM Length L Ch R = 3 ,16678.52,,,
BEGIN DESCRIPTION:
END DESCRIPTION:
Bridge Culvert--1,0,-1,-1, 0
Deck Dist Width WeirC Skew NumUp NumDn MinLoCord MaxHiCord MaxSubmerge Is_Ogee
54.871950,50.000000,2.6,0, 45, 44, , , 0.95, 0, 0,0,,
 8785.56 8816.54 8838.14 8859.74 8870.55 8892.15 8913.75 8935.35 8956.96 8978.56
 9000.16 9010.96 9031.93 9042.00 9062.14 9092.34 9132.62 9162.82 9172.89 9193.03
 9253.44 9263.51 9293.72 9333.99 9344.06 9354.13 9364.20 9414.54 9424.61 9454.81
 9464.88 9531.15 9553.44 9580.25 9615.00 9615.0010168.0010168.0010209.6510253.10
10319.1410375.4010419.8610464.3210527.73
  122.93  121.73  120.68  119.53  118.80  117.64  116.70  115.91  115.32  114.94
  114.41  114.38  113.82  113.67  113.12  112.48  112.17  112.16  112.03  112.00
  112.09  112.24  112.26  112.56  112.52  112.71  112.73  113.18  113.20  113.54
  113.77  114.51  114.88  115.21  115.09  115.09  113.31  113.31  113.18  112.31
  111.66  111.69  111.98  112.80  114.44
 -877.07 -878.27 -879.32 -880.47 -881.20 -882.36 -883.30 -884.09 -884.68 -885.06
 -885.59 -885.62 -886.18 -886.33 -886.88 -887.52 -887.83 -887.84 -887.97 -888.00
 -887.91 -887.76 -887.74 -887.44 -887.48 -887.29 -887.27 -886.82 -886.80 -886.46
 -886.23 -885.49 -885.12 -884.79 -884.91  109.09  107.31 -886.69 -886.82 -887.69
 -888.34 -888.31 -888.02 -887.20 -885.56
 8785.56 8816.54 8838.14 8859.74 8870.55 8892.15 8913.75 8935.35 8956.96 8978.56
 9000.16 9010.96 9031.93 9042.00 9062.14 9092.34 9132.62 9162.82 9172.89 9193.03
 9253.44 9263.51 9293.72 9333.99 9344.06 9354.13 9364.20 9414.54 9424.61 9454.81
 9464.88 9531.15 9575.72 9604.91 9604.9110157.9110157.9110209.6510253.1010319.14
10375.4010419.8610464.3210527.73
  122.93  121.73  120.68  119.53  118.80  117.64  116.70  115.91  115.32  114.94
  114.41  114.38  113.82  113.67  113.12  112.48  112.17  112.16  112.03  112.00
  112.09  112.24  112.26  112.56  112.52  112.71  112.73  113.18  113.20  113.54
  113.77  114.51  115.17  115.13  115.13  113.34  113.34  113.18  112.31  111.66
  111.69  111.98  112.80  114.44
 -877.07 -878.27 -879.32 -880.47 -881.20 -882.36 -883.30 -884.09 -884.68 -885.06
 -885.59 -885.62 -886.18 -886.33 -886.88 -887.52 -887.83 -887.84 -887.97 -888.00
 -887.91 -887.76 -887.74 -887.44 -887.48 -887.29 -887.27 -886.82 -886.80 -886.46
 -886.23 -885.49 -884.83 -884.87  109.13  107.34 -886.66 -886.82 -887.69 -888.34
 -888.31 -888.02 -887.20 -885.56
Pier Skew, UpSta & Num, DnSta & Num=  ,9705.83, 2 ,9695.74, 2 , 0 , 0 , 0 ,,
    4.00    4.00
 -885.20  114.80
    4.00    4.00
 -885.17  114.83
Pier Skew, UpSta & Num, DnSta & Num=  ,9798.66, 2 ,9788.57, 2 , 0 , 0 , 0 ,,
    4.00    4.00
 -885.50  114.50
    4.00    4.00
 -885.46  114.54
Pier Skew, UpSta & Num, DnSta & Num=  ,9891.50, 2 ,9881.41, 2 , 0 , 0 , 0 ,,
    4.00    4.00
 -885.80  114.20
    4.00    4.00
 -885.76  114.24
Pier Skew, UpSta & Num, DnSta & Num=  ,9984.33, 2 ,9974.24, 2 , 0 , 0 , 0 ,,
    4.00    4.00
 -886.10  113.90
    4.00    4.00
 -886.06  113.94
Pier Skew, UpSta & Num, DnSta & Num=  ,10077.16, 2 ,10067.07, 2 , 0 , 0 , 0 ,,
    4.00    4.00
 -886.40  113.60
    4.00    4.00
 -886.36  113.64
BR Coef=-1 , 0 , 0 ,, 0 ,,,0.8,0,1,0,
WSPro=,,,, 1 ,,,, 0 ,,,, 0 ,,,,-1 ,-1 ,-1 , 0 , 0 , 0 , 0 , 0
BC Design=,, 0 ,, 0 ,,,,,,

Type RM Length L Ch R = 1 ,16576.28,486.051400,486.051400,486.051400
XS GIS Cut Line= 6
 798544.00327307721976.019476026798500.600495338722029.838920444
797929.730993003722104.137242213797728.993145764722187.687589437
797013.324743003722668.959290817796831.234214514722754.393017098
#Sta/Elev= 30
8729.441141.84878740.978136.95978759.713122.98398779.518  111.788824.444104.0691
8864.855101.37919046.70395.644259056.80596.999349167.93494.840689318.92299.65525
9401.20399.162469433.698100.73929630.88196.149249722.74599.588529757.19495.43423
9871.19494.842549932.98388.605419950.94891.853139963.75691.626679994.52885.80492
10009.9185.0726910056.0788.0046910088.6588.0608110117.4494.8181210164.4697.40343
10199.7395.3492810282.0295.9423410401.8699.9380410544.93 114.57810658.35119.5857
#Mann= 3 , 0 , 0
8729.441  0.0436       08729.441  0.0436       010658.35  0.0436       0
#XS Ineff= 2 , 0
       09539.286        10195.49       0
Bank Sta=8729.441,10658.35
Exp/Cntr=0.3,0.1

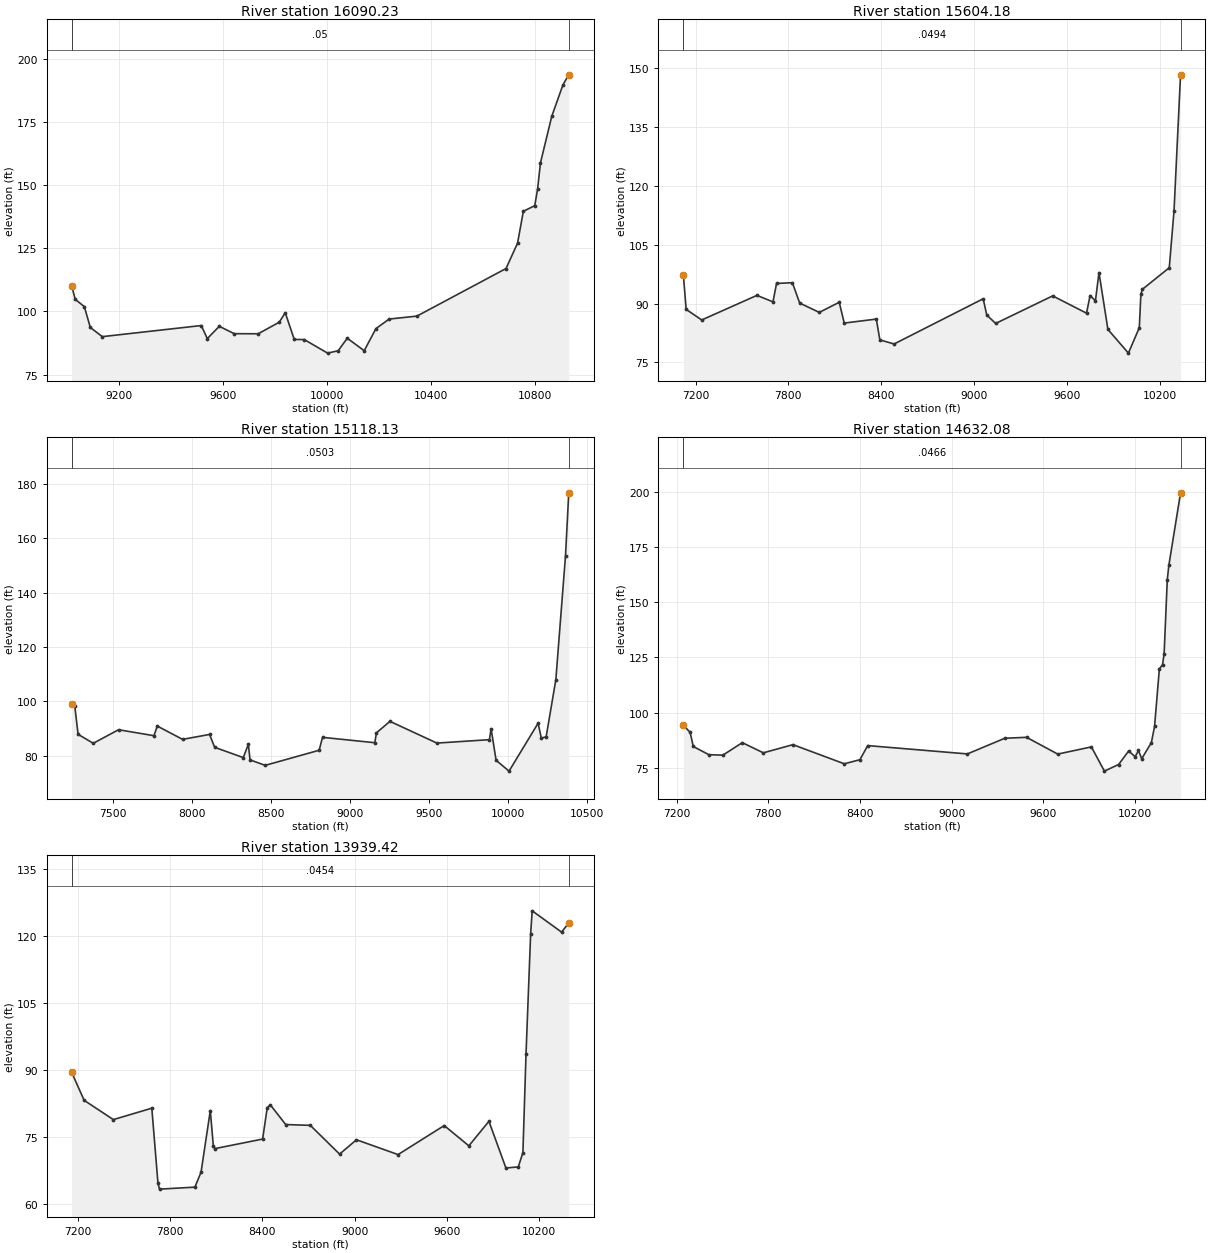
Type RM Length L Ch R = 1 ,16090.23,486.051300,486.051300,486.051300
XS GIS Cut Line= 6
797887.657825679721551.268017098797111.714499831722000.833144695
796984.283016026722127.537001058796719.895814955722305.413666993
796516.777222961722418.000280246796254.511173725722537.357833833
#Sta/Elev= 30
9015.392110.2659 9030.02104.77429064.692101.93479087.80693.666029134.03590.03246
9515.42194.433729538.53689.249289584.76494.12488 9642.55 91.20539735.007 91.1748
9815.90795.760019839.02299.493129873.69388.914649912.16288.8799410002.21 83.5021
10043.1684.4622410077.9389.4179410143.1984.44984 10188.593.2227410239.4697.00099
 10346.498.1699510689.78 117.01910734.28127.088310756.53139.687610800.59141.9373
10811.54148.6235 10822.5158.884910866.09177.333210909.38 189.84910931.55 193.755
#Mann= 3 , 0 , 0
9015.392    0.05       09015.392    0.05       010931.55    0.05       0
#XS Ineff= 2 , 0
       09172.889                       0
Bank Sta=9015.392,10931.55
Exp/Cntr=0.3,0.1

Type RM Length L Ch R = 1 ,15604.18,486.051400,486.051400,486.051400
XS GIS Cut Line= 6
 799388.23652935720235.874498591 796998.91062884721598.508787698
796922.103140701721612.839093475 796793.48496934721627.800906558
 796677.58219568721649.141482062796543.765411246721678.548481185
#Sta/Elev= 30
7121.26897.390867139.689 88.51167240.113 85.81237596.98392.08071 7700.5990.42722
7723.61495.112937826.00395.307677873.26990.11421  7999.9 87.74378128.78890.31998
8161.06785.023428368.28286.043778391.30580.741248483.401 79.70269058.99791.21552
9082.02187.07013 9139.5884.925529507.96291.946919726.68887.546989749.71292.03922
9784.24890.684039807.271 97.88819864.83183.418299997.36877.3696710067.8683.85264
10077.9492.3486810088.09 93.637210261.3999.1172510292.11113.582810334.32148.2466
#Mann= 3 , 0 , 0
7121.268  0.0494       07121.268  0.0494       010334.32  0.0494       0
#XS Ineff= 2 , 0
       09030.716                       0
Bank Sta=7121.268,10334.32
Exp/Cntr=0.3,0.1

Type RM Length L Ch R = 1 ,15118.13,486.051300,486.051300,486.051300
XS GIS Cut Line= 6
799383.896251589720192.471720815796877.005789747721120.695892558
796792.230737391 721139.66616935796790.276895789721140.093373042
796775.006524309721143.402062595796414.880953506721216.795288814
#Sta/Elev= 30
7238.90999.204577259.05998.475277280.38687.917337376.35884.61475 7536.3189.59883
7760.24387.40683 7781.5790.940217941.52286.058668112.13887.869158144.12983.13788
8325.40879.359018357.398 84.23598368.06278.520218464.03376.502418805.26582.05981
8826.59286.80242 9157.1684.826629167.82388.464699253.13192.681369550.13384.68961
9882.27785.94847 9892.9489.970579924.43178.37999 10006.474.3827610190.1391.99344
10210.5486.5294310241.1586.9928810302.39107.975110363.62153.630110384.15176.6804
#Mann= 3 , 0 , 0
7238.909  0.0503       07238.909  0.0503       010384.15  0.0503       0
#XS Ineff= 2 , 0
       09004.831                       0
Bank Sta=7238.909,10384.15
Exp/Cntr=0.3,0.1

Type RM Length L Ch R = 1 ,14632.08,692.656000,692.656000,692.656000
XS GIS Cut Line= 6
799318.792084932720110.006443024796767.039047148 720615.14111408
796584.044351524 720707.39167078796427.843595956720773.775146786
796281.603898742720820.810942961796160.550608907720850.830899491
#Sta/Elev= 30
7243.83394.238547288.47591.095467308.86384.677477410.80380.96027 7502.5580.74617
7630.02486.402327767.59581.801197961.28285.499968297.68576.829478399.626 78.6818
8450.59685.073759103.01581.303339347.673 88.39669490.389 88.8212 9694.2781.22749
9914.64484.487749999.71673.5136410092.8376.5114910158.4782.62069 10201.480.05153
10222.8282.8611410243.9879.1260410307.2186.4208610328.1193.7628410359.46119.7897
10380.29121.742510390.63126.536510411.33160.134910421.67166.7354 10498.2199.5197
#Mann= 3 , 0 , 0
7243.833  0.0466       07243.833  0.0466       0 10498.2  0.0466       0
#XS Ineff= 2 , 0
       08912.932                       0
Bank Sta=7243.833,10498.2
Exp/Cntr=0.3,0.1

Type RM Length L Ch R = 1 ,13939.42,765.498100,765.498100,765.498100
XS GIS Cut Line= 5
799266.708751559720053.582831919796690.879540443720004.999999985
796138.651045151720054.618144446 796045.83768067720062.519091976
796038.182846571720062.908142626
#Sta/Elev= 30
7160.49589.523837242.21883.194217432.252 78.87137682.29781.428067722.30464.62396
7732.30563.320087962.34663.762028002.35467.125648062.36480.896288082.36872.87693
 8092.3772.382728402.42574.52048 8432.4381.547518452.43482.176718552.45177.76926
 8712.4877.585738902.51471.154739012.533 74.35999282.58171.048849582.63577.54085
9742.68673.008799873.20978.490629983.65268.0529210063.97 68.2849 10094.171.49378
10114.1893.49319 10144.3120.368410154.34125.574710345.08120.821510392.05122.8465
#Mann= 3 , 0 , 0
7160.495  0.0454       07160.495  0.0454       010392.05  0.0454       0
#XS Ineff= 2 , 0
       08822.142                       0
Bank Sta=7160.495,10392.05
Exp/Cntr=0.3,0.1