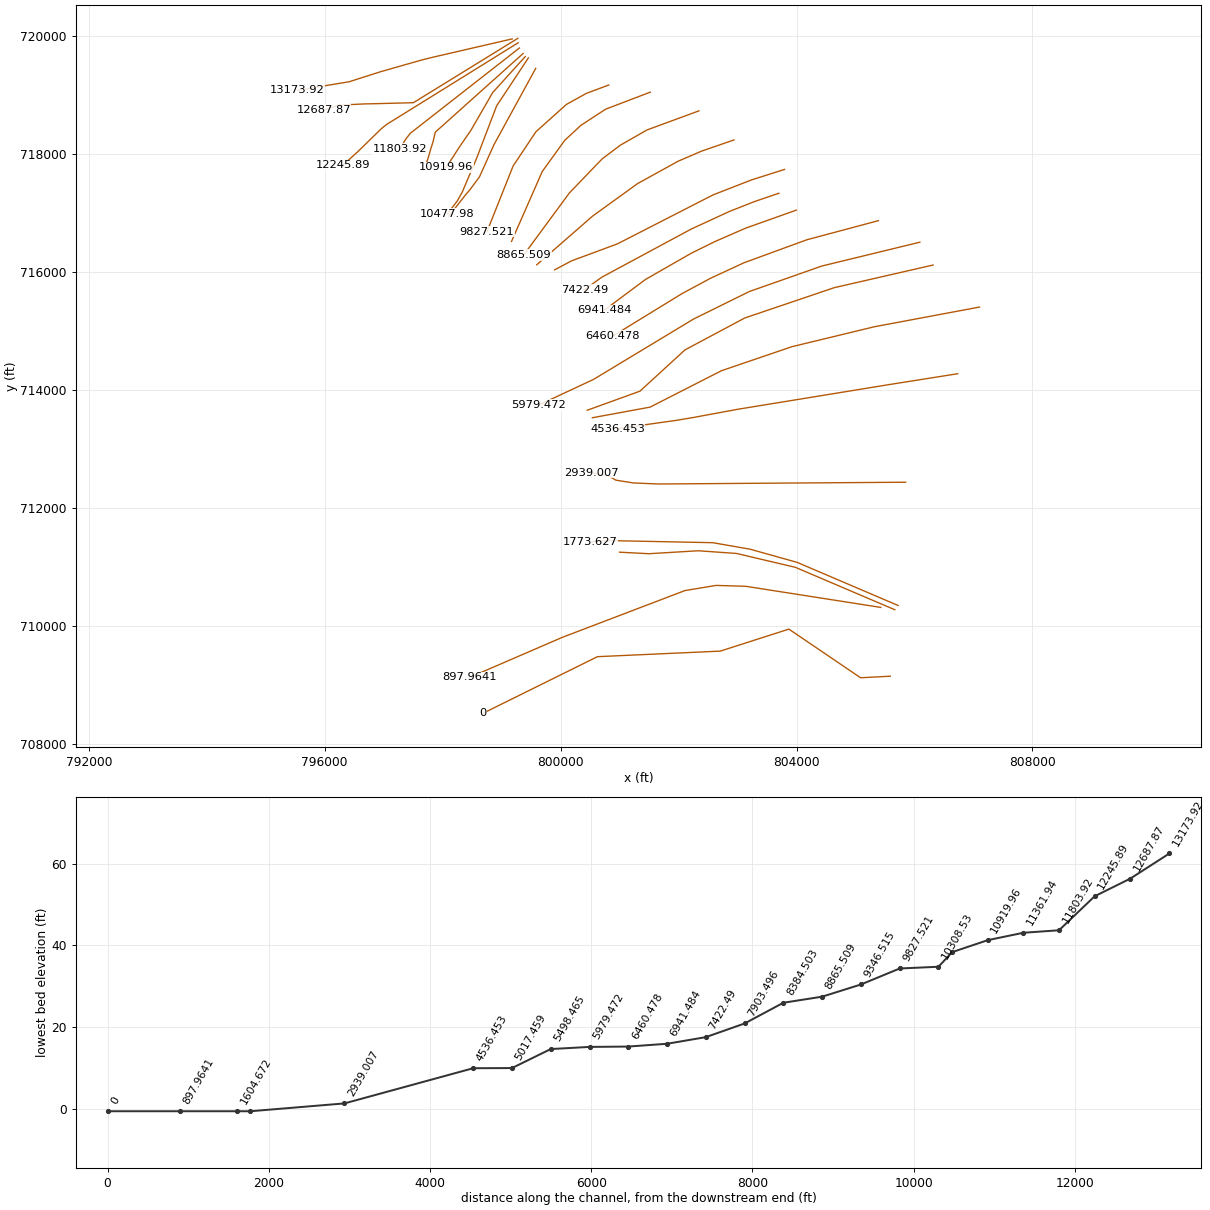
HEC-RAS study 6721_ras.prj: 6721

--- 6721_ras.g01 (geometry) --- (continued)

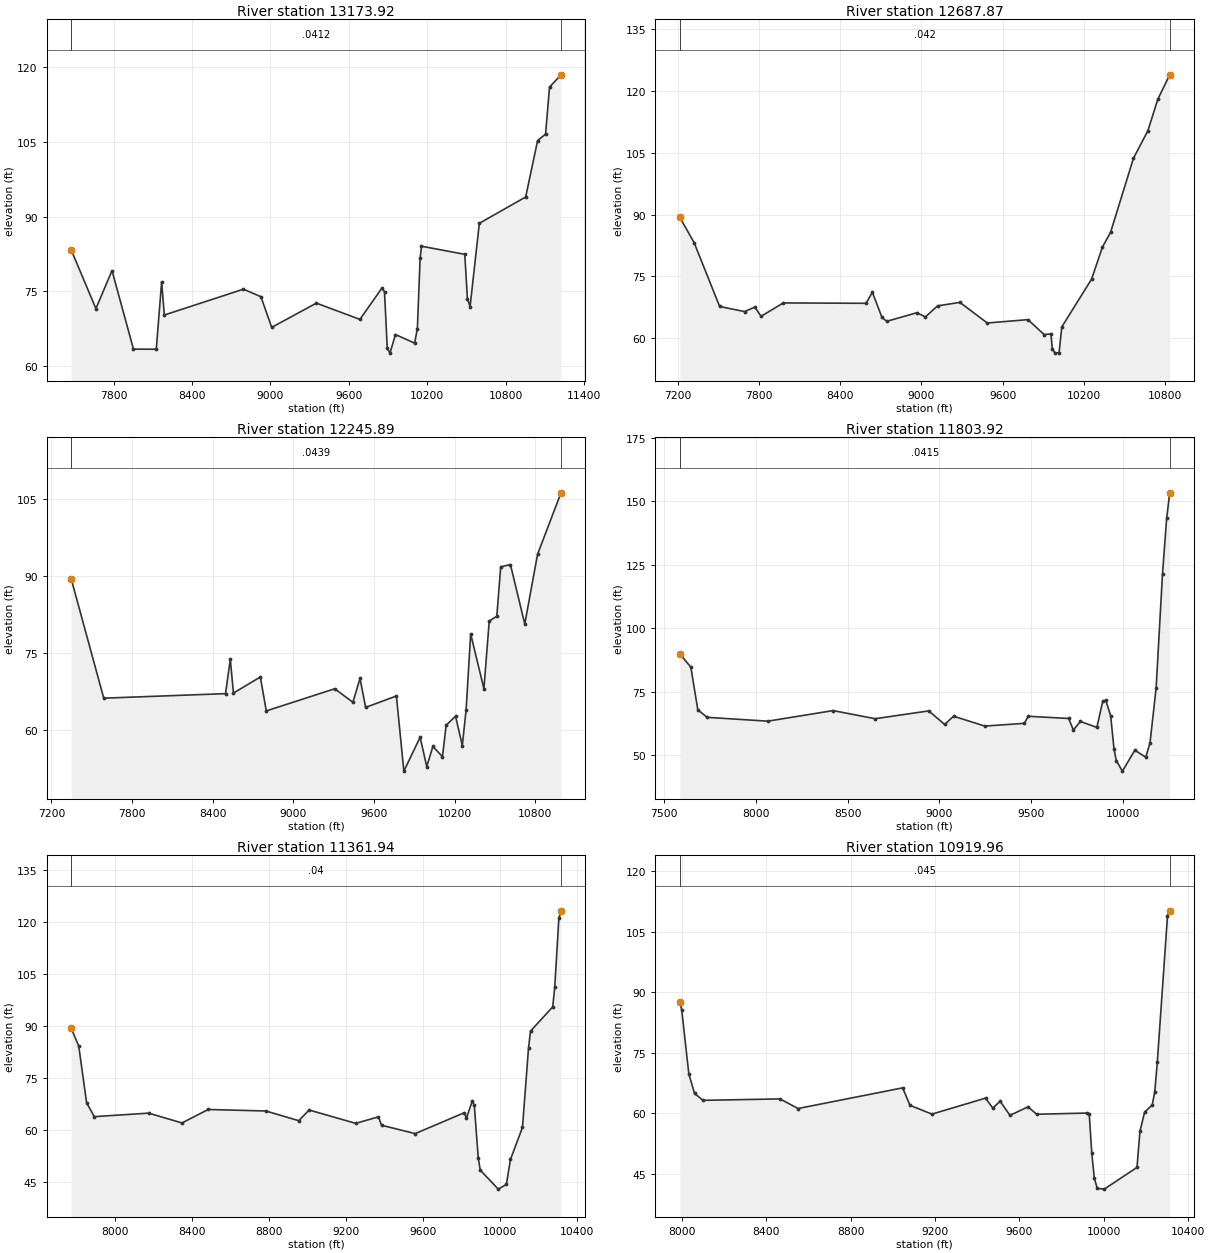
Type RM Length L Ch R = 1 ,13173.92,486.051400,486.051400,486.051400
XS GIS Cut Line= 6
799179.541892856719956.207531482797830.268828064719644.369847789
797638.499854237719596.491622314 796950.07418254719400.159909442
796412.637090236719228.904636547795538.410140485719085.700887457
#Sta/Elev= 30
7475.28783.319627664.71371.482837787.88979.133057952.12363.341368126.62263.32008
8167.68176.86103 8188.2170.198678793.76675.39392  8927.473.879559009.85667.71407
9351.89672.589819685.15869.316859852.24475.573989873.17374.906699894.10363.57135
9915.032 62.5361 9956.8966.2746910103.5664.5491310124.62 67.467710145.6981.59249
10156.2284.0334910487.3882.4013510507.6573.5104910527.9171.8898610598.8588.64097
10953.5193.9338311044.71  105.2811105.51106.562111135.91116.023911223.65118.4941
#Mann= 3 , 0 , 0
7475.287  0.0412       07475.287  0.0412       011223.65  0.0412       0
#XS Ineff= 2 , 0
       09141.754                       0
Bank Sta=7475.287,11223.65
Exp/Cntr=0.3,0.1

Type RM Length L Ch R = 1 ,12687.87,441.977100,441.977100,441.977100
XS GIS Cut Line= 6
799274.768608732719965.544938966797503.935275396718874.399105632
796864.033655025718857.689036187796679.137821692718853.782786187
796236.429488358718832.949452854795981.517269741 718751.29531891
#Sta/Elev= 30
 7217.3489.304277322.78283.154097510.71767.684567694.94566.450327771.19667.54379
7816.11265.293247980.88568.549448591.34568.458948638.32871.134328708.80465.06143
8744.042 64.08218967.21566.17001 9029.3365.143029119.91267.835159284.35668.68776
9486.35263.673069786.45464.494479906.49560.85358 9956.5161.039299966.51257.39412
9986.51756.3586510016.5256.4844710036.5362.72513 10256.774.3451110336.7882.13288
10396.8585.7098810565.61103.682910672.11110.369110745.62118.033910833.28123.9386
#Mann= 3 , 0 , 0
 7217.34   0.042       0 7217.34   0.042       010833.28   0.042       0
#XS Ineff= 2 , 0
       09306.299                       0
Bank Sta=7217.34,10833.28
Exp/Cntr=0.3,0.1

Type RM Length L Ch R = 1 ,12245.89,441.977100,441.977100,441.977100
XS GIS Cut Line= 6
799280.999116153719890.807947651797062.112350643718513.175503209
796996.224164337718463.314908668796952.611071855718425.561506003
796562.174243689718045.049715981 796305.38814194717811.094195069
#Sta/Elev= 30
7346.71389.526277589.18766.247548495.22767.130128530.83773.803518554.37867.25265
8754.479 70.37058798.56163.766129307.69868.078179443.14665.454199496.02870.09251
9537.93864.453289766.752 66.67469822.31352.032799943.31158.641649992.52252.92454
10038.3256.8540510109.3454.8502310137.0560.9783610206.7662.74056 10257.257.02186
10285.6164.0365510319.4178.7707710417.97 68.083510457.3581.26294 10513.982.21994
10542.8391.8351410615.1592.28254 10721.980.7047510817.2894.29983 10991.4106.2576
#Mann= 3 , 0 , 0
7346.713  0.0439       07346.713  0.0439       0 10991.4  0.0439       0
#XS Ineff= 2 , 0
       0 9459.23                       0
Bank Sta=7346.713,10991.4
Exp/Cntr=0.3,0.1

Type RM Length L Ch R = 1 ,11803.92,441.977100,441.977100,441.977100
XS GIS Cut Line= 6
799301.832449496719802.266280979797453.295764327 718357.47054714
797383.954472631718269.742181912797351.017796218718220.138322324
797322.185740203718169.047215044797280.218964238718090.333185896
#Sta/Elev= 30
7587.577 89.79757647.01784.687887685.093 67.84657735.86164.887068065.85463.37575
8421.23267.542198649.688 64.34228941.60667.418079028.38962.079279077.10565.32236
9246.21561.44145 9461.9862.516489483.07565.301059703.12964.434979728.51359.89496
9766.58963.257299856.56660.913059889.044 71.36999905.28371.537829931.58565.49794
 9949.6152.52011 9962.33 47.77929995.71843.6984910063.2751.95758 10122.549.16199
10145.46 54.709610179.0576.47342 10213.7121.436810236.36143.312910252.98153.3023
#Mann= 3 , 0 , 0
7587.577  0.0415       07587.577  0.0415       010252.98  0.0415       0
#XS Ineff= 2 , 0
       0 9899.43                       0
Bank Sta=7587.577,10252.98
Exp/Cntr=0.3,0.1

Type RM Length L Ch R = 1 ,11361.94,441.977100,441.977100,441.977100
XS GIS Cut Line= 6
799364.332449496719708.516280979797875.453999877718374.940445706
797834.754189134718203.434758514797802.066533536718103.710655198
 797755.57167998717942.409537271797724.941660999 717854.65934747
#Sta/Elev= 30
7774.90789.408967814.28584.253377855.11967.950277894.83463.947978176.75664.96396
8349.73162.133868485.527 66.0124 8784.3965.580238955.39762.792499009.21365.85986
9250.74362.021069368.93163.896439384.992 61.47669559.51559.064349814.75265.09333
 9825.0363.448069855.86368.528339866.14167.190529886.69652.028649896.97448.57127
9990.358 43.089710032.4944.4389810053.5651.6176510116.0260.8526210147.2483.66331
10157.6588.5622910272.8195.5448610283.36101.167910304.65120.993610315.75123.1872
#Mann= 3 , 0 , 0
7774.907    0.04       07774.907    0.04       010315.75    0.04       0
#XS Ineff= 2 , 0
       0 9845.23                       0
Bank Sta=7774.907,10315.75
Exp/Cntr=0.3,0.1

Type RM Length L Ch R = 1 ,10919.96,441.977100,441.977100,441.977100
XS GIS Cut Line= 6
799400.790782809719656.432947651798848.707449496719047.057947651
798481.594628483718410.729057908798270.923316956  718103.8765717
798171.302074611717947.479370236 798056.46362433717776.130600132
#Sta/Elev= 30
7991.53887.595548000.16285.621258033.95269.77571 8060.9464.947888101.42163.24855
8465.751 63.60278551.24161.222369047.08566.335779081.71962.017849185.62359.83946
 9439.6163.791589474.24561.326059508.87963.03709 9555.4959.53564 9641.2561.63825
 9681.5759.806429919.32760.098059931.19559.770659943.04250.181969954.88844.06268
 9969.0341.4599910002.2641.2756910157.2546.6562110171.3255.5722610193.3660.32098
10229.4862.0954110241.5165.3647710253.5572.6986410301.71108.827110312.38110.1489
#Mann= 3 , 0 , 0
7991.538   0.045       07991.538   0.045       010312.38   0.045       0
#XS Ineff= 2 , 0
       09844.961                       0
Bank Sta=7991.538,10312.38
Exp/Cntr=0.3,0.1

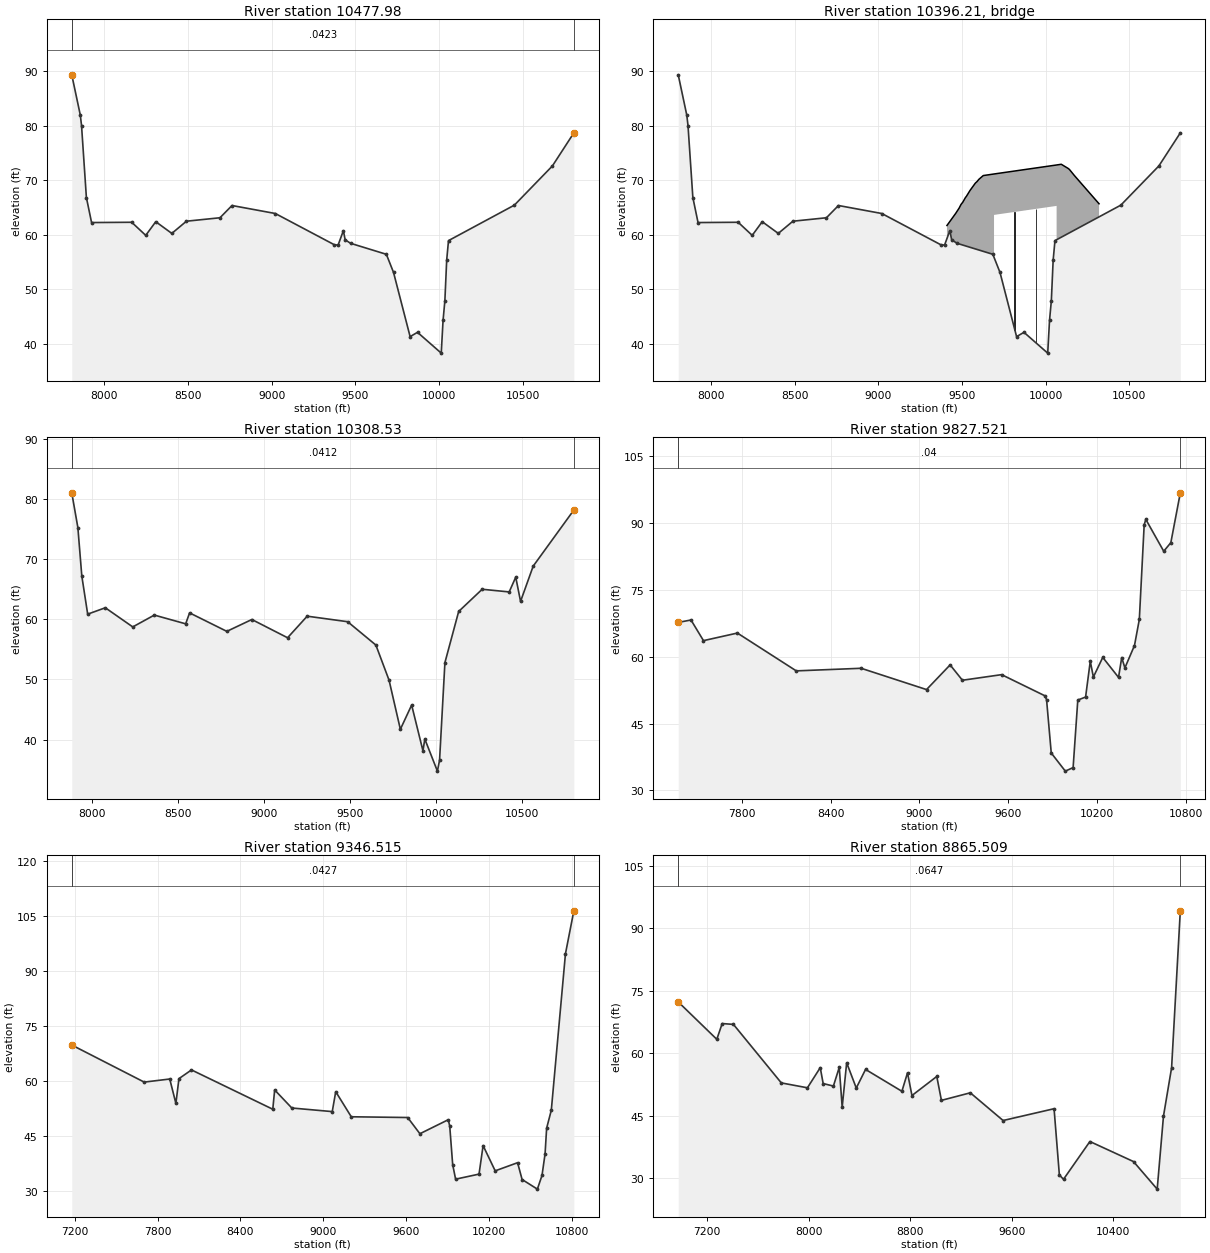
Type RM Length L Ch R = 1 ,10477.98,169.457100,169.457100,169.457100
XS GIS Cut Line= 6
799453.194534657719633.684406559798915.000090212718820.316351003
798573.555600985717926.501816589798331.273119297717356.337099761
798245.295229101717203.996906557798078.194534656716986.983017668
#Sta/Elev= 30
7804.69289.340817855.786  81.9527863.06980.045847892.02966.859097923.02462.26855
8162.84362.31897 8246.7859.922048306.73562.424168402.66260.278378490.04962.51474
8690.445 63.14688762.39165.391139021.19563.926599374.45458.191869396.49258.14054
9427.97860.776639438.68259.108769470.79758.466149684.89356.448959727.71253.13103
9826.84741.364029871.03742.1504610012.8938.3382510023.7344.3203110034.5847.93105
10045.4255.3739610056.2758.9578910449.9165.4576910677.2572.64288 10805.478.70117
#Mann= 3 , 0 , 0
7804.692  0.0423       07804.692  0.0423       0 10805.4  0.0423       0
#XS Ineff= 2 , 0
       09637.013                       0
Bank Sta=7804.692,10805.4
Exp/Cntr=0.3,0.1

Type RM Length L Ch R = 3 ,10396.21,,,
BEGIN DESCRIPTION:
END DESCRIPTION:
Bridge Culvert--1,0,-1,-1, 0
Deck Dist Width WeirC Skew NumUp NumDn MinLoCord MaxHiCord MaxSubmerge Is_Ogee
60.228550,49.000000,2.6,0, 21, 21, , , 0.95, 0, 0,0,,
 9410.71 9462.51 9483.91 9494.60 9505.30 9521.36 9526.70 9548.10 9580.19 9590.89
 9601.59 9627.60 9692.08 9692.0810066.0810066.0810093.9410136.5110143.4510171.87
10319.69
   61.73   63.93   64.94   65.58   66.00   66.86   67.06   68.13   69.49   69.79
   70.19   70.88   71.17   71.17   72.82   72.82   72.95   72.16   71.97   70.90
   65.71
 -938.27 -936.07 -935.06 -934.42 -934.00 -933.14 -932.94 -931.87 -930.51 -930.21
 -929.81 -929.12 -928.83   63.67   65.32 -927.18 -927.05 -927.84 -928.03 -929.10
 -934.29
 9410.71 9462.51 9483.91 9494.60 9505.30 9521.36 9526.70 9548.10 9580.19 9590.89
 9601.59 9627.60 9664.43 9664.4310038.4310038.4310093.9410136.5110147.7010171.87
10319.69
   61.73   63.93   64.94   65.58   66.00   66.86   67.06   68.13   69.49   69.79
   70.19   70.88   71.05   71.05   72.70   72.70   72.95   72.16   71.83   70.90
   65.71
 -938.27 -936.07 -935.06 -934.42 -934.00 -933.14 -932.94 -931.87 -930.51 -930.21
 -929.81 -929.12 -928.95   63.55   65.20 -927.30 -927.05 -927.84 -928.17 -929.10
 -934.29
Pier Skew, UpSta & Num, DnSta & Num=  ,9816.08, 2 ,9788.43, 2 , 0 , 0 , 0 ,,
    4.00    4.00
 -928.28   71.72
    4.00    4.00
 -928.40   71.60
Pier Skew, UpSta & Num, DnSta & Num=  ,9942.08, 2 ,9914.43, 2 , 0 , 0 , 0 ,,
    4.00    4.00
 -927.72   72.28
    4.00    4.00
 -927.85   72.15
BR Coef=-1 , 0 , 0 ,, 0 ,,,0.8,0,1,0,
WSPro=,,,, 1 ,,,, 0 ,,,, 0 ,,,,-1 ,-1 ,-1 , 0 , 0 , 0 , 0 , 0
BC Design=,, 0 ,, 0 ,,,,,,

Type RM Length L Ch R = 1 ,10308.53,481.006200,481.006200,481.006200
XS GIS Cut Line= 6
 799577.54349299719456.167045447798869.861201323718162.257901928
798624.487768896717617.913894281798463.936599404717399.855524042
798393.819534656717319.393318594798104.236201323716948.716235261
#Sta/Elev= 30
7882.16580.998377917.68975.213547940.48567.186637974.67960.84059 8077.2661.90018
8236.832 58.71818362.20960.684218544.57759.232538567.37361.050738783.93457.98027
8929.45459.950879137.27156.917719251.25160.502369486.60159.583169650.78655.70147
9727.40549.866919793.07941.707889858.75345.735649924.42738.137139935.37340.08627
10008.5534.7575910021.1336.5828910052.2252.7908510132.2261.2857510268.94 64.9746
10426.0364.53284 10464.166.9888410492.1462.9641410565.6268.8202210802.0178.13943
#Mann= 3 , 0 , 0
7882.165  0.0412       07882.165  0.0412       010802.01  0.0412       0
#XS Ineff= 2 , 0
       0                               0
Bank Sta=7882.165,10802.01
Exp/Cntr=0.3,0.1

Type RM Length L Ch R = 1 ,9827.521,481.006200,481.006200,481.006200
XS GIS Cut Line= 6
800816.968191862719174.454305395800434.337445021719031.496502668
  800097.8292014718844.682134554799581.591248274718382.156331629
799194.476966202717801.155520976798750.199338078716685.011997119
#Sta/Elev= 30
7370.928 67.65887457.21568.19885 7541.4363.572857770.47465.272388168.32956.79656
8606.59357.378829048.37952.607149207.71958.136089290.82854.69632  9555.655.95205
9848.73951.202629859.29350.335389890.95438.394239985.93834.3319410038.6635.12402
10070.2650.2573410122.9350.9348210154.5358.95199 10175.655.4213810238.9259.81568
10345.4755.3362610366.9859.7823910388.4857.4660310453.2362.4820210485.9768.31578
 10518.789.5011210529.6290.7560610650.8283.6048610698.7985.5260410762.8596.69577
#Mann= 3 , 0 , 0
7370.928    0.04       07370.928    0.04       010762.85    0.04       0
#XS Ineff= 2 , 0
       0                               0
Bank Sta=7370.928,10762.85
Exp/Cntr=0.3,0.1

Type RM Length L Ch R = 1 ,9346.515,481.006200,481.006200,481.006200
XS GIS Cut Line= 6
801520.382210523719053.232097477800761.082478732718763.350313574
800344.082868218718490.464143172800069.454604179718235.676656187
799688.760803074717708.075932056799167.683724105716522.251913682
#Sta/Elev= 30
7178.03669.751977702.83759.629847887.97260.470747932.47653.812657954.72760.57593
8045.56862.95471 8634.5652.222068648.26157.489858772.424 52.55819065.441 51.5753
9090.73557.015849203.25750.164519612.05149.959919700.56845.533419906.07349.35953
9916.75347.624389938.08537.115279959.30433.1283110129.1634.5094810158.5142.29681
10246.21 35.398910408.45  37.62610441.1233.0382610551.8330.4102410585.4134.14401
10607.6240.04295 10618.947.0378210652.7751.9520310755.34 94.6741 10816.1106.3893
#Mann= 3 , 0 , 0
7178.036  0.0427       07178.036  0.0427       0 10816.1  0.0427       0
#XS Ineff= 2 , 0
       0                10205.52       0
Bank Sta=7178.036,10816.1
Exp/Cntr=0.3,0.1

Type RM Length L Ch R = 1 ,8865.509,481.006200,481.006200,481.006200
XS GIS Cut Line= 6
802345.786116868718736.443495452801464.911424309718412.390614629
801014.289640248718155.066218212800702.672523439717920.600899845
800148.889262229717344.391874805799373.173071742716291.254904196
#Sta/Elev= 30
6971.08672.330667275.171 63.36277317.47367.140917406.20566.939227783.64452.90311
7989.49551.73198  8090.756.563078113.517 52.75118194.29952.14482 8240.4656.63222
 8263.5447.087698298.85357.737528374.50751.674418447.74256.135598734.19250.89463
8778.621 55.33458813.35449.872869009.22954.447579045.83948.715599273.62750.52952
9532.08643.883029933.86946.712559975.60730.8273410008.1929.78209 10216.3  38.846
10560.0934.03434 10746.827.4241710796.3244.9313910860.3456.5348210929.03   94.18
#Mann= 3 , 0 , 0
6971.086  0.0647       06971.086  0.0647       010929.03  0.0647       0
#XS Ineff= 2 , 0
       0                10609.69       0
Bank Sta=6971.086,10929.03
Exp/Cntr=0.3,0.1

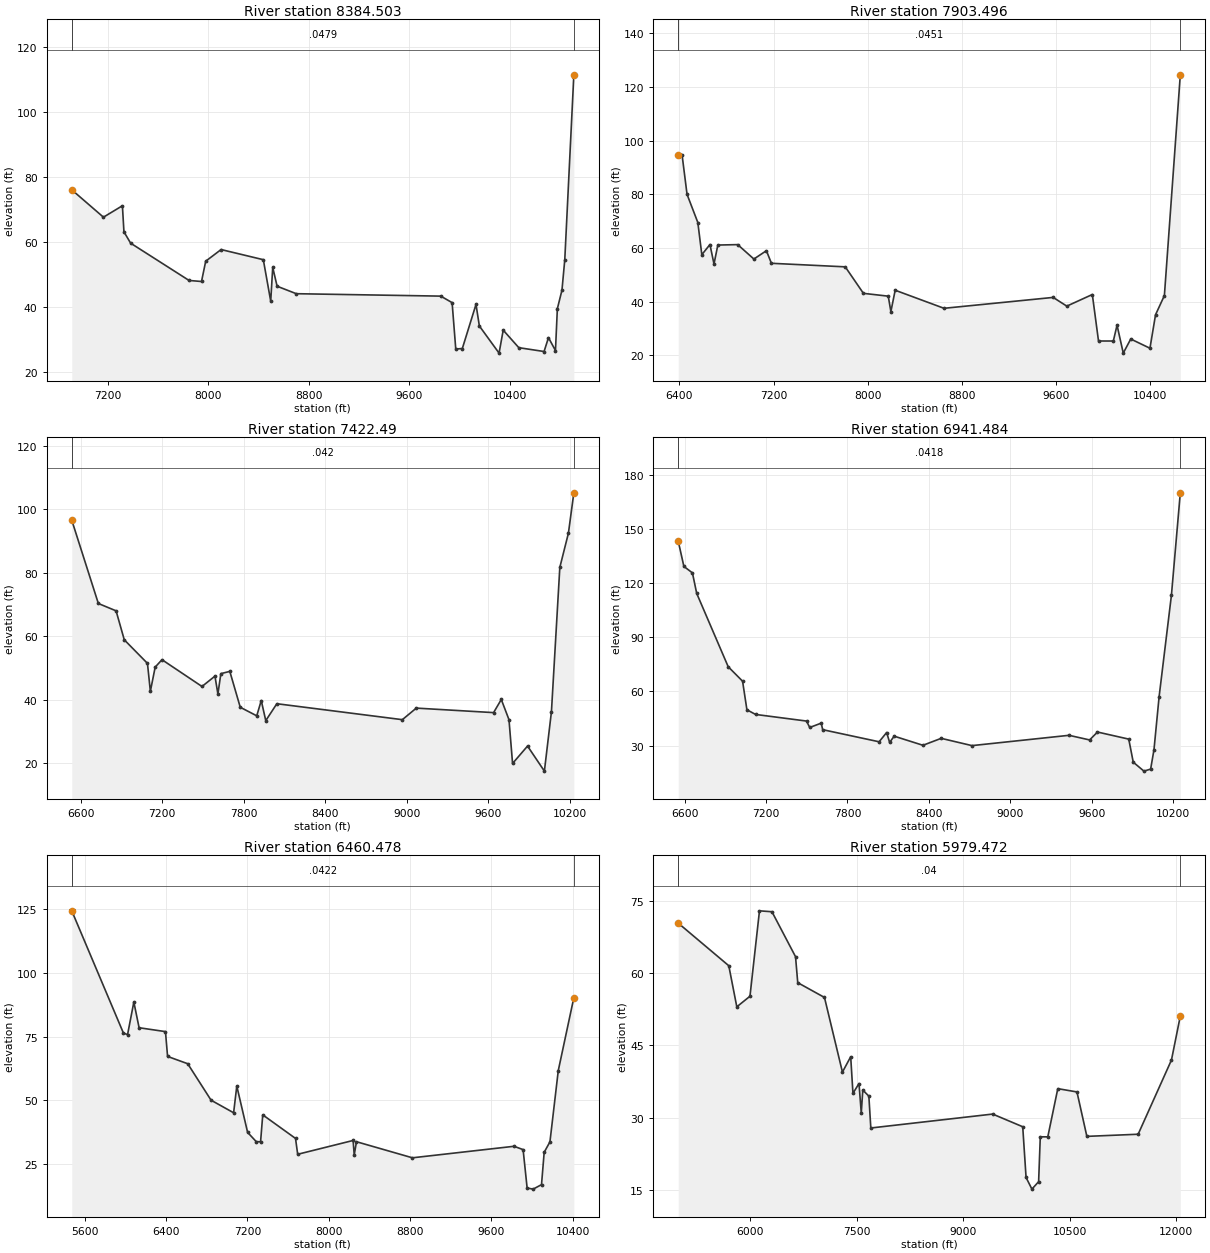
Type RM Length L Ch R = 1 ,8384.503,481.006200,481.006200,481.006200
XS GIS Cut Line= 6
802938.696858764718242.738266692802391.093442768718053.602937073
801992.063849807717882.037688121 801305.52685076717502.988596842
800542.186670154716951.547477156 799595.30338347716126.262082994
#Sta/Elev= 30
6915.02776.060727167.15967.659747318.16971.173087330.335 63.16827383.67359.68492
7848.91448.238877947.92847.919957981.33754.152868103.83757.726598440.01954.61034
8498.89841.891638514.89552.246668549.79146.467478702.49944.172639852.78143.43055
9943.03841.429079972.09427.1931610024.35  27.34810133.1940.88387   1016034.26581
10316.8425.9335410349.8332.9854510474.0727.6063610675.1126.4311610710.2430.68576
10765.8526.7265310780.9239.5703410817.5845.2488210840.0854.6447910912.17111.3564
#Mann= 3 , 0 , 0
6915.027  0.0479       06915.027  0.0479       010912.17  0.0479       0
#XS Ineff= 2 , 0
       0                               0
Bank Sta=6915.027,10912.17
Exp/Cntr=0.3,0.1

Type RM Length L Ch R = 1 ,7903.496,481.006200,481.006200,481.006200
XS GIS Cut Line= 6
803796.769083895717742.955896834 803236.97543788717565.610514581
802583.894069344717310.807597816800962.995404392716480.885063246
800185.069929898716192.737753525799898.920736104716040.776568696
#Sta/Elev= 30
6390.53294.798136423.57194.517326465.38779.97042    655769.488736590.83457.50735
6659.92561.291456694.23454.052436726.91361.099576895.56561.25905  7033.155.89634
7139.47758.991727182.02854.305417809.24152.984127963.42443.117058174.49742.06545
8196.80136.316958233.26544.274718648.16737.547129575.27541.600319691.193 38.3546
9907.93842.682849960.43525.3737210086.2925.3601310117.8431.25603 10170.720.85462
10234.2626.1133210397.4322.6739610444.8735.1449210520.0642.2918410655.27124.4837
#Mann= 3 , 0 , 0
6390.532  0.0451       06390.532  0.0451       010655.27  0.0451       0
#XS Ineff= 2 , 0
       09907.204                       0
Bank Sta=6390.532,10655.27
Exp/Cntr=0.3,0.1

Type RM Length L Ch R = 1 , 7422.49,481.006200,481.006200,481.006200
XS GIS Cut Line= 6
 803700.94838834717339.705536489803288.470035434717198.413116053
802863.720498502717031.387262821802213.462307721716731.512904838
 800701.39192456 715917.52475296800399.118910223715702.807969987
#Sta/Elev= 30
6533.13196.499196728.88470.274516859.45667.960426919.81458.84318 7090.5851.42522
 7111.98 42.62387147.43250.247717197.57952.581887492.18444.151987587.59547.40827
7609.37941.78727 7631.1948.193147697.09648.900987773.98737.607837895.45334.91508
7928.66639.726547961.87933.401498043.44638.723818967.71233.703379070.45937.34337
9639.76135.924079696.41740.061339753.07433.704679779.45719.917519889.78825.39684
10013.8717.50603 10065.836.23604 10127.581.6393810190.78 92.409810230.76105.1086
#Mann= 3 , 0 , 0
6533.131   0.042       06533.131   0.042       010230.76   0.042       0
#XS Ineff= 2 , 0
       09693.976                       0
Bank Sta=6533.131,10230.76
Exp/Cntr=0.3,0.1

Type RM Length L Ch R = 1 ,6941.484,481.006200,481.006200,481.006200
XS GIS Cut Line= 6
803994.743095068717052.458045578803135.948028415 716747.01036343
802612.382277161716518.312901139 802212.73773855716320.702556625
801439.945637256715878.106352076800735.104538888715352.265053257
#Sta/Elev= 30
6553.251143.15946594.937129.1593 6657.87125.58686689.336 114.2366921.48473.64314
7027.39165.650137059.35149.823097123.27147.252137498.53143.588257522.29340.02783
7606.84642.442597617.67838.821888033.52732.120268088.937 37.2524 8111.11  31.751
8144.36835.227988356.57130.182168491.00334.025178717.84829.999449433.10335.70149
9584.75633.135419642.645 37.51749873.047 33.59549906.22820.840239984.88915.88043
10034.3316.99682 10059.127.7858610096.8557.1116710187.46113.154110253.02169.8954
#Mann= 3 , 0 , 0
6553.251  0.0418       06553.251  0.0418       010253.02  0.0418       0
#XS Ineff= 2 , 0
       09636.477                       0
Bank Sta=6553.251,10253.02
Exp/Cntr=0.3,0.1

Type RM Length L Ch R = 1 ,6460.478,481.006200,481.006200,481.006200
XS GIS Cut Line= 6
805388.050708956716874.386511949804174.837641269 716550.34782064
803107.943181992716160.059382856802538.706750989715896.035139501
802061.479967207715639.573129043800886.352369934714918.469006732
#Sta/Elev= 30
5472.086124.29525979.68776.442136020.98775.746096082.93888.536596134.58778.46581
6394.09376.943746414.85367.21857 6613.0964.355336842.88550.058787064.79745.13085
7096.05955.599187202.40537.445317287.44133.810687330.09633.754177351.42344.31164
7673.94635.072387695.29728.854528240.59434.272158251.66928.59719 8273.8233.77573
8824.31227.474139823.90431.988339913.536 30.6876 9953.1715.6326810012.1715.19507
 10094.716.95272   1012129.6455310177.6433.7321710259.7561.6864510412.87 90.2536
#Mann= 3 , 0 , 0
5472.086  0.0422       05472.086  0.0422       010412.87  0.0422       0
#XS Ineff= 2 , 0
       09411.219                       0
Bank Sta=5472.086,10412.87
Exp/Cntr=0.3,0.1

Type RM Length L Ch R = 1 ,5979.472,481.006200,481.006200,481.006200
XS GIS Cut Line= 6
806090.851903054716509.289121414 804427.08745715716104.606304482
803200.431770116 715673.16509828802252.358143151715205.527406171
800558.444801897714182.945053875799631.273455441713750.093206421
#Sta/Elev= 30
4982.97970.423585695.26261.56068 5808.2753.016475993.61155.215826127.60172.97984
6303.43572.788826635.545 63.44476666.73158.040657043.38454.966677296.36839.44715
7412.79242.637847444.65835.026697529.90337.07131 7561.8730.903667583.18135.71317
7668.73234.443867696.31427.821169413.04730.71608 9836.6728.079549883.73917.52837
 9966.1115.1086710060.5716.6597810084.0625.9893810189.7825.9773810330.7436.00172
10600.7735.3170610740.2826.0790211462.7926.5226311932.1841.9543612056.8751.10142
#Mann= 3 , 0 , 0
4982.979    0.04       04982.979    0.04       012056.87    0.04       0
#XS Ineff= 2 , 0
       09228.903        10275.29       0
Bank Sta=4982.979,12056.87
Exp/Cntr=0.3,0.1

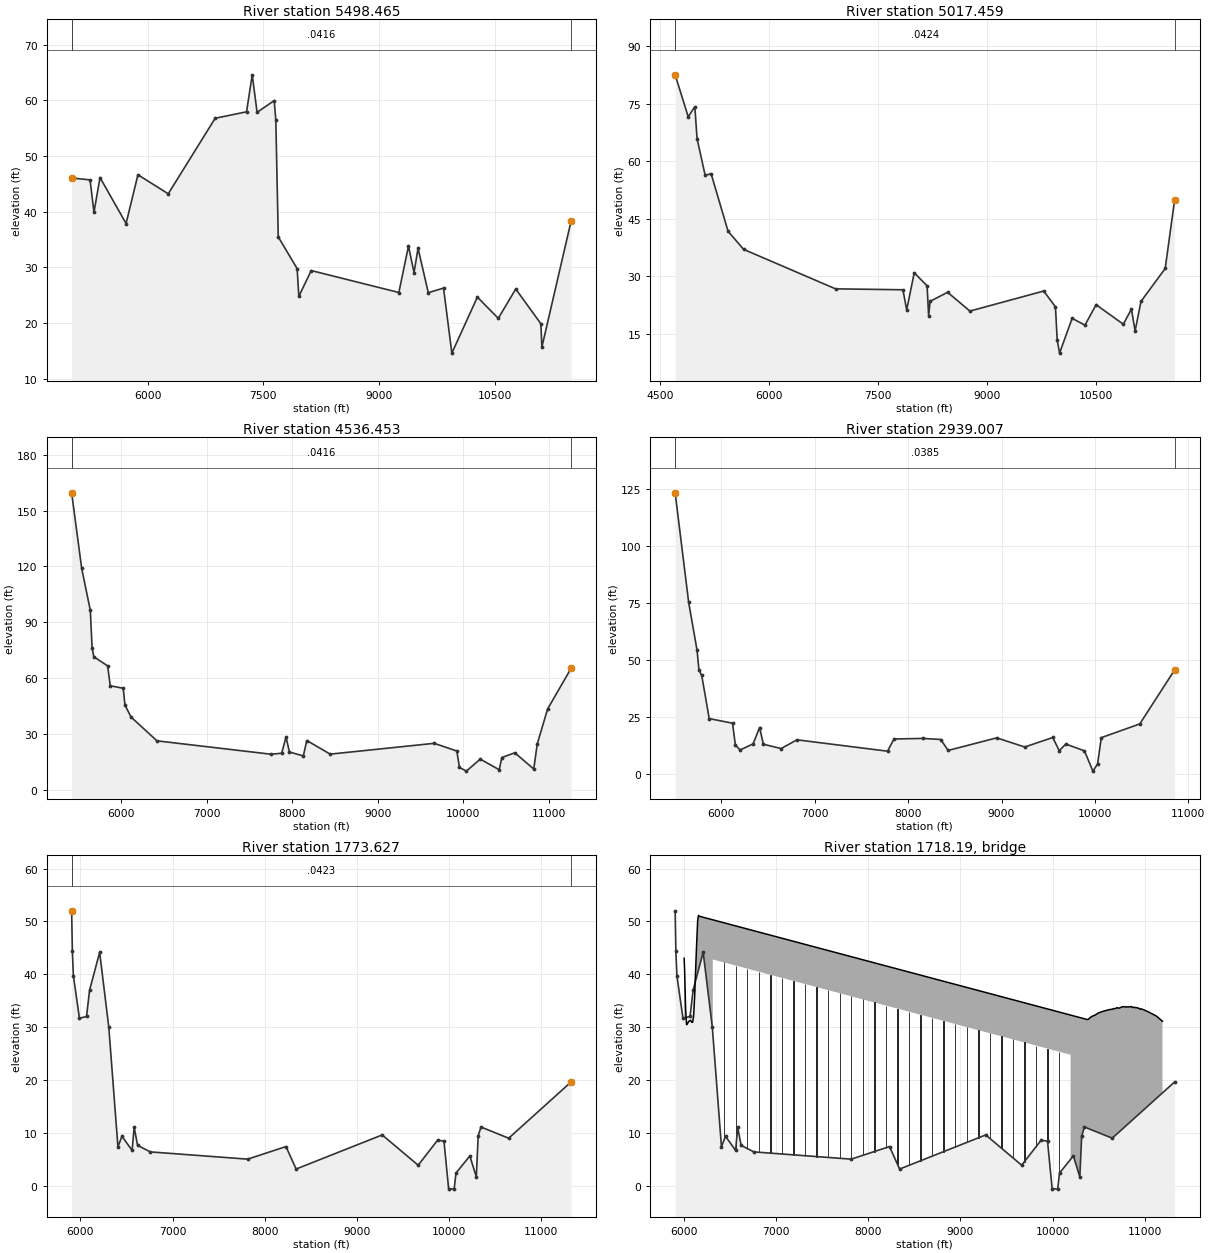
Type RM Length L Ch R = 1 ,5498.465,481.006200,481.006200,481.006200
XS GIS Cut Line= 6
 806315.42874539716122.264346029804638.054721773715737.906344593
803121.433368862 715223.90878655 802109.16498065714683.815246403
 801344.39099136713983.154442072800451.151000708713660.206649363
#Sta/Elev= 30
5015.67446.062685254.52745.719435304.97639.898175383.38346.14345 5720.8737.88051
5874.57946.644366267.07443.217286875.12856.796417281.67457.957487355.35864.60463
7418.33757.857337639.72259.972037660.83456.504037692.60535.476587937.30829.76608
 7958.6824.775588119.50829.424949254.84725.478739379.68633.826739451.20729.04837
9503.57333.423169636.10725.448559833.86326.272529941.44414.5834810272.0324.64849
   1054320.8373110769.1126.1073811094.9119.8636611107.8415.6677111485.4738.27049
#Mann= 3 , 0 , 0
5015.674  0.0416       05015.674  0.0416       011485.47  0.0416       0
#XS Ineff= 2 , 0
       09358.741        10635.02       0
Bank Sta=5015.674,11485.47
Exp/Cntr=0.3,0.1

Type RM Length L Ch R = 1 ,5017.459,481.006200,481.006200,481.006200
XS GIS Cut Line= 6
807102.053229476 715409.41456842805320.693075627715075.917174086
803920.999787837714737.250514343802727.403503805714330.393185765
801516.391771227713712.827024996800538.105268478713532.896707058
#Sta/Elev= 30
4708.54882.538414888.17371.601164979.48174.223495009.91765.900635121.61256.30705
5202.877 56.75685436.51341.733685650.11337.003266915.83426.695727843.085 26.4569
7894.93821.214487998.767 30.88738175.85827.485448196.776 19.73238217.69323.44332
8458.36625.802358764.58220.893459780.70626.127439942.16222.010879966.15113.34179
    99999.92443910171.7718.99957 10348.617.2249110501.4822.5640710876.0917.46416
 10987.721.3830811038.4215.7187611119.2723.4123311452.7832.0174111581.35 49.7593
#Mann= 3 , 0 , 0
4708.548  0.0424       04708.548  0.0424       011581.35  0.0424       0
#XS Ineff= 2 , 0
       09551.143        10906.02       0
Bank Sta=4708.548,11581.35
Exp/Cntr=0.3,0.1

Type RM Length L Ch R = 1 ,4536.453,1597.446300,1597.446300,1597.446300
XS GIS Cut Line= 6
806731.221080996714279.015169541805561.396816668714093.738014166
803005.050602763713676.766664305802260.755343454713539.131672916
 801966.26292684713489.536597061 800963.51696945713347.990764042
#Sta/Elev= 30
5418.709159.62375536.346118.94965637.56596.320355657.80976.381665678.052 71.4289
5840.00266.509215870.36855.822646022.24154.464546042.49545.485086113.38238.99827
6417.18526.17642 7754.5318.970147876.11619.527847926.77728.205887967.30620.17727
 8129.4218.059578169.94926.365968443.51719.030129660.62524.845199925.49520.70912
9956.02211.8645810036.999.88820110199.3816.3494510421.4710.6237710451.7817.19351
10603.3419.7534910825.6111.0272710866.0324.4489310987.2743.2992511261.5765.16266
#Mann= 3 , 0 , 0
5418.709  0.0416       05418.709  0.0416       011261.57  0.0416       0
#XS Ineff= 2 , 0
       09612.481                       0
Bank Sta=5418.709,11261.57
Exp/Cntr=0.3,0.1

Type RM Length L Ch R = 1 ,2939.007,1165.380200,1165.380200,1165.380200
XS GIS Cut Line= 6
805849.761208531712439.770962863801666.012821694 712409.75066813
801236.325321694712427.111779241800936.846155028712474.854834797
800810.978099472712548.639557019800528.860043916712600.722890352
#Sta/Elev= 30
5503.845123.4367 5648.6175.320585738.61254.290355758.61345.607835788.61343.24784
5868.615  24.3276118.62222.305156148.62312.779736198.62410.531616338.628 13.2165
6408.62920.40418 6448.6313.082386638.63511.16262 6808.6415.009237778.66510.01614
7848.66615.371468158.67415.621118348.67915.146368428.681 10.34528948.69515.86715
9248.70211.85165 9548.7116.026169618.71210.245369688.71513.160299888.87810.14004
9978.951 1.2617910028.994.37105210069.0215.95859 10481.121.9763210853.7945.64567
#Mann= 3 , 0 , 0
5503.845  0.0385       05503.845  0.0385       010853.79  0.0385       0
#XS Ineff= 2 , 0
       08253.484                       0
Bank Sta=5503.845,10853.79
Exp/Cntr=0.3,0.1

Type RM Length L Ch R = 1 ,1773.627,168.954500,168.954500,168.954500
XS GIS Cut Line= 6
805722.213720292 710349.50268133804010.871127695711080.492264688
803211.391961068711304.450598001802578.304754943711414.672522187
800817.835738361711450.332265362800499.576227646711429.761701257
#Sta/Elev= 30
  5905.852.009255913.72144.322035924.70239.724975990.586 31.6761 6067.4532.01398
6100.39336.993176209.60244.159336309.02529.945876407.8527.3571776451.7749.350868
6561.5816.6654196583.54211.038086621.1357.6298466759.2336.3893347814.9275.015534
8230.325  7.39948340.0793.1437999273.5669.6023769663.7843.8674829873.7898.594061
 9943.79 8.426569993.818 -0.559110053.89-0.6561710073.912.385276 10224.15.626916
10294.211.65179110314.379.40899310344.6111.0975310645.288.97991711321.4219.61438
#Mann= 3 , 0 , 0
  5905.8  0.0423       0  5905.8  0.0423       011321.42  0.0423       0
#XS Ineff= 2 , 0
       07524.727        10395.26       0
Bank Sta=5905.8,11321.42
Exp/Cntr=0.3,0.1

Type RM Length L Ch R = 3 , 1718.19,,,
BEGIN DESCRIPTION:
END DESCRIPTION:
Bridge Culvert--1,0,-1,-1, 0
Deck Dist Width WeirC Skew NumUp NumDn MinLoCord MaxHiCord MaxSubmerge Is_Ogee
62.477250,44.000000,2.6,0, 54, 54, , , 0.95, 0, 0,0,,
 6003.39 6008.18 6019.04 6028.45 6029.90 6040.76 6051.62 6073.34 6084.20 6095.06
 6105.92 6116.78 6127.64 6131.01 6138.50 6149.36 6156.66 6160.22 6163.96 6313.95
 6313.9510193.9510193.9510376.9510386.9610406.9610426.9610456.9710496.9710546.98
10616.9910647.0010657.0010677.0010697.0110717.0110757.0110777.0210787.0210797.02
10807.0210857.0310867.0310887.0410897.0410917.0410927.0410937.0410947.0410957.05
10967.0511027.0611127.0711190.44
   43.03   40.85   33.62   30.66   30.46   30.70   31.06   31.31   30.93   30.93
   32.06   35.56   40.81   42.35   45.62   49.97   50.99   51.15   51.00   50.31
   50.31   32.28   32.28   31.43   31.49   31.82   32.05   32.26   32.70   33.00
   33.33   33.38   33.50   33.50   33.68   33.58   33.86   33.87   33.79   33.87
   33.81   33.88   33.70   33.78   33.67   33.69   33.57   33.56   33.39   33.46
   33.42   32.98   32.07   31.10
 -956.97 -959.15 -966.38 -969.34 -969.54 -969.30 -968.94 -968.69 -969.07 -969.07
 -967.94 -964.44 -959.19 -957.65 -954.38 -950.03 -949.01 -948.85 -949.00 -949.69
   42.81   24.78 -967.72 -968.57 -968.51 -968.18 -967.95 -967.74 -967.30 -967.00
 -966.67 -966.62 -966.50 -966.50 -966.32 -966.42 -966.14 -966.13 -966.21 -966.13
 -966.19 -966.12 -966.30 -966.22 -966.33 -966.31 -966.43 -966.44 -966.61 -966.54
 -966.58 -967.02 -967.93 -968.90
 6003.39 6008.18 6019.04 6028.45 6029.90 6040.76 6051.62 6073.34 6084.20 6095.06
 6105.92 6116.78 6127.64 6131.01 6138.50 6149.36 6156.66 6160.22 6163.96 6352.92
 6352.9210232.9210232.9210376.9510386.9610406.9610426.9610456.9710496.9710546.98
10616.9910647.0010657.0010677.0010697.0110717.0110757.0110777.0210787.0210797.02
10807.0210857.0310867.0310887.0410897.0410917.0410927.0410937.0410947.0410957.05
10967.0511027.0611127.0711190.44
   43.03   40.85   33.62   30.66   30.46   30.70   31.06   31.31   30.93   30.93
   32.06   35.56   40.81   42.35   45.62   49.97   50.99   51.15   51.00   50.12
   50.12   32.10   32.10   31.43   31.49   31.82   32.05   32.26   32.70   33.00
   33.33   33.38   33.50   33.50   33.68   33.58   33.86   33.87   33.79   33.87
   33.81   33.88   33.70   33.78   33.67   33.69   33.57   33.56   33.39   33.46
   33.42   32.98   32.07   31.10
 -956.97 -959.15 -966.38 -969.34 -969.54 -969.30 -968.94 -968.69 -969.07 -969.07
 -967.94 -964.44 -959.19 -957.65 -954.38 -950.03 -949.01 -948.85 -949.00 -949.88
   42.62   24.60 -967.90 -968.57 -968.51 -968.18 -967.95 -967.74 -967.30 -967.00
 -966.67 -966.62 -966.50 -966.50 -966.32 -966.42 -966.14 -966.13 -966.21 -966.13
 -966.19 -966.12 -966.30 -966.22 -966.33 -966.31 -966.43 -966.44 -966.61 -966.54
 -966.58 -967.02 -967.93 -968.90
Pier Skew, UpSta & Num, DnSta & Num=  ,6437.24, 2 ,6476.21, 2 , 0 , 0 , 0 ,,
    4.00    4.00
 -950.27   49.73
    4.00    4.00
 -950.45   49.55
Pier Skew, UpSta & Num, DnSta & Num=  ,6562.53, 2 ,6601.50, 2 , 0 , 0 , 0 ,,
    4.00    4.00
 -950.85   49.15
    4.00    4.00
 -951.03   48.97
Pier Skew, UpSta & Num, DnSta & Num=  ,6687.82, 2 ,6726.79, 2 , 0 , 0 , 0 ,,
    4.00    4.00
 -951.43   48.57
    4.00    4.00
 -951.61   48.39
Pier Skew, UpSta & Num, DnSta & Num=  ,6813.11, 2 ,6852.08, 2 , 0 , 0 , 0 ,,
    4.00    4.00
 -952.01   47.99
    4.00    4.00
 -952.19   47.81
Pier Skew, UpSta & Num, DnSta & Num=  ,6938.40, 2 ,6977.38, 2 , 0 , 0 , 0 ,,
    4.00    4.00
 -952.60   47.40
    4.00    4.00
 -952.78   47.22
Pier Skew, UpSta & Num, DnSta & Num=  ,7063.69, 2 ,7102.67, 2 , 0 , 0 , 0 ,,
    4.00    4.00
 -953.18   46.82
    4.00    4.00
 -953.36   46.64
Pier Skew, UpSta & Num, DnSta & Num=  ,7188.98, 2 ,7227.96, 2 , 0 , 0 , 0 ,,
    4.00    4.00
 -953.76   46.24
    4.00    4.00
 -953.94   46.06
Pier Skew, UpSta & Num, DnSta & Num=  ,7314.27, 2 ,7353.25, 2 , 0 , 0 , 0 ,,
    4.00    4.00
 -954.34   45.66
    4.00    4.00
 -954.52   45.48
Pier Skew, UpSta & Num, DnSta & Num=  ,7439.56, 2 ,7478.54, 2 , 0 , 0 , 0 ,,
    4.00    4.00
 -954.92   45.08
    4.00    4.00
 -955.11   44.89
Pier Skew, UpSta & Num, DnSta & Num=  ,7564.85, 2 ,7603.83, 2 , 0 , 0 , 0 ,,
    4.00    4.00
 -955.51   44.49
    4.00    4.00
 -955.69   44.31
Pier Skew, UpSta & Num, DnSta & Num=  ,7690.14, 2 ,7729.12, 2 , 0 , 0 , 0 ,,
    4.00    4.00
 -956.09   43.91
    4.00    4.00
 -956.27   43.73
Pier Skew, UpSta & Num, DnSta & Num=  ,7815.43, 2 ,7854.41, 2 , 0 , 0 , 0 ,,
    4.00    4.00
 -956.67   43.33
    4.00    4.00
 -956.85   43.15
Pier Skew, UpSta & Num, DnSta & Num=  ,7940.72, 2 ,7979.70, 2 , 0 , 0 , 0 ,,
    4.00    4.00
 -957.25   42.75
    4.00    4.00
 -957.43   42.57
Pier Skew, UpSta & Num, DnSta & Num=  ,8066.01, 2 ,8104.99, 2 , 0 , 0 , 0 ,,
    4.00    4.00
 -957.84   42.16
    4.00    4.00
 -958.02   41.98
Pier Skew, UpSta & Num, DnSta & Num=  ,8191.30, 2 ,8230.28, 2 , 0 , 0 , 0 ,,
    4.00    4.00
 -958.42   41.58
    4.00    4.00
 -958.60   41.40
Pier Skew, UpSta & Num, DnSta & Num=  ,8316.59, 2 ,8355.57, 2 , 0 , 0 , 0 ,,
    4.00    4.00
 -959.00   41.00
    4.00    4.00
 -959.18   40.82
Pier Skew, UpSta & Num, DnSta & Num=  ,8441.88, 2 ,8480.86, 2 , 0 , 0 , 0 ,,
    4.00    4.00
 -959.58   40.42
    4.00    4.00
 -959.76   40.24
Pier Skew, UpSta & Num, DnSta & Num=  ,8567.17, 2 ,8606.15, 2 , 0 , 0 , 0 ,,
    4.00    4.00
 -960.16   39.84
    4.00    4.00
 -960.35   39.65
Pier Skew, UpSta & Num, DnSta & Num=  ,8692.46, 2 ,8731.44, 2 , 0 , 0 , 0 ,,
    4.00    4.00
 -960.75   39.25
    4.00    4.00
 -960.93   39.07
Pier Skew, UpSta & Num, DnSta & Num=  ,8817.75, 2 ,8856.73, 2 , 0 , 0 , 0 ,,
    4.00    4.00
 -961.33   38.67
    4.00    4.00
 -961.51   38.49
Pier Skew, UpSta & Num, DnSta & Num=  ,8943.04, 2 ,8982.02, 2 , 0 , 0 , 0 ,,
    4.00    4.00
 -961.91   38.09
    4.00    4.00
 -962.09   37.91
Pier Skew, UpSta & Num, DnSta & Num=  ,9068.33, 2 ,9107.31, 2 , 0 , 0 , 0 ,,
    4.00    4.00
 -962.49   37.51
    4.00    4.00
 -962.67   37.33
Pier Skew, UpSta & Num, DnSta & Num=  ,9193.62, 2 ,9232.60, 2 , 0 , 0 , 0 ,,
    4.00    4.00
 -963.07   36.93
    4.00    4.00
 -963.26   36.74
Pier Skew, UpSta & Num, DnSta & Num=  ,9318.91, 2 ,9357.89, 2 , 0 , 0 , 0 ,,
    4.00    4.00
 -963.66   36.34
    4.00    4.00
 -963.84   36.16
Pier Skew, UpSta & Num, DnSta & Num=  ,9444.20, 2 ,9483.18, 2 , 0 , 0 , 0 ,,
    4.00    4.00
 -964.24   35.76
    4.00    4.00
 -964.42   35.58
Pier Skew, UpSta & Num, DnSta & Num=  ,9569.50, 2 ,9608.47, 2 , 0 , 0 , 0 ,,
    4.00    4.00
 -964.82   35.18
    4.00    4.00
 -965.00   35.00
Pier Skew, UpSta & Num, DnSta & Num=  ,9694.79, 2 ,9733.76, 2 , 0 , 0 , 0 ,,
    4.00    4.00
 -965.40   34.60
    4.00    4.00
 -965.58   34.42
Pier Skew, UpSta & Num, DnSta & Num=  ,9820.08, 2 ,9859.05, 2 , 0 , 0 , 0 ,,
    4.00    4.00
 -965.99   34.01
    4.00    4.00
 -966.17   33.83
Pier Skew, UpSta & Num, DnSta & Num=  ,9945.37, 2 ,9984.34, 2 , 0 , 0 , 0 ,,
    4.00    4.00
 -966.57   33.43
    4.00    4.00
 -966.75   33.25
Pier Skew, UpSta & Num, DnSta & Num=  ,10070.66, 2 ,10109.63, 2 , 0 , 0 , 0 ,,
    4.00    4.00
 -967.15   32.85
    4.00    4.00
 -967.33   32.67
BR Coef=-1 , 0 , 0 ,, 0 ,,,0.8,0,1,0,
WSPro=,,,, 1 ,,,, 0 ,,,, 0 ,,,,-1 ,-1 ,-1 , 0 , 0 , 0 , 0 , 0
BC Design=,, 0 ,, 0 ,,,,,,

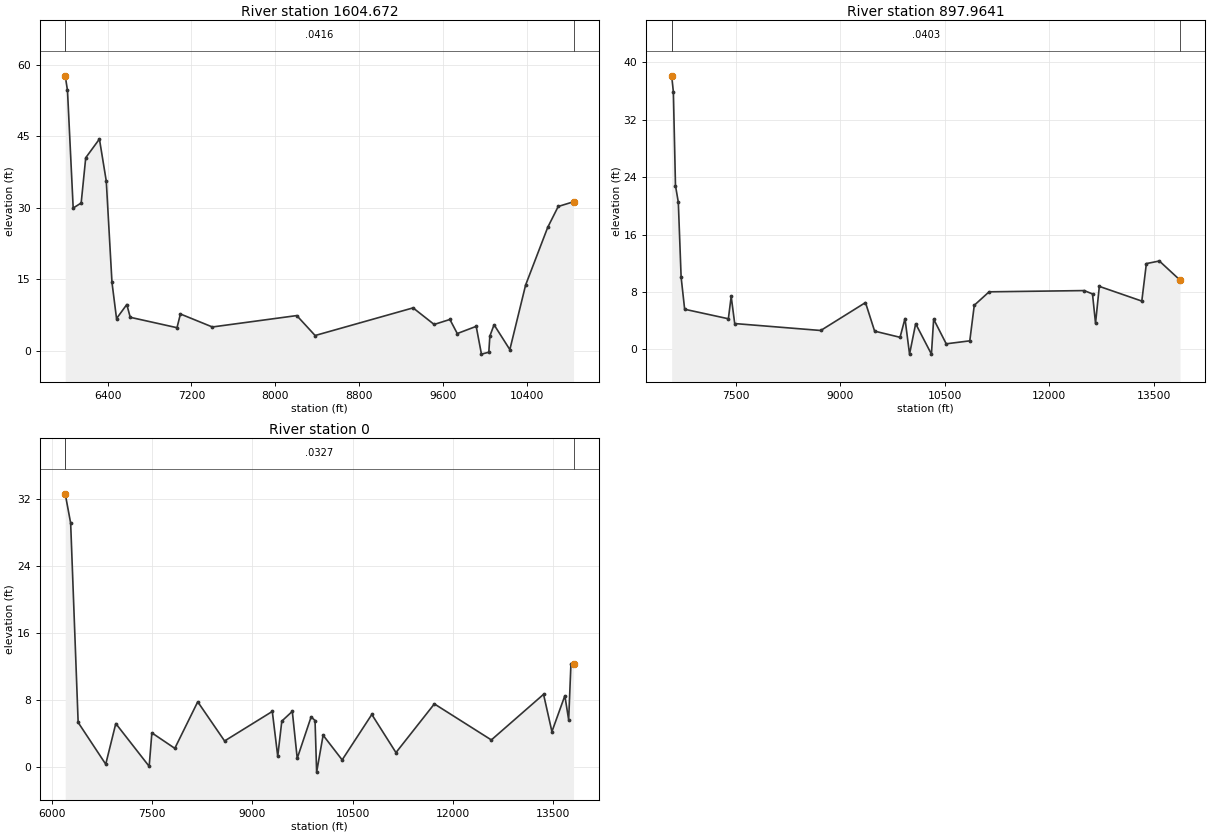
Type RM Length L Ch R = 1 ,1604.672,706.707900,706.707900,706.707900
XS GIS Cut Line= 6
805664.922053635710278.322125793803979.621127695 710997.15893133
802982.592682838711232.016293123802333.721155047711277.589209795
801498.217682838711227.676015347800999.125707615711253.447663711
#Sta/Elev= 30
 5996.81 57.70146018.46854.655966072.827  29.9796148.92831.035526192.41540.52191
6322.87544.449846388.10535.641196442.46314.39007 6485.95  6.79916583.7959.749683
 6616.41 7.067987062.1484.8847757094.7637.7593897399.1695.0371578203.6127.427351
8378.2653.2465099312.0489.0430869512.5375.5672019662.8336.6109069732.9713.659885
9913.3265.1661119963.425-0.6561710033.56 -0.255510043.583.13461910083.665.502246
10233.950.28997310384.1913.8255810594.7125.9153210694.8930.3045610840.9231.29273
#Mann= 3 , 0 , 0
 5996.81  0.0416       0 5996.81  0.0416       010840.92  0.0416       0
#XS Ineff= 2 , 0
       07413.991        10410.74       0
Bank Sta=5996.81,10840.92
Exp/Cntr=0.3,0.1

Type RM Length L Ch R = 1 ,897.9641,897.964100,897.964100,897.964100
XS GIS Cut Line= 6
805429.042424023710317.124209136 803142.58409068710674.763098001
802637.375757366710690.388098001802108.038123555710602.805144518
800030.926040107709810.557271467 798455.09907439709129.447497926
#Sta/Elev= 30
6583.428 38.10886607.76335.867156638.12722.802426678.61420.51637  6719.110.05797
6769.7085.5949117397.2474.2695157437.7337.3808057488.3413.6028258723.1752.636022
9365.4956.5244279496.7692.5455779861.6631.6858939932.6154.2931319998.018-0.65617
10085.833.58061310312.07-0.6561710344.014.21371610524.54 0.7793710862.831.195454
10927.19 6.1521311139.928.02240712505.088.19523712624.267.72775512667.743.638989
12722.098.78005913331.936.73319313397.5511.95419 13583.812.3168713880.269.658008
#Mann= 3 , 0 , 0
6583.428  0.0403       06583.428  0.0403       013880.26  0.0403       0
#XS Ineff= 2 , 0
       07342.113        11065.83       0
Bank Sta=6583.428,13880.26
Exp/Cntr=0.3,0.1

Type RM Length L Ch R = 1 ,       0,0.000000,0.000000,0.000000
XS GIS Cut Line= 6
805588.755374163709150.764336661805085.283151954709124.722669989
803870.005374193709949.375447795802706.810929745709576.111558869
800624.396791607 709482.08139731798681.051884234 708520.68093434
#Sta/Elev= 30
6200.63232.621186282.10629.123156394.3275.2836466807.0380.2911526957.5395.152515
7457.0450.0343927497.3254.0389767840.6462.1880388183.5817.7519858585.3543.069901
9299.3686.599765 9380.681.2343179441.6635.4435119598.6886.6108069672.261  0.9911
9880.2295.9503549938.7975.5141349962.874-0.6561710059.683.75798610344.630.806384
10788.27 6.2378111149.681.67987411724.157.50263412576.74 3.1925113358.098.646535
13483.344.18520313676.918.48101613733.845.597452   1376812.3234713806.6612.31464
#Mann= 3 , 0 , 0
6200.632  0.0327       06200.632  0.0327       013806.66  0.0327       0
#XS Ineff= 2 , 0
       0                11526.49       0
Bank Sta=6200.632,13806.66
Exp/Cntr=0.3,0.1